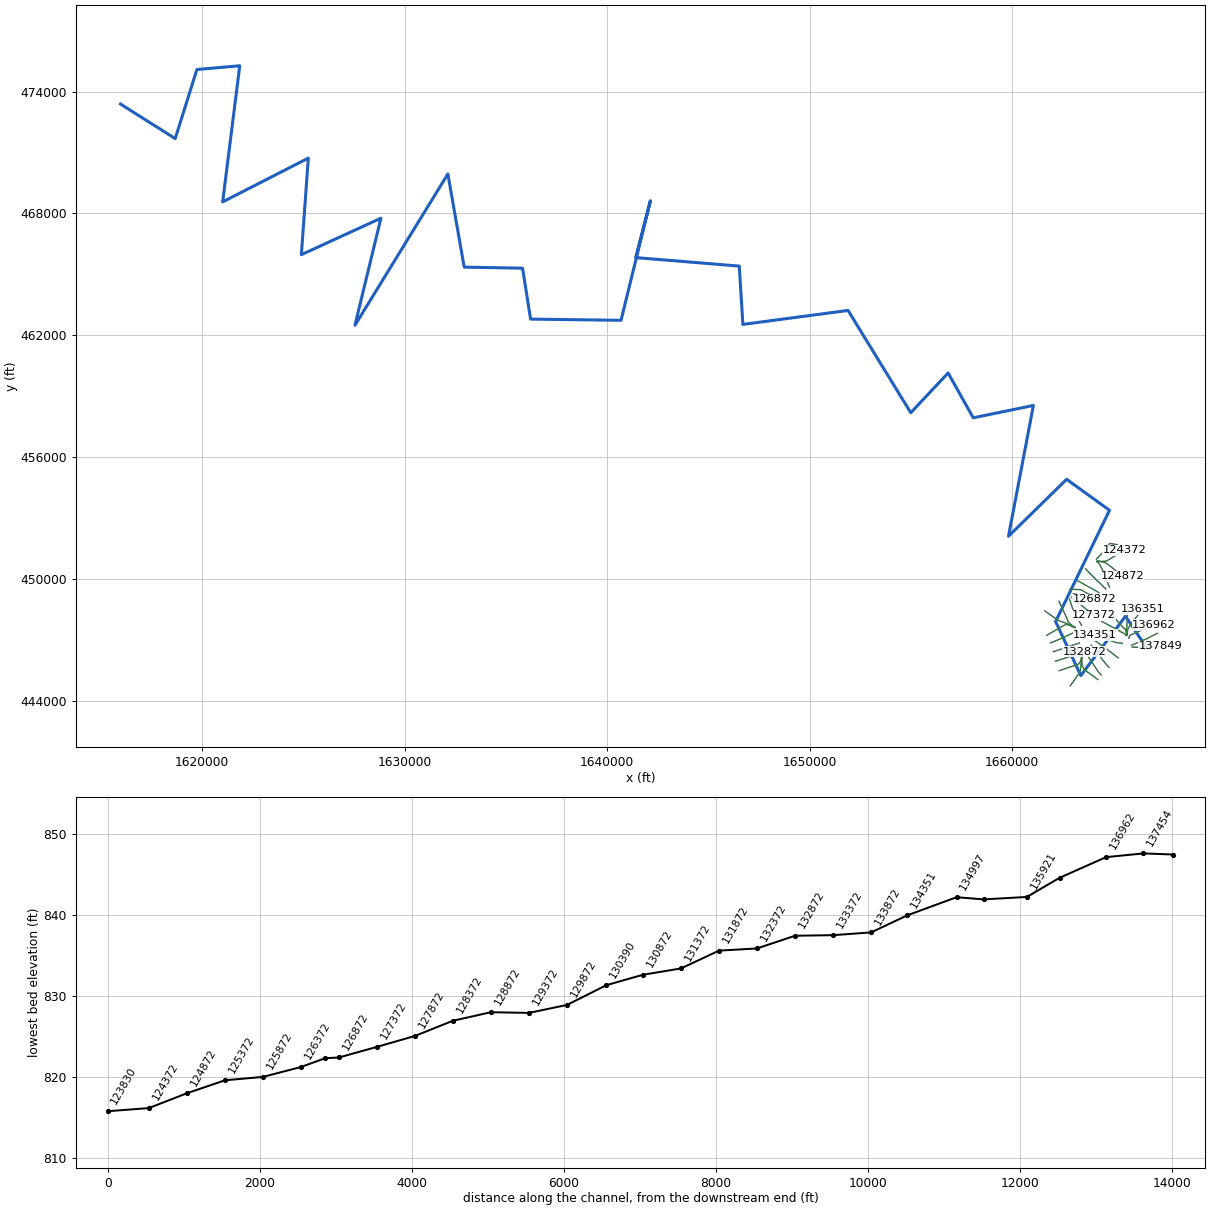
--- FshCrk.prj (project) ---

Proj Title=FshCrk
Current Plan=p01
Default Exp/Contr=0,0
English Units
Geom File=g01
Flow File=f01
Plan File=p01
BEGIN DESCRIPTION:
---------- MODELED AS PART OF WVEM CTP PROGRAM, 2025----------
Stream Name: Fish Creek
Flood Zone: AFH
Marshall County, WV
HEC-RAS Version: RAS 6.6
Vertical Datum: NAVD88
Projection: NAD 1983 StatePlane West Virginia N FIPS 4701 (US Feet)
Terrain: 1-meter West Virginia FEMA R3 South Central (collected 2018-2019)
Land Use: 2024 NLCD
Hydrologic Method:
Duda et al., "Estimation of magnitude and frequency of floods for rural, unregulated streams in and near Virginia and West Virginia." September 8, 2025.
Additional Model Notes:
KWSE to Zone AE
END DESCRIPTION:
DSS Export Rating Curves= 0
DSS Export Rating Curve Sorted= 0
DSS Export Volume Flow Curves= 0
DXF OffsetX= 0
DXF OffsetY= 0
DXF ScaleX= 0
DXF ScaleY= 0

--- FshCrk.p01 (plan) ---

Plan Title=Floodplain
Program Version=6.60
Short Identifier=Floodplain
Geom File=g01
Flow File=f01
Subcritical Flow
K Sum by GR= 0
Std Step Tol= 0.01
Critical Tol= 0.01
Num of Std Step Trials= 20
Max Error Tol= 0.3
Flow Tol Ratio= 0.001
Split Flow NTrial= 30
Split Flow Tol= 0.02
Split Flow Ratio= 0.02
Log Output Level= 0
Friction Slope Method= 1
Unsteady Friction Slope Method= 2
Unsteady Bridges Friction Slope Method= 1
Parabolic Critical Depth
Global Vel Dist= 0 , 0 , 0
Global Log Level= 0
CheckData=False
Encroach Param=-1 ,0,0, 0
Flow Ratio Tolerance=0.1
Flow Ratio Min Ratio=0.5
Flow Ratio Max Ratio=4
Flow Ratio Max Iterations= 10
Mapping Interval=1HOUR
Computation Time Step Use Courant=        0
Computation Time Step Use Time Series=    0
Computation Time Step Count To Double=0
Computation Time Step Max Doubling=0
Computation Time Step Max Halving=0
Computation Time Step Residence Courant=0
Run HTab= 0
Run UNet= 0
Run Sediment= 0
Run PostProcess= 0
Run WQNet= 0
Run RASMapper=-1
UNET Theta= 0
UNET Theta Warmup= 0
UNET ZTol= 0
UNET ZSATol= 0
UNET MxIter= 0
UNET Max Iter WO Improvement= 0
UNET MaxInSteps= 0
UNET DtIC= 0
UNET DtMin= 0
UNET MaxCRTS= 0
UNET WFStab= 0
UNET SFStab= 0
UNET WFX= 1
UNET SFX= 1
UNET Gravity=32.17405
UNET 1D Methodology=Finite Difference
UNET DSS MLevel= 1
UNET Pardiso=0
UNET DZMax Abort= 0
UNET Use Existing IB Tables= 0
UNET Froude Reduction=False
UNET Froude Limit= 0
UNET Froude Power= 0
UNET D1 Cores= 0
UNET WindReference=Eulerian
UNET WindDragFormulation=Hsu (1988)
UNET D2 Coriolis=0
UNET D2 Cores= 0
UNET D2 Theta= 1
UNET D2 Theta Warmup= 1
UNET D2 Z Tol= 0.01
UNET D2 Volume Tol= 0.01
UNET D2 Max Iterations= 20
UNET D2 Advanced Convergence=0
UNET D2 WS Max Tol=0.15
UNET D2 WS RMS Tol=0.002
UNET D2 WS Stall Tol=1
UNET D2 Equation= 0
UNET D2 RampUpFraction=0.1
UNET D2 TimeSlices= 1
UNET D2 Turbulence Formulation=Non-Conservative (original)
UNET D2 Eddy Viscosity=0.3
UNET D2 Transverse Eddy Viscosity=0.1
UNET D2 Smagorinsky Mixing=0
UNET D2 BCVolumeCheck=0
UNET D2 Cores=0
UNET D2 SolverType=PARDISO (Direct)
UNET D2 Minimum Iterations= 3
UNET D2 Maximum Iterations= 30
UNET D2 Restart Number= 10
UNET D2 Relaxation Coeff=1.3
UNET D2 SOR Precondition Iterations= 10
UNET D2 ILUT Maximum Fill= 8
UNET D2 ILUT Tolerance=1E-08
UNET D2 Convergence Tolerance=0.00001
PS Theta= 1
PS WS Tol= 0.01
PS Volume Tol= 0.01
PS Max Iterations= 20
PS Equation= 0
PS Advance Time Step=-1
PS Target Courant=0.9
PS Time Slices= 1
PS Iterate With 2D=0
PS Project Initial WSE from DS=-1
PS Ramp Up Initial WSE from US=-1
PS Cores=0
UNET D1D2 MaxIter= 0
UNET D1D2 ZTol=0.01
UNET D1D2 QTol=0.1
UNET D1D2 MinQTol=1
Write IC File= 0
Write IC File at Fixed DateTime=0
Write IC File at Sim End=0
Echo Input=False
Echo Parameters=False
Echo Output=False
Write Detailed= 0
HDF Write Warmup=0
HDF Write Time Slices=0
HDF Flush=0
HDF Compression= 1
HDF Chunk Size= 1
HDF Spatial Parts= 1
HDF Use Max Rows=0
HDF Fixed Rows= 1
Calibration Method= 0
Calibration Iterations= 20
Calibration Max Change=0.05
Calibration Tolerance=0.2
Calibration Maximum=1.5
Calibration Minimum=0.5
Calibration Optimization Method= 1
WQ AD Non Conservative
WQ ULTIMATE=-1
WQ Max Comp Step=1HOUR
WQ Output Interval=15MIN
WQ Output Selected Increments= 0
WQ Create Restart=0
WQ Fixed Restart=0
WQ System Summary=0
WQ Write To DSS=0
Sorting and Armoring Iterations= 10
XS Update Threshold= 0.02
Bed Roughness Predictor= 0
Processes Affected by Predictor=Sediment Only
Hydraulics Update Threshold= 0.02
Energy Slope Method= 1
Volume Change Method= 1
Sediment Retention Method= 0
Sediment TS Multiplier= 1
Warm Up Method= 0
XS Weighting Method= 0
Number of US Weighted Cross Sections= 1
Number of DS Weighted Cross Sections= 1
Upstream XS Weight=0
Main XS Weight=1
Downstream XS Weight=0
Number of DS XS's Weighted with US Boundary= 1
Upstream Boundary Weight= 1
Weight of XSs Associated with US Boundary= 0
Number of US XS's Weighted with DS Boundary= 1
Downstream Boundary Weight= 0.5
Weight of XSs Associated with DS Boundary= 0.5
Percentile Method= 0
Sediment Output Level= 3
Mass or Volume Output= 0
Output Increment Type= 1
Profile and TS Output Increment= 1
Transport Output Increment 1
XS Output Flag= 0
XS Output Increment= 10
Read HDF5 Sediment Hotstart= 0
Sediment Hotstart Type= 0
Write Gradation File= 0
Read Gradation Hotstart= 0
Write HDF5 File= 1
Write Binary Output= 1
Write DSS Sediment File= 0
DSS Sediment Output Type= 1
SV Curve= 0
Specific Gage Flag= 0
Subcell Erosion Methods= 0
Subcell Deposition Methods= 0
Advection Scheme= 1
Matrix Solver= 0
Implicit Weighting Factor= 1
Maximum Outer Loop Convergence Iterations= 5
Convergence Maximum Absolute= 0.001
Convergence RMSE= 0.0001
Grain Fractions Max Abs Error= 0.001
Max Subgrid Regions= 1
Max Subgrid Length Scale= 3.402823E+38
Initial Layer Thickness= 3
Min Layer Thickness= 0.1
Max Layer Thickness= 6
Number of Layers= 5

--- FshCrk.f01 (steady flow) ---

Flow Title=Flow
Program Version=6.60
Number of Profiles= 1
Profile Names=P100yr
River Rch & RM=FshCrk,Main,137849
    9920
River Rch & RM=FshCrk,Main,105902
   13600
River Rch & RM=FshCrk,Main,90818
   15200
River Rch & RM=FshCrk,Main,52152
   17400
Boundary for River Rch & Prof#=FshCrk,Main            , 1
Up Type= 0
Dn Type= 1
Dn Known WS=644
DSS Import GetInterval= 0
DSS Import GetPeak= 0
DSS Import FillOption= 0

--- FshCrk.g01 (geometry) ---

Geom Title=Geometry
Program Version=6.60

River Reach=FshCrk          ,Main
Reach XY= 30
     1666630.542      446628.978     1665595.164      448172.373
     1663389.371      445250.597     1662145.833      447909.722
     1664806.945        453387.5     1662690.278        454912.5
     1659819.444      452109.722     1661049.098      458549.058
     1658078.889      457941.111       1656838.4        460147.2
     1654994.792      458190.972     1651899.306       463227.43
     1646705.247       462538.58     1646527.778      465410.397
     1641411.111      465828.889     1642140.445      468630.044
     1640689.236       462741.32     1636223.958      462800.347
     1635827.778      465306.667      1632946.18      465359.375
        1632140.      469945.555     1627552.626      462497.287
      1628834.93      467768.661      1624906.25      465972.222
        1625250.      470725.694     1621020.833      468571.181
     1621865.167      475273.132     1619749.599      475088.755
     1618677.775      471687.3171615975.85636511473390.112471268

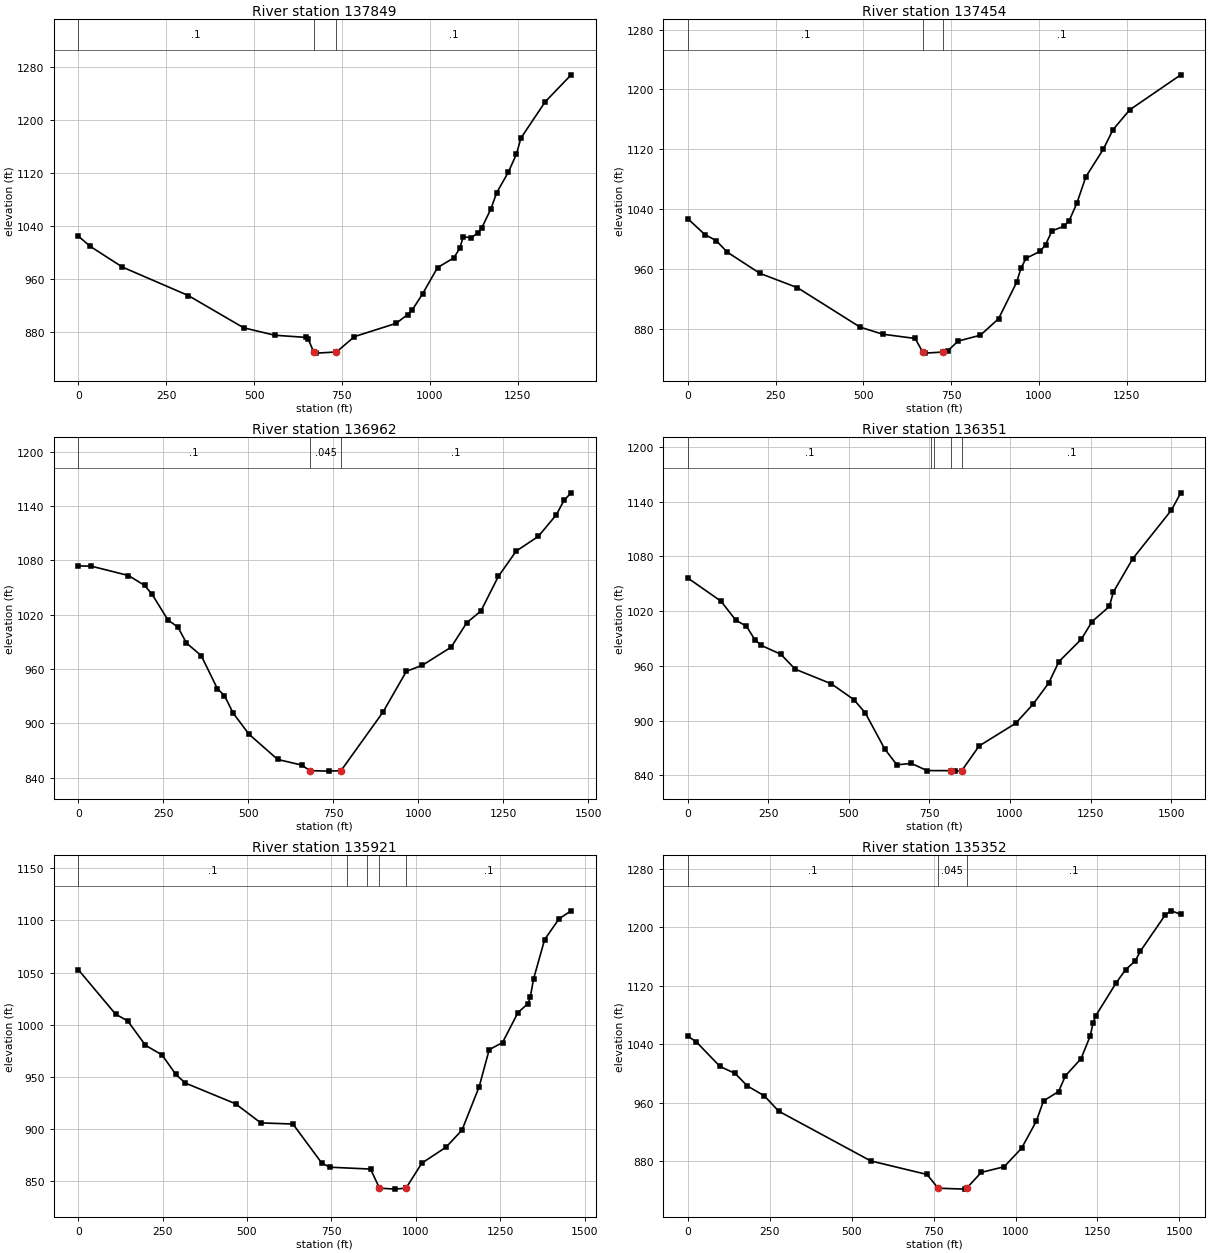
Type RM Length L Ch R = 1 ,137849  ,380.1,395.4,403.4
XS GIS Cut Line= 6
1665929.46459681446649.4938098941666226.86459255446647.392764226
1666580.24905638446640.7008484751666680.22064123  446643.0804369
1667032.88594639446666.5846549721667329.84893514446682.837903306
#Sta/Elev= 30
       0  1024.5    34.1 1008.92     126  977.46     313  934.54   470.5  885.72
   559.1  874.48   647.7  871.24   654.3  868.26   669.8849.1772   677.2  847.44
   734.5849.1591   785.6  872.45     904  892.43   936.9  905.83   950.1  912.78
   979.7  937.44  1021.9  976.81    1068  991.43  1084.9 1005.72  1094.7 1023.19
  1117.7 1022.03  1137.4 1029.45  1147.3 1036.46  1173.6 1065.45    1190 1090.04
  1222.9 1120.77  1245.9 1147.94    1259 1172.66    1328 1227.42  1401.7  1268.2
#Mann= 3 ,-1,0
       0      .1       0   669.8    .045       0   734.5      .1       0
Bank Sta=669.8,734.5
XS Rating Curve= 0 ,0
Exp/Cntr(USF)=0,0
Exp/Cntr=0.3,0.1

Type RM Length L Ch R = 1 ,137454  ,490.6,491.4,491.1
XS GIS Cut Line= 6
1665892.96824914446741.8810478431666652.24100882447065.575938506
1666730.09649615 447106.072576671666899.20672223447196.373577176
1666987.52773981447241.3104951811667167.09529406447329.438927842
#Sta/Elev= 30
       0 1027.26    48.3 1006.12    80.4   998.1   112.4  982.55   205.2  954.25
   312.2  935.07   490.5  882.37   554.9  872.89   647.4  867.19     669849.0118
   675.9  847.58   725.7848.9935     740  850.49   769.9  863.68   833.2  871.53
   884.9   893.5   936.4  942.11   948.8  960.84     963  974.29    1004  983.77
  1018.9  992.66  1037.4 1011.08  1070.1 1016.93  1085.7 1024.17  1107.9 1047.78
  1133.7 1083.36  1183.3 1120.07  1210.9 1146.21  1258.5 1172.78    1404  1219.6
#Mann= 3 ,-1,0
       0      .1       0     669    .045       0   725.7      .1       0
Bank Sta=669,725.7
XS Rating Curve= 0 ,0
Exp/Cntr(USF)=0,0
Exp/Cntr=0.3,0.1

Type RM Length L Ch R = 1 ,136962  ,597.5,611.9,624.6
XS GIS Cut Line= 6
1665758.96057655447085.6148491491665805.97459014447225.849148734
1665985.15959922447309.6337580671666073.39826788 447349.70749682
1666159.22552406447387.4561089861667000.57751589447741.709993644
#Sta/Elev= 30
       0 1073.98    38.8 1073.58   147.9 1063.28   195.3 1052.34   217.1 1042.63
   264.2 1013.98   293.1 1006.37   318.4  988.61   361.7  974.79   409.5  938.05
   430.1   930.6   455.3  911.41   501.9  888.01   586.4  860.04   656.6  853.87
   681.4847.6542   736.7  847.12   772.8  847.66   896.5  912.56   964.9  957.39
  1012.3  964.19  1096.6  984.14  1142.5 1011.14    1184 1024.01  1235.2 1062.22
  1287.8 1090.26    1353 1106.58  1406.3 1130.66  1428.1 1146.21  1449.3 1154.66
#Mann= 3 ,-1,0
       0      .1       0   681.4    .045       0   772.8      .1       0
Bank Sta=681.4,772.8
XS Rating Curve= 0 ,0
Exp/Cntr(USF)=0,0
Exp/Cntr=0.3,0.1

Type RM Length L Ch R = 1 ,136351  ,388.8,429.9,435.2
XS GIS Cut Line= 6
1665677.12028523447231.199011311 1665692.4493228447416.707170472
 1665718.8193488447549.8033609841665766.82220556447642.893397897
1665878.63070898 447797.352734641666431.49443264448523.789601982
#Sta/Elev= 30
       0  1056.3   102.8 1030.91   148.9 1010.07   181.8 1003.48   208.5  988.47
   228.6  982.34   288.8  972.64   333.3  956.37   445.5  940.29   515.4  922.96
   550.7  908.46   611.3   868.8     649  851.44   693.5  853.04   742.7  845.15
  816.72845.0816     828  844.56   850.4  845.09   904.2  872.15  1017.6  896.97
  1071.8     918  1120.5  941.28  1151.8  964.57  1221.9  989.38  1254.9 1008.59
  1308.5 1025.09  1320.9 1040.87  1380.6 1077.25  1501.2 1130.77  1530.2 1149.72
#Mann= 5 ,-1,0
       0      .1       0  754.78     .06       0  764.78      .1       0
  816.72    .045       0   850.4      .1       0
Bank Sta=816.72,850.4
XS Rating Curve= 0 ,0
Exp/Cntr(USF)=0,0
Exp/Cntr=0.3,0.1

Type RM Length L Ch R = 1 ,135921  ,520.5,569,582.7
XS GIS Cut Line= 3
1665663.07306921 447236.265930311665652.53814048447501.952141958
1665712.56635299448694.755001843
#Sta/Elev= 30
       0 1052.89   110.6 1010.13   146.7 1003.56   199.2  980.24   248.5  970.92
   289.4  952.18   317.5  943.96   466.1  924.12   540.8  905.75   636.1  904.67
     721  867.44   744.5  863.25   866.1  861.44  892.44 843.166   938.3   842.2
   971.2  843.16   971.2  843.17  1018.1  867.18  1090.1  882.56    1137  898.88
    1188  940.65  1217.5     976    1257  982.84  1302.7 1011.57  1332.5 1020.26
  1339.1 1026.09  1348.9 1043.86  1381.8 1081.67  1424.5 1101.59  1460.2 1109.21
#Mann= 5 ,-1,0
       0      .1       0  795.89     .06       0  855.89      .1       0
  892.44    .045       0   971.2      .1       0
Bank Sta=892.44,971.2
XS Rating Curve= 0 ,0
Exp/Cntr(USF)=0,0
Exp/Cntr=0.3,0.1

Type RM Length L Ch R = 1 ,135352  ,339.3,354.2,371.2
XS GIS Cut Line= 6
1665644.56129523447222.670156971 1665627.3313428  447399.6497899
1665588.58306073 447515.688599811665448.93701455447653.678481311
 1665270.4363873447839.154160231 1664804.0396823448427.002065897
#Sta/Elev= 30
       0 1050.86    25.8 1043.13    98.3 1009.47   144.5  999.95   181.4  982.93
   233.3  969.45   277.3  948.43   558.1  880.46   729.9  861.92     764 843.157
   845.2   841.9   850.9  843.17   895.3  864.72   965.4  872.48  1018.6  897.89
  1063.5  934.72  1085.4  962.49  1131.3  975.16  1152.4  996.77    1200 1020.18
  1227.5 1050.67    1237  1069.4  1244.2  1078.3  1306.9 1123.56  1336.1 1141.96
  1365.4 1153.66  1381.2 1167.17  1457.3  1216.8  1475.5 1222.19  1504.3 1217.39
#Mann= 3 ,-1,0
       0      .1       0     764    .045       0   850.9      .1       0
Bank Sta=764,850.9
XS Rating Curve= 0 ,0
Exp/Cntr(USF)=0,0
Exp/Cntr=0.3,0.1

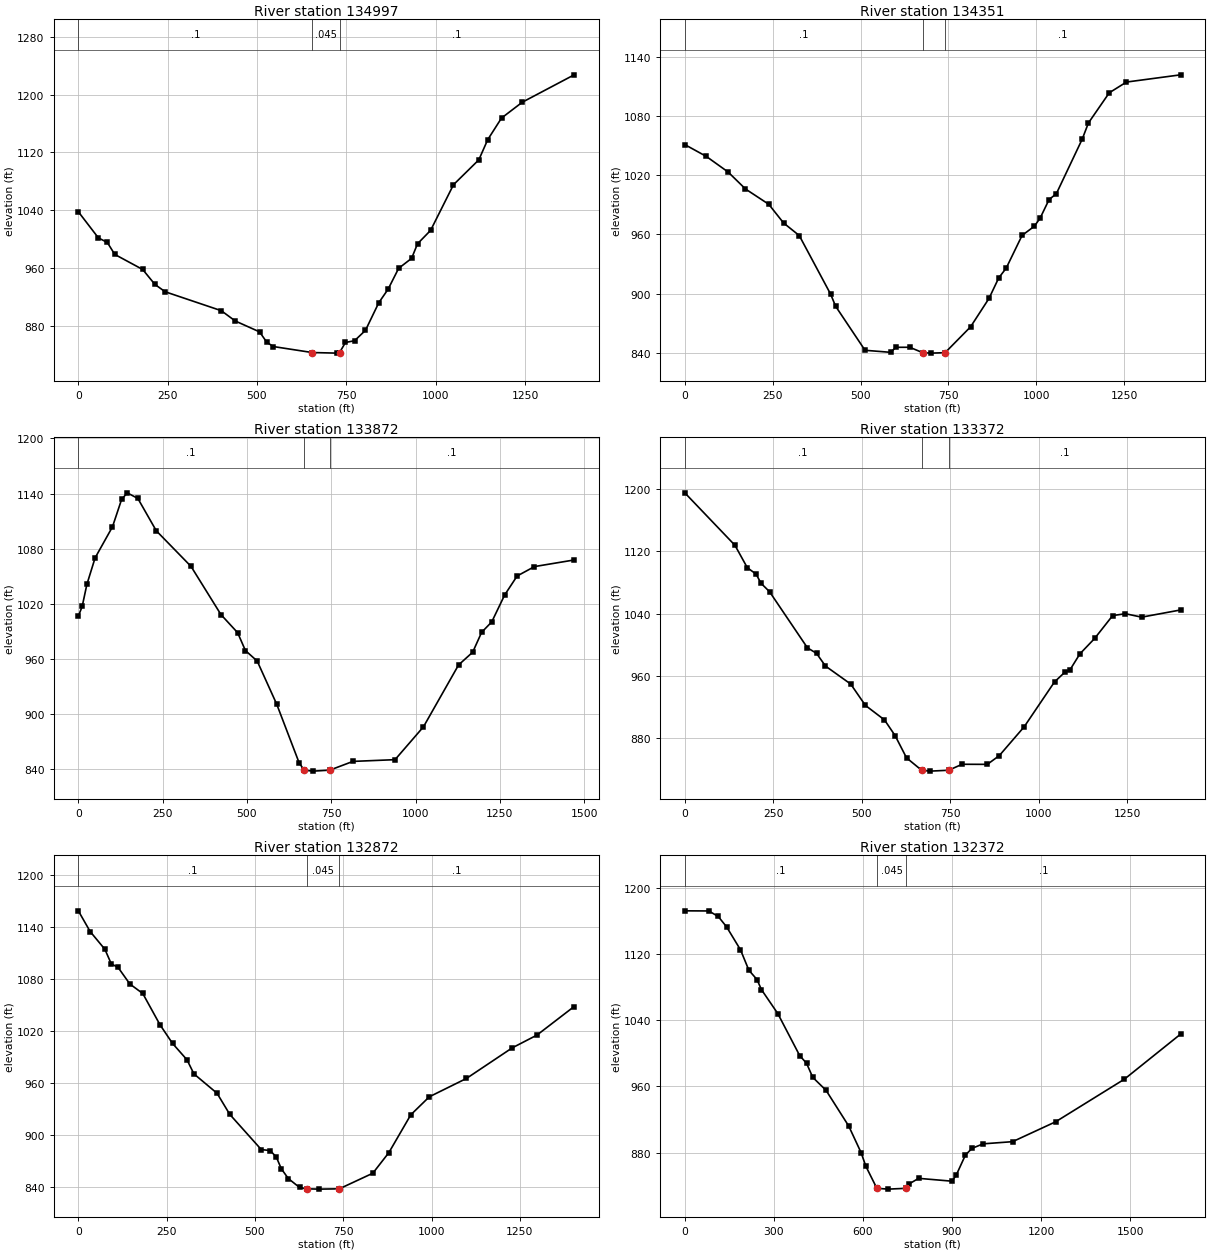
Type RM Length L Ch R = 1 ,134997  ,641.4,646.9,651.2
XS GIS Cut Line= 6
1665618.65227567447235.4622989021665564.11444296447302.126377793
1664766.80501395447734.5658016221664595.11867754447827.682741377
1664506.51452404447872.4274025431664416.18104328447914.941097039
#Sta/Elev= 30
       0 1037.94    56.2 1001.69    81.1  995.44   101.9  978.88   180.1  957.98
   214.2  937.37     243  927.13     400  900.95     439  886.73   507.2  871.59
   527.4  857.25   545.5  851.29   654.6842.9758   723.4  842.17   731.1842.9857
   747.6  856.94     773  859.33   803.6  873.74   840.9  912.04     867  930.77
   896.4  959.59   932.7  973.42   949.2  993.56   985.9 1012.18  1049.9 1075.37
  1120.8 1109.83  1145.6 1137.66  1184.3 1167.67  1242.4 1189.59  1387.6 1227.53
#Mann= 3 ,-1,0
       0      .1       0   654.6    .045       0   731.1      .1       0
Bank Sta=654.6,731.1
XS Rating Curve= 0 ,0
Exp/Cntr(USF)=0,0
Exp/Cntr=0.3,0.1

Type RM Length L Ch R = 1 ,134351  ,486.1,478.8,459
XS GIS Cut Line= 6
 1665440.0521898446842.7473603931665336.68133356446851.566568479
1665234.54767956446861.0324288161665135.18567355446875.832924142
1665042.38041297446904.0927101371664096.35441789447248.127127066
#Sta/Elev= 30
       0 1050.91    60.8 1039.03   123.2 1023.16   172.6    1006   238.8  990.52
   280.9  971.64   325.6  958.86     415  899.46   428.9  887.42   512.7  842.81
     586  840.73     600  845.82   639.7  845.87   676.8840.4014   701.2  839.94
   740.5840.4078     813  866.59   865.3  895.29   893.1   916.1   914.2  925.88
   959.4  959.02   994.5  968.36  1010.9  976.61  1036.2   995.3  1056.9 1001.21
  1130.6 1056.53  1148.1 1072.76  1207.4 1103.31  1256.3 1114.16  1410.4 1121.48
#Mann= 3 ,-1,0
       0      .1       0   676.8    .045       0   740.5      .1       0
Bank Sta=676.8,740.5
XS Rating Curve= 0 ,0
Exp/Cntr(USF)=0,0
Exp/Cntr=0.3,0.1

Type RM Length L Ch R = 1 ,133872  ,507.8,500,488.3
XS GIS Cut Line= 6
1665241.83900355446116.953536391 1665084.4131373446238.401784316
1665006.47333255446298.5292887241664929.77073005446357.702726811
1664647.70272464446575.3072784841664059.82506197446990.961984842
#Sta/Elev= 30
       0 1006.46    11.4 1017.12    25.4 1041.13    49.7 1069.96   101.3 1103.83
   128.3 1133.59     145 1140.79   176.5 1134.67   231.2 1099.46   334.2 1060.69
     423 1008.21   472.4  988.54   495.5  969.09   530.4  957.66   588.4  910.59
   654.6  847.06   669.5838.9003   696.7  837.82   745.7838.8906   814.3  848.41
   939.2   850.3  1023.6  886.12  1127.7  953.45  1169.5  967.31    1196  988.93
    1226 1000.28  1264.3 1029.58  1301.3 1050.25  1352.7  1060.5  1470.4  1067.7
#Mann= 3 ,-1,0
       0      .1       0   669.5    .045       0   745.7      .1       0
Bank Sta=669.5,745.7
XS Rating Curve= 0 ,0
Exp/Cntr(USF)=0,0
Exp/Cntr=0.3,0.1

Type RM Length L Ch R = 1 ,133372  ,507.2,500,498.1
XS GIS Cut Line= 6
1664782.01183923445650.1280264711664715.27608031445724.423153475
1664649.44812797445798.9285818931664585.43677305 445873.85461314
1664525.05828489445949.6225062311663907.87185521446744.862057477
#Sta/Elev= 30
       0 1195.12   141.7 1127.72   176.7  1098.9   201.5 1090.66   215.6  1078.8
   239.4 1068.14   346.6  995.95   372.3  988.85   397.5  972.55   468.9  949.38
   510.4  921.98   564.4   903.3   594.4  883.14   626.7  854.55   669.4838.6245
   693.1  837.48   745.8838.6082   783.8   846.3   855.1  846.17     889  857.47
   959.4  894.57    1045  952.18    1076  965.36  1087.8  966.97  1116.7  988.16
  1158.3 1007.95  1209.3 1037.38  1245.5 1039.76  1291.2 1035.34  1401.4 1044.61
#Mann= 3 ,-1,0
       0      .1       0   669.4    .045       0   745.8      .1       0
Bank Sta=669.4,745.8
XS Rating Curve= 0 ,0
Exp/Cntr(USF)=0,0
Exp/Cntr=0.3,0.1

Type RM Length L Ch R = 1 ,132872  ,478.9,500,512.2
XS GIS Cut Line= 6
1664390.65140148445276.938812226 1664322.2178113445350.977049977
1664259.33604731445428.2692182211663755.30884014 446179.54527472
1663645.18766931446343.6837259831663589.50569406446427.790841222
#Sta/Elev= 30
       0 1158.43    33.5 1134.52    75.2 1114.04    93.3 1097.24   112.5 1093.15
     146 1073.98   182.4 1063.08   231.1 1027.06   266.7 1005.47   307.6  986.59
   327.3  970.32   392.7  947.99   428.7  923.65     518  883.01   543.3  881.91
   560.6  874.29   574.7  860.86   594.6  849.57   626.2  839.35   646.2837.7502
   681.5  837.41   738.8837.7482   833.7  855.76   879.1  879.51   941.2  923.13
   993.6  943.91  1098.7  965.06  1228.2 1000.32  1298.3 1015.07  1403.7 1048.06
#Mann= 3 ,-1,0
       0      .1       0   646.2    .045       0   738.8      .1       0
Bank Sta=646.2,738.8
XS Rating Curve= 0 ,0
Exp/Cntr(USF)=0,0
Exp/Cntr=0.3,0.1

Type RM Length L Ch R = 1 ,132372  ,567,500,428
XS GIS Cut Line= 6
1664235.59232838445053.0960840581663586.82569564445523.813570341
1663456.92123457445730.7486465081663437.28093289446013.528874472
1663459.47216147446184.0925097321663496.64794014446347.995397151
#Sta/Elev= 30
       0  1172.4    80.9 1172.24   112.6 1165.54   140.6 1153.08   187.5 1125.26
   215.8 1100.51     243 1089.33   258.1 1077.08     313 1048.21   386.8  997.35
   409.8  988.09   430.9  970.98   475.6  955.31     552  912.09   593.8  879.77
   609.5  863.56   646.6  836.84   684.7  835.84     746  836.84   755.1  842.12
   787.4  848.88   899.6  845.44   913.9  852.78   944.8  877.03   966.7  885.09
  1004.3   890.6  1103.7  893.24  1248.4  917.24  1479.9  968.75  1669.4 1023.32
#Mann= 3 ,-1,0
       0      .1       0   646.6    .045       0     746      .1       0
Bank Sta=646.6,746
XS Rating Curve= 0 ,0
Exp/Cntr(USF)=0,0
Exp/Cntr=0.3,0.1

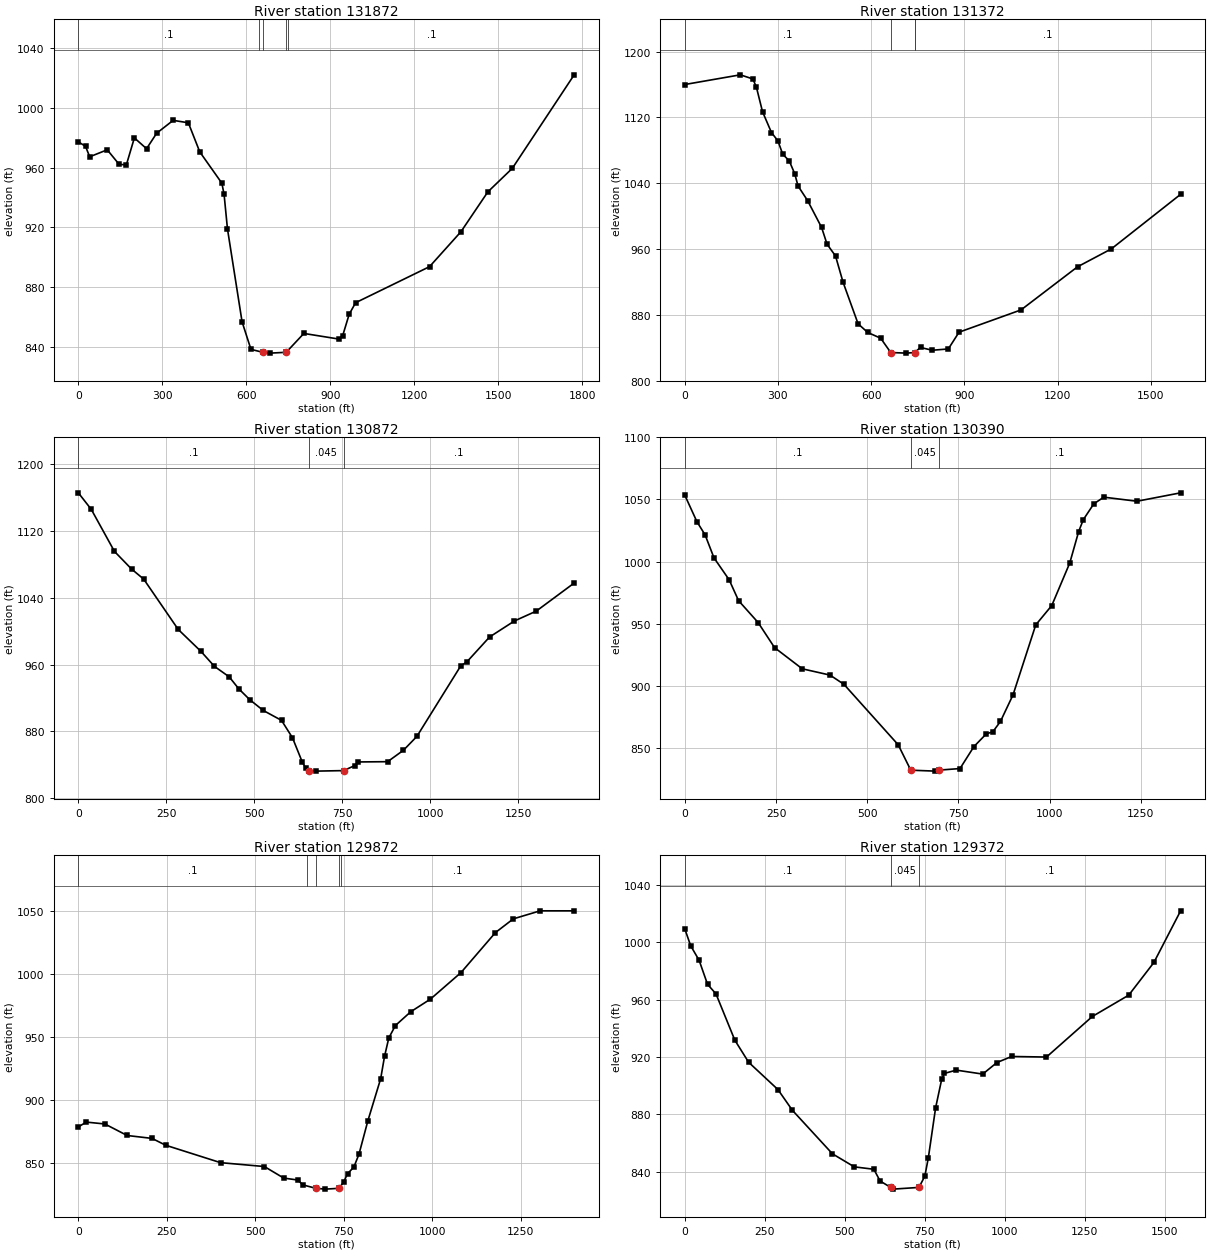
Type RM Length L Ch R = 1 ,131872  ,524.2,500,473.2
XS GIS Cut Line= 6
1662866.14034289444739.4067508131663341.39464173445414.242671475
1663368.61210696445508.5466167331663421.34625347446003.552844554
1663451.50498581446179.104658812 1663492.6643523446345.501307637
#Sta/Elev= 30
       0  977.36    25.6  974.38    40.6  967.33   103.2  972.02   145.6  962.28
   171.5  961.86   200.1  980.01   243.7  972.75   279.8  983.15   338.7  991.78
   392.9  990.15   433.7  970.63   512.6  949.63   520.6  942.06   532.6  918.99
   584.8   856.6   616.5  838.09   659.2836.1287   685.1  835.57   742.4 836.123
   805.5  848.78   931.1     845   944.3  847.36   967.4  861.68   990.4  869.41
  1254.4   893.6  1366.6  917.05  1462.7   943.8  1550.1  959.59  1770.9 1022.33
#Mann= 5 ,-1,0
       0      .1       0  645.39     .08       0   659.2    .045       0
   742.4     .08       0  750.39      .1       0
Bank Sta=659.2,742.4
XS Rating Curve= 0 ,0
Exp/Cntr(USF)=0,0
Exp/Cntr=0.3,0.1

Type RM Length L Ch R = 1 ,131372  ,500.3,500,499.3
XS GIS Cut Line= 6
1662324.06006221445492.4062290641663279.08374272445810.611629397
1663349.72303714 445903.15475139 1663395.8161208446046.781760722
1663438.73991947446200.7191168961663486.28181913446356.308372647
#Sta/Elev= 30
       0 1159.88   178.7 1171.65   219.1 1166.64   230.6 1156.57   250.2 1126.86
     279 1101.54   299.8 1091.35   315.3 1075.13   336.1 1067.19   353.9 1051.49
   364.6 1036.58   395.4 1018.75   440.4   986.2     458  965.81   485.3  951.45
   509.5  919.61     558  868.97   589.1  858.46   630.6  851.51   663.1  834.11
   713.6  833.37   739.8834.1106   758.9  840.26   796.6  836.86   848.4  838.45
     883  858.82  1082.7  885.94  1264.4  938.29  1373.5  960.11  1596.4 1026.41
#Mann= 4 ,-1,0
       0      .1       0   663.1    .045       0   739.8     .08       0
  740.39      .1       0
Bank Sta=663.1,739.8
XS Rating Curve= 0 ,0
Exp/Cntr(USF)=0,0
Exp/Cntr=0.3,0.1

Type RM Length L Ch R = 1 ,130872  ,481.7,482.2,482.2
XS GIS Cut Line= 6
 1662139.4524918445952.0398242321662684.28440739446137.060451567
1662921.00703105446217.4497264771663092.63070355 446275.73209022
1663371.51958147446370.4405622331663452.67165014446441.169423386
#Sta/Elev= 30
       0 1165.27    36.8 1145.47   102.6 1095.26   151.1 1074.22   185.8 1062.08
   283.8 1001.96   348.5  975.69   386.7  957.82   428.7  945.27     456  930.91
   487.2  917.94   525.3  905.15   577.3  893.27   608.5  872.44   636.2  843.53
   646.6  835.88   654.8833.2123   674.3  832.59   753.7  833.22   785.2  839.16
   795.9  843.57   878.8  843.88   923.8  857.56   961.9  874.07  1086.6  958.42
  1103.7  963.07  1168.4  992.91  1239.1 1012.08  1301.2 1023.89  1408.8 1057.42
#Mann= 3 ,-1,0
       0      .1       0   654.8    .045       0   753.7      .1       0
Bank Sta=654.8,753.7
XS Rating Curve= 0 ,0
Exp/Cntr(USF)=0,0
Exp/Cntr=0.3,0.1

Type RM Length L Ch R = 1 ,130390  ,516.1,517.8,521.7
XS GIS Cut Line= 2
1662029.70685679 446422.266259871663318.48996927446852.721752807
#Sta/Elev= 30
       0 1053.49    33.3 1032.08    55.6 1021.53      80 1003.01   121.5  985.38
   147.4  968.54   200.9  950.95     246  930.74   321.9  913.68     398  908.62
   436.1   901.2   584.8  852.51   619.3  832.05   686.8   831.3695.5208832.0846
   754.2  833.37   792.3  851.04   826.3  861.31   844.2  862.99     865  871.28
   899.6  892.77   961.8  949.05  1005.7  964.63    1055  998.89  1079.4 1024.22
  1092.1 1033.77  1120.9 1046.51  1148.3 1051.88  1239.1 1048.59  1358.8 1055.37
#Mann= 3 ,-1,0
       0      .1       0   619.3    .045       0695.5208      .1       0
Bank Sta=619.3,695.5208
XS Rating Curve= 0 ,0
Exp/Cntr(USF)=0,0
Exp/Cntr=0.3,0.1

Type RM Length L Ch R = 1 ,129872  ,495.9,500,503.2
XS GIS Cut Line= 6
1661893.95856021446862.8381994811661987.66998698446897.403419063
1662080.67931539446932.5677188041662172.28444713446968.930178896
1662261.08085747447007.6896158161663177.18105939447424.925001815
#Sta/Elev= 30
       0  878.37    22.5   882.2      75  880.71     138  871.54   208.3  869.23
   246.8   863.8   401.9  849.93   525.8  846.84   580.6  837.64   620.2  836.11
   634.7  832.24   671.2829.5168   698.3  828.86   736.9829.5086     750  834.55
   760.8  841.07   778.9  846.47   793.3  856.75   818.5  883.39   854.6  916.82
   865.4  934.47   877.5  949.16   896.2  959.05   939.4  969.99   995.2  980.08
  1081.7 1001.23    1179 1033.05  1229.5 1043.95  1305.2 1050.33  1401.4 1050.32
#Mann= 5 ,-1,0
       0      .1       0  646.01     .08       0   671.2    .045       0
   736.9     .08       0  741.01      .1       0
Bank Sta=671.2,736.9
XS Rating Curve= 0 ,0
Exp/Cntr(USF)=0,0
Exp/Cntr=0.3,0.1

Type RM Length L Ch R = 1 ,129372  ,550.3,500,450.5
XS GIS Cut Line= 6
1661712.04324163447231.6586560611662583.07069905447736.278053641
1662678.03277947447764.7839021381662805.67983389 447736.61958839
1662949.42396897447675.9517307281663091.72552164447608.193007976
#Sta/Elev= 30
       0 1009.47    18.4   997.7    44.8  987.55    71.1   970.8    97.5  964.13
   156.4  931.84   199.6  916.41   291.1  897.38   336.3  882.92   461.5  852.54
   529.9  843.42   591.1  841.74   610.6  833.54   643.9829.0684   651.3  827.88
     732829.0715   750.4  836.87   761.4  849.68   784.2  884.67   803.2  904.55
   811.5  908.62   848.7  910.93   931.5  908.16   975.8  916.21  1021.9  920.44
  1130.8  920.05  1274.1  948.35    1388  963.25  1466.6  986.04  1550.2 1022.09
#Mann= 3 ,-1,0
       0      .1       0   643.9    .045       0     732      .1       0
Bank Sta=643.9,732
XS Rating Curve= 0 ,0
Exp/Cntr(USF)=0,0
Exp/Cntr=0.3,0.1

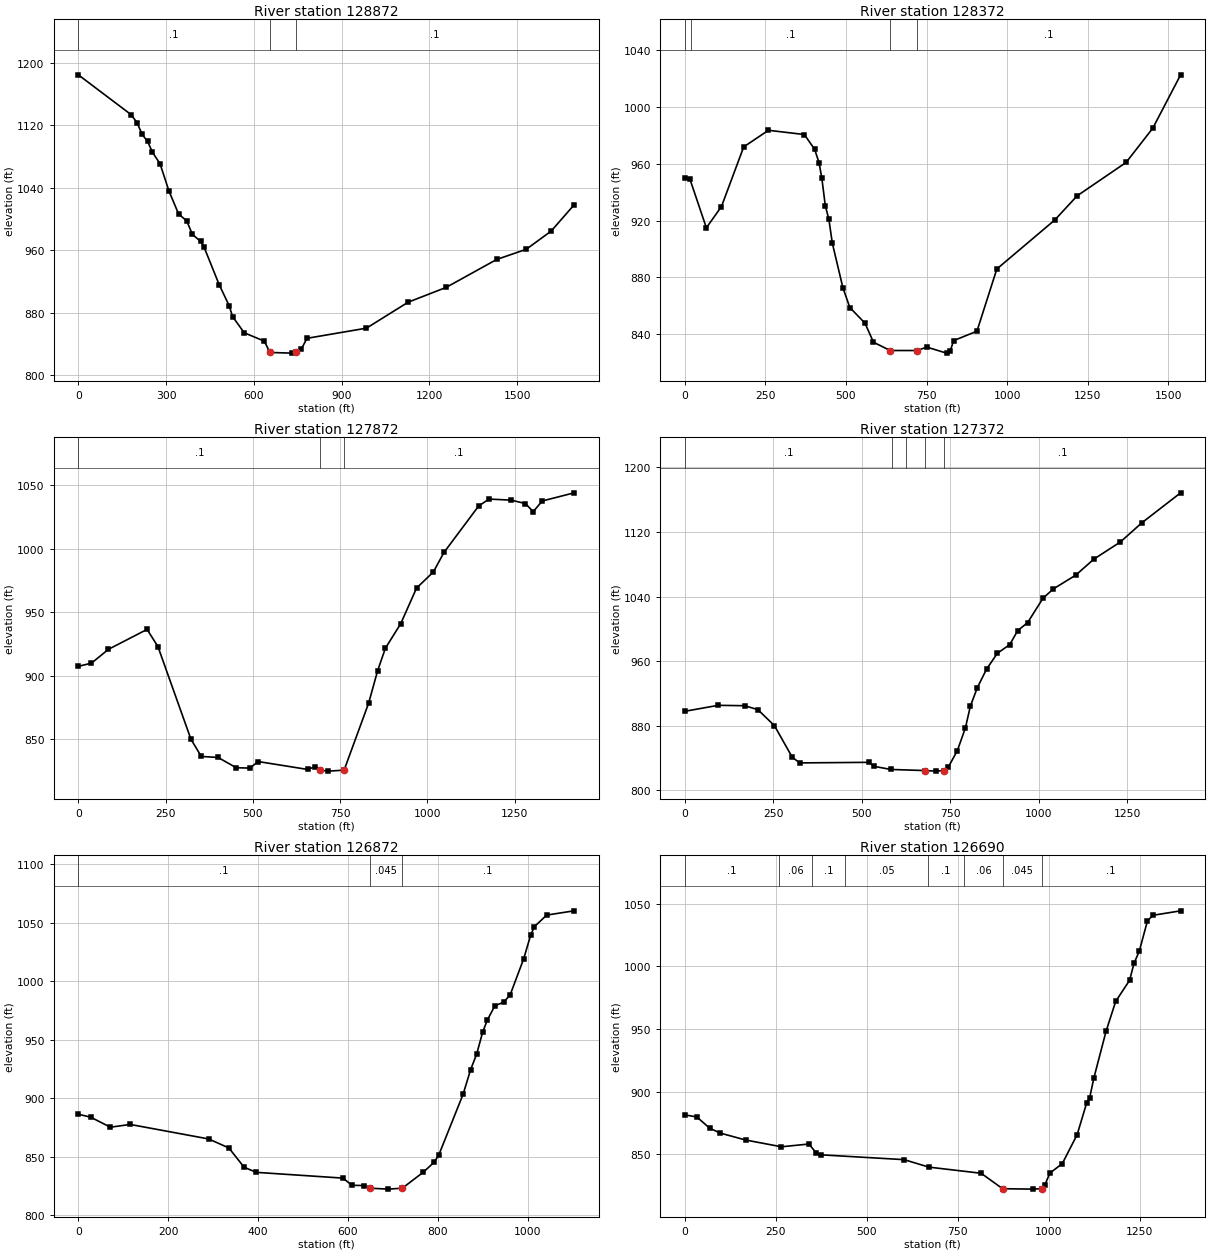
Type RM Length L Ch R = 1 ,128872  ,521.4,500,476.6
XS GIS Cut Line= 6
1661611.76719548448429.8130838871662290.63788497447960.317631811
1662390.04024522447920.5726325661662641.85995156447836.685989305
1662787.59325589447772.5706319811663087.20387714447617.180850893
#Sta/Elev= 30
       0 1184.65   180.4  1133.6   200.9 1123.22   218.1 1108.24   236.9  1099.2
   253.4 1085.36   279.3 1070.65   309.9 1035.59   342.9 1006.14   370.3  997.56
     390  980.07   418.3  971.04   430.1  963.51   481.2  915.84   515.6  888.75
     527  874.88     567  854.05   635.7  843.31   654.9828.7966   730.7  827.96
     743828.8046   762.7  833.52   781.5  846.94   984.8  859.96  1127.1  893.22
  1257.1  912.18  1429.9     948  1530.9  961.04    1616  984.32  1694.7 1018.08
#Mann= 3 ,-1,0
       0      .1       0   654.9    .045       0     743      .1       0
Bank Sta=654.9,743
XS Rating Curve= 0 ,0
Exp/Cntr(USF)=0,0
Exp/Cntr=0.3,0.1

Type RM Length L Ch R = 1 ,128372  ,509.7,499.9,508.5
XS GIS Cut Line= 6
1662313.36552981448903.4207324831662698.81718673448075.896796972
1662769.47944698447898.5208393931662851.40316764 447803.48789297
1662972.28579989447709.3860470651663103.15627305447624.910166144
#Sta/Elev= 30
       0   949.6    16.2  948.83    66.9  914.88   113.8  929.81   182.7  971.65
   259.5  983.32   370.9  980.34   402.7  970.01   416.5   960.6   425.2  949.64
     436  930.22   446.9  920.96   457.7  904.11   490.3  872.96     512  858.92
   559.1  847.91   585.4  834.54   637.2  828.75  720.28 828.732   750.9  831.13
   812.1  826.91   823.3  828.29   834.1  835.69   906.4  842.32   968.1  885.97
  1147.9  920.37  1217.2  937.31  1369.1  960.75  1451.9  984.78  1538.3 1022.25
#Mann= 4 ,-1,0
       0     .06       0      20      .1       0   637.2    .045       0
  720.28      .1       0
Bank Sta=637.2,720.28
XS Rating Curve= 0 ,0
Exp/Cntr(USF)=0,0
Exp/Cntr=0.3,0.1

Type RM Length L Ch R = 1 ,127872  ,490.2,500.1,514.6
XS GIS Cut Line= 6
1662831.61449331449016.2262811361662961.09487739 448625.49477914
1662992.75065397448534.7826902271663032.73745064448456.635536805
1663069.53265263448391.2567305561663421.77013713 447728.67439431
#Sta/Elev= 30
       0  907.41    37.6   909.9    86.2  920.77     197  936.44   228.1  922.94
   322.6  850.17   352.3  836.59   400.5  835.76   452.5  827.72   491.3  827.41
   515.5  832.55   656.8  826.37     679  828.48   693.2825.7789   716.5  825.03
   761.6 825.784   831.8  878.38   857.7  903.97     880  921.68     924     941
   969.2  968.92  1017.5  981.62  1047.7   996.9  1147.5 1033.55  1177.2  1038.9
  1240.4 1038.06  1281.3 1035.37  1303.5 1028.99  1329.5  1037.4  1420.9 1043.81
#Mann= 3 ,-1,0
       0      .1       0   693.2    .045       0   761.6      .1       0
Bank Sta=693.2,761.6
XS Rating Curve= 0 ,0
Exp/Cntr(USF)=0,0
Exp/Cntr=0.3,0.1

Type RM Length L Ch R = 1 ,127372  ,485.5,500,511.7
XS GIS Cut Line= 6
1662932.16678564 449103.572891221663086.84396972448978.642694891
1663379.78826572448742.0355565551663438.13362147448694.909994647
1663944.40393439448286.0010355561664021.89426497448223.412578061
#Sta/Elev= 30
       0  897.83    94.4  905.23   169.1  904.76   206.4  899.87   253.1  880.12
   303.6  840.86   324.7  833.87     519  834.57   535.1  829.58     582  825.75
   678.5824.3839   708.5  823.68   732.6824.3802     744  828.27   770.1  849.23
   792.8  877.27   806.6  903.94   826.6  927.29   852.6   950.1     883  969.71
     918  980.49   940.4  997.73   968.5 1007.75  1012.1 1038.03  1041.6 1049.61
  1104.9 1066.69  1155.5 1086.37  1230.6 1107.68  1291.2 1131.42  1400.8 1168.59
#Mann= 5 ,-1,0
       0      .1       0  585.39     .06       0  625.39      .1       0
   678.5    .045       0   732.6      .1       0
Bank Sta=678.5,732.6
XS Rating Curve= 0 ,0
Exp/Cntr(USF)=0,0
Exp/Cntr=0.3,0.1

Type RM Length L Ch R = 1 ,126872  ,194.2,181.6,168.1
XS GIS Cut Line= 6
1663010.50521164449279.8048222211663107.14051706449255.645749807
1663568.71603747449140.2522798031663641.47671872449122.062355563
1663987.09020072449035.6589850631664081.07262431449012.163625225
#Sta/Elev= 30
       0  886.33    27.4  883.82    71.4  875.24   115.4  877.61   290.3   865.2
   335.2  857.46     369  841.03   396.1   836.7   588.8  831.78   609.1  825.66
   636.2  825.41     649823.1613   690.3  822.37   721.1  823.17   768.1  836.93
   791.7  845.31   801.9   851.2   856.4  903.46   872.9  924.23   886.4  937.54
   899.9  956.42   910.1   966.6     927  978.92   947.3  982.11   961.3   988.5
   991.3 1019.19  1006.6 1039.13  1014.9 1046.46  1042.4 1056.38  1103.5 1060.01
#Mann= 3 ,-1,0
       0      .1       0     649    .045       0   721.1      .1       0
Bank Sta=649,721.1
XS Rating Curve= 0 ,0
Exp/Cntr(USF)=0,0
Exp/Cntr=0.3,0.1

Type RM Length L Ch R = 1 ,126690  ,316.3,318.4,317.8
XS GIS Cut Line= 3
1662857.30979629449504.7712761091663393.89493296449477.533451913
1664110.24970932449068.966088969
#Sta/Elev= 30
       0  881.54    33.1  879.84    68.4  870.88    97.9  866.95   166.9  861.48
   265.5  856.06     341  858.27   360.7  851.31   373.8  849.65   602.5   845.8
   670.4  839.84     814  834.93  873.01822.6167   957.4  822.28   980.1  822.69
   988.8  825.43  1002.8  835.06  1036.9   842.6  1077.8  865.79  1104.2  891.32
  1112.3  895.28  1123.7  910.98  1157.1  948.14  1183.6  972.05  1221.9  988.93
  1234.1 1002.64  1248.3 1011.97    1271 1036.45  1286.1 1040.76    1362 1044.32
#Mann= 8 ,-1,0
       0      .1       0     260     .06       0     350      .1       0
     440     .05       0  667.28      .1       0  767.28     .06       0
  873.01    .045       0   980.1      .1       0
Bank Sta=873.01,980.1
XS Rating Curve= 0 ,0
Exp/Cntr(USF)=0,0
Exp/Cntr=0.3,0.1

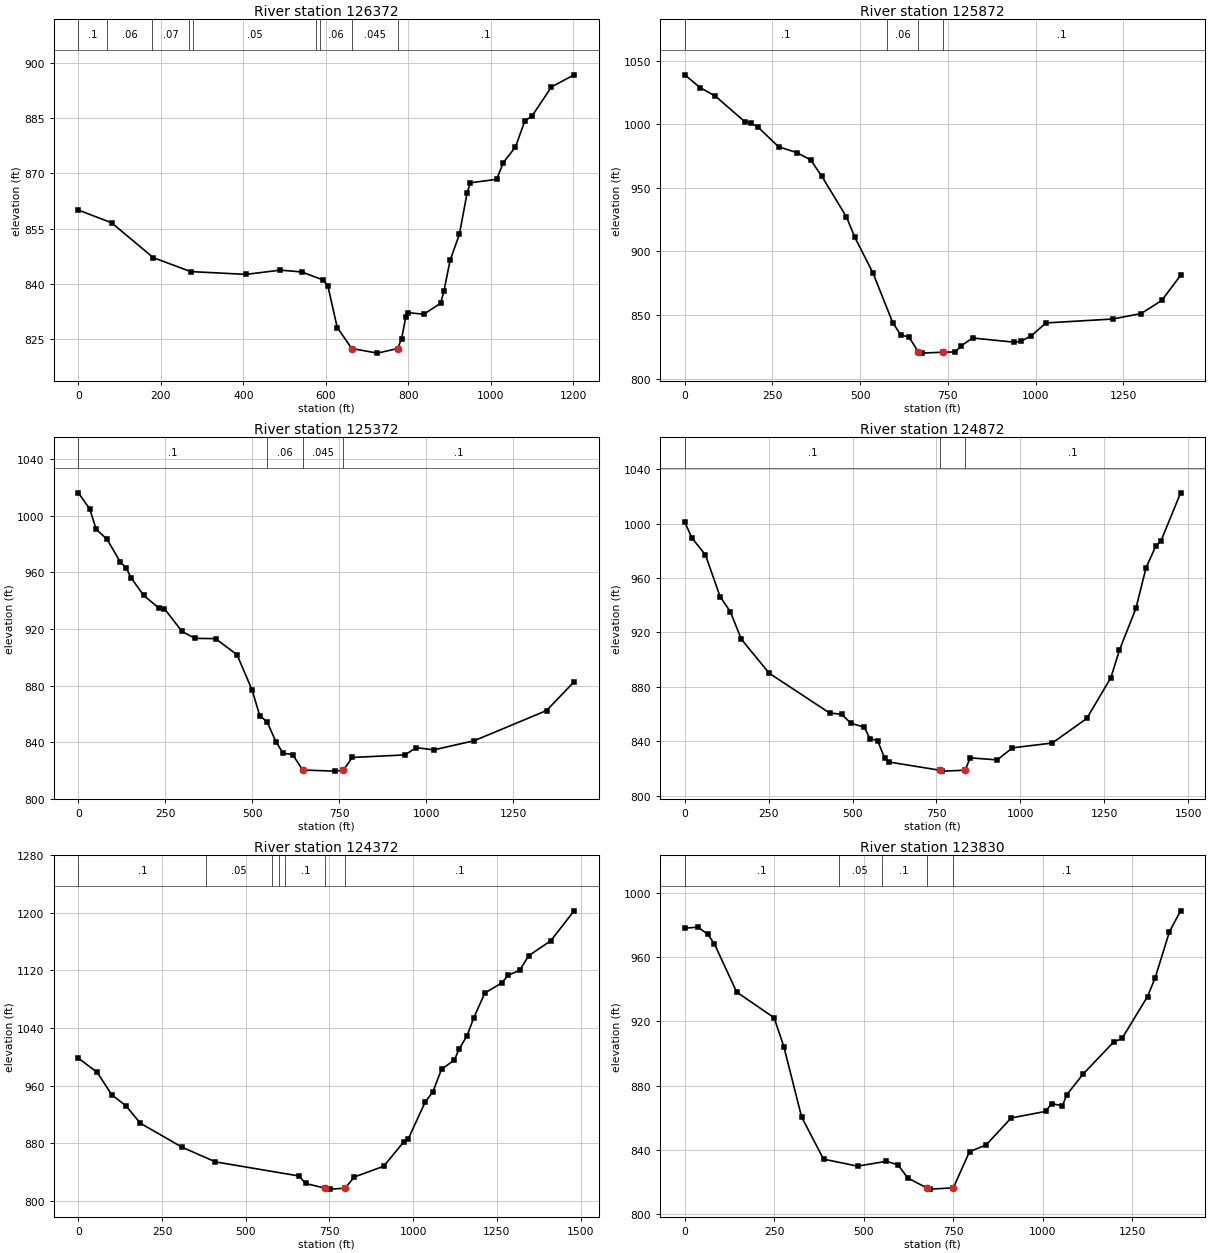
Type RM Length L Ch R = 1 ,126372  ,509.8,500,488.5
XS GIS Cut Line= 6
1663232.32957114449919.2133203151663736.12876038449641.254886732
1664031.63637146449478.216826975 1664113.2024813449431.986932561
1664197.08157864 449383.48079598 1664282.1174978449333.836538315
#Sta/Elev= 30
       0  860.02    80.6  856.56   181.7   847.1   272.3  843.32   406.6  842.56
   489.6  843.71   541.5  843.22   593.9  841.03   605.2  839.31   627.6  828.14
  662.82822.4432   725.1  821.19   773.8  822.43   783.8  825.11   793.5  830.86
   798.3  832.18   837.5  831.75     878   834.7   886.2  837.93   901.2  846.35
   923.8  853.44   942.6  864.73   950.6  867.41  1014.3  868.36  1030.1  872.87
  1059.7  877.12  1082.5  884.24  1099.3  885.44    1147  893.43    1202  896.71
#Mann= 9 ,-1,0
       0      .1       0      70     .06       0  179.61     .07       0
  268.83     .06       0  278.83     .05       0  575.39      .1       0
  585.39     .06       0  662.82    .045       0   773.8      .1       0
Bank Sta=662.82,773.8
XS Rating Curve= 0 ,0
Exp/Cntr(USF)=0,0
Exp/Cntr=0.3,0.1

Type RM Length L Ch R = 1 ,125872  ,521,500,485.5
XS GIS Cut Line= 6
1663623.67524514450504.0002084821664147.69158556449966.884812891
1664202.32533455449915.405257061 1664269.5761843449858.772168234
1664340.22499314449794.4681629841664628.08498172449510.091435149
#Sta/Elev= 30
       0  1038.9    43.3  1028.9    87.1 1022.16   170.7 1002.14     189 1000.97
   209.7   997.5   267.4  982.28   320.5  977.61   359.1  971.91     391  958.93
   460.7  927.21   484.9     911   536.6  882.92   592.8  843.98   615.7  834.26
   639.3  832.57   666.2  820.74   675.3  819.97  736.05820.7137   770.7  820.84
   788.7  825.84   820.3  831.88     939  828.57   957.5  829.24   987.7  833.52
  1029.5  843.72  1219.8  846.79    1301  851.09  1359.8  861.42  1413.6  881.18
#Mann= 4 ,-1,0
       0      .1       0  575.39     .06       0   666.2    .045       0
  736.05      .1       0
Bank Sta=666.2,736.05
XS Rating Curve= 0 ,0
Exp/Cntr(USF)=0,0
Exp/Cntr=0.3,0.1

Type RM Length L Ch R = 1 ,125372  ,471.3,499.9,519.9
XS GIS Cut Line= 6
1664171.06194563450854.3804132341664274.28221163450792.516035646
1664377.58876355450621.1269427241664421.51387255450534.404347137
 1664495.4576223450368.805596977 1664805.8192063449603.988228977
#Sta/Elev= 30
       0 1016.24    32.8 1004.84    51.2   990.5    82.5  983.44   120.3  967.39
   137.4  963.16   151.7  956.19   187.4  943.79   231.1  934.88   247.1  934.41
   297.9  918.28   335.3  913.37   394.2   913.2   456.1  901.75   499.5  876.67
   521.1  858.82   542.5  854.27   567.5  840.43   588.2  832.23   615.8  831.24
   644.4  820.33   737.6  819.55   761.8820.3227     787  829.21   938.2     831
   970.9  836.16  1020.9  834.57  1137.7  841.07  1345.1  862.35  1424.5  882.73
#Mann= 4 ,-1,0
       0      .1       0  541.58     .06       0   644.4    .045       0
   761.8      .1       0
Bank Sta=644.4,761.8
XS Rating Curve= 0 ,0
Exp/Cntr(USF)=0,0
Exp/Cntr=0.3,0.1

Type RM Length L Ch R = 1 ,124872  ,462.2,500.1,545.9
XS GIS Cut Line= 6
1664203.87913722 450887.82916522 1664459.3553323450841.067447722
1664565.86528988  450814.79453441664656.72271971450772.147966146
 1664866.3997938 450623.197476641665438.70704813 450137.86183314
#Sta/Elev= 30
       0 1000.97    21.4  989.34    61.6  976.95   105.1   946.3   135.8  935.15
   168.5  914.95   251.5  889.94   431.4  860.72   467.5  859.76   495.2  853.09
   535.2  850.25   551.2  841.87   574.6  840.43   595.3  827.59   607.5  824.69
     760818.5933   766.9  817.95   834.9  818.59   850.7  827.69     931  826.22
   976.4  835.08  1095.1  838.62  1197.8  856.67  1269.7  886.71  1295.3  907.04
  1344.2  937.56  1374.4  967.47  1404.3  983.86  1418.7  987.09  1477.5 1022.61
#Mann= 3 ,-1,0
       0      .1       0     760    .045       0   834.9      .1       0
Bank Sta=760,834.9
XS Rating Curve= 0 ,0
Exp/Cntr(USF)=0,0
Exp/Cntr=0.3,0.1

Type RM Length L Ch R = 1 ,124372  ,531.6,542.1,560.7
XS GIS Cut Line= 6
1664205.04448922450895.8406321411664342.24762689450875.436473474
1664464.01674031450873.1136434821664575.18876205450878.886597812
1664675.36933596450900.3320929711665538.60645464451418.164718732
#Sta/Elev= 30
       0  998.18    56.4  978.39    99.6  947.33   142.6  931.68   185.3  907.69
     310  874.32   409.4     854   659.5  834.36   678.6  824.01     738 817.332
   751.4  816.12   796.6817.3527   824.2  832.94   912.3  847.98   972.5  882.09
   985.3  885.63  1035.3  936.59  1059.2   951.7  1084.7  982.66    1123  995.57
  1138.1 1011.48  1161.3 1029.62  1180.4 1053.44  1214.1 1088.66  1264.7 1102.79
  1283.8 1113.37  1318.3 1120.24  1345.1 1140.52  1410.6  1161.1  1480.9 1202.89
#Mann= 7 ,-1,0
       0      .1       0  381.83     .05       0  578.05      .1       0
  598.05     .05       0  618.05      .1       0     738    .045       0
   796.6      .1       0
Bank Sta=738,796.6
XS Rating Curve= 0 ,0
Exp/Cntr(USF)=0,0
Exp/Cntr=0.3,0.1

Type RM Length L Ch R = 1 ,123830  ,99.9,101.1,105.5
XS GIS Cut Line= 5
1664160.83859014 450984.848224691664559.00621127 451402.48199069
1664748.10695927451664.9706591911664816.97351379451758.143056471
1665180.60796355451696.545127896
#Sta/Elev= 30
       0  977.86    36.7   978.5    64.1   974.1    82.6  968.14     145  938.16
   249.6  922.19     277  904.03   326.2  860.64   387.5  834.37   482.5  830.02
   563.4  833.01   595.7  830.81   622.6  822.71   675.7816.5117     685  815.73
   750.2816.5143   795.4  839.03   841.5  843.13   911.9  859.96  1008.1  864.02
  1024.7  868.91  1054.7  867.48  1067.5  874.51  1113.4  887.36  1197.7  907.03
  1221.6  909.38  1292.7  935.39  1314.2   947.1  1354.1  975.76  1385.2  988.64
#Mann= 5 ,-1,0
       0      .1       0     430     .05       0     550      .1       0
   675.7    .045       0   750.2      .1       0
Bank Sta=675.7,750.2
XS Rating Curve= 0 ,0
Exp/Cntr(USF)=0,0
Exp/Cntr=0.3,0.1