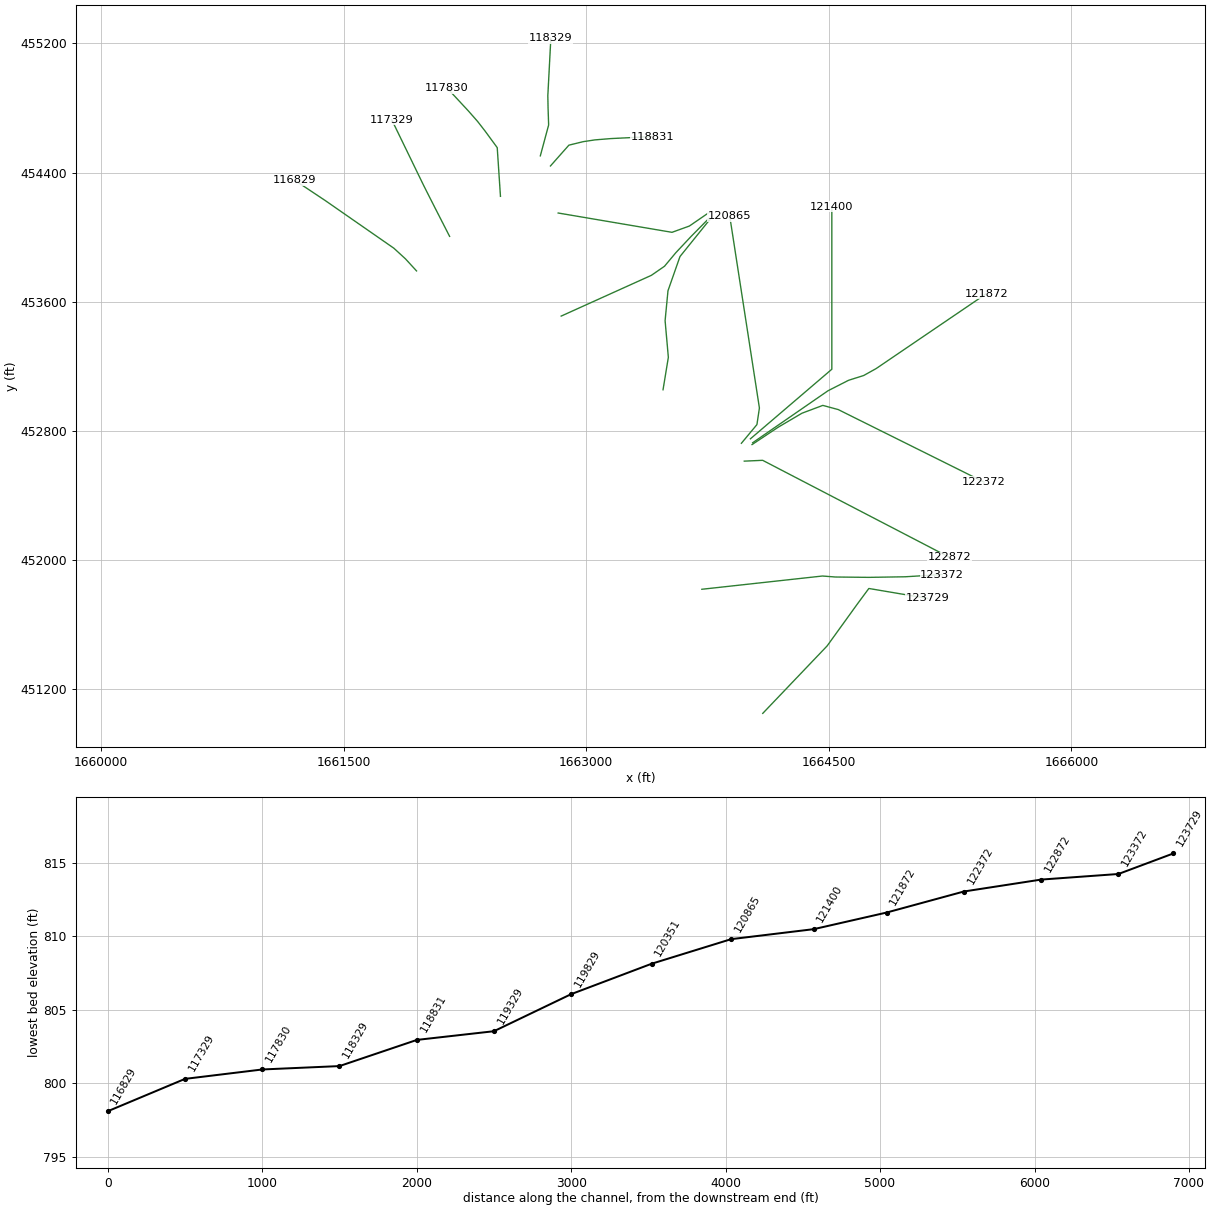
HEC-RAS study FshCrk.prj: FshCrk

--- FshCrk.g01 (geometry) --- (continued)

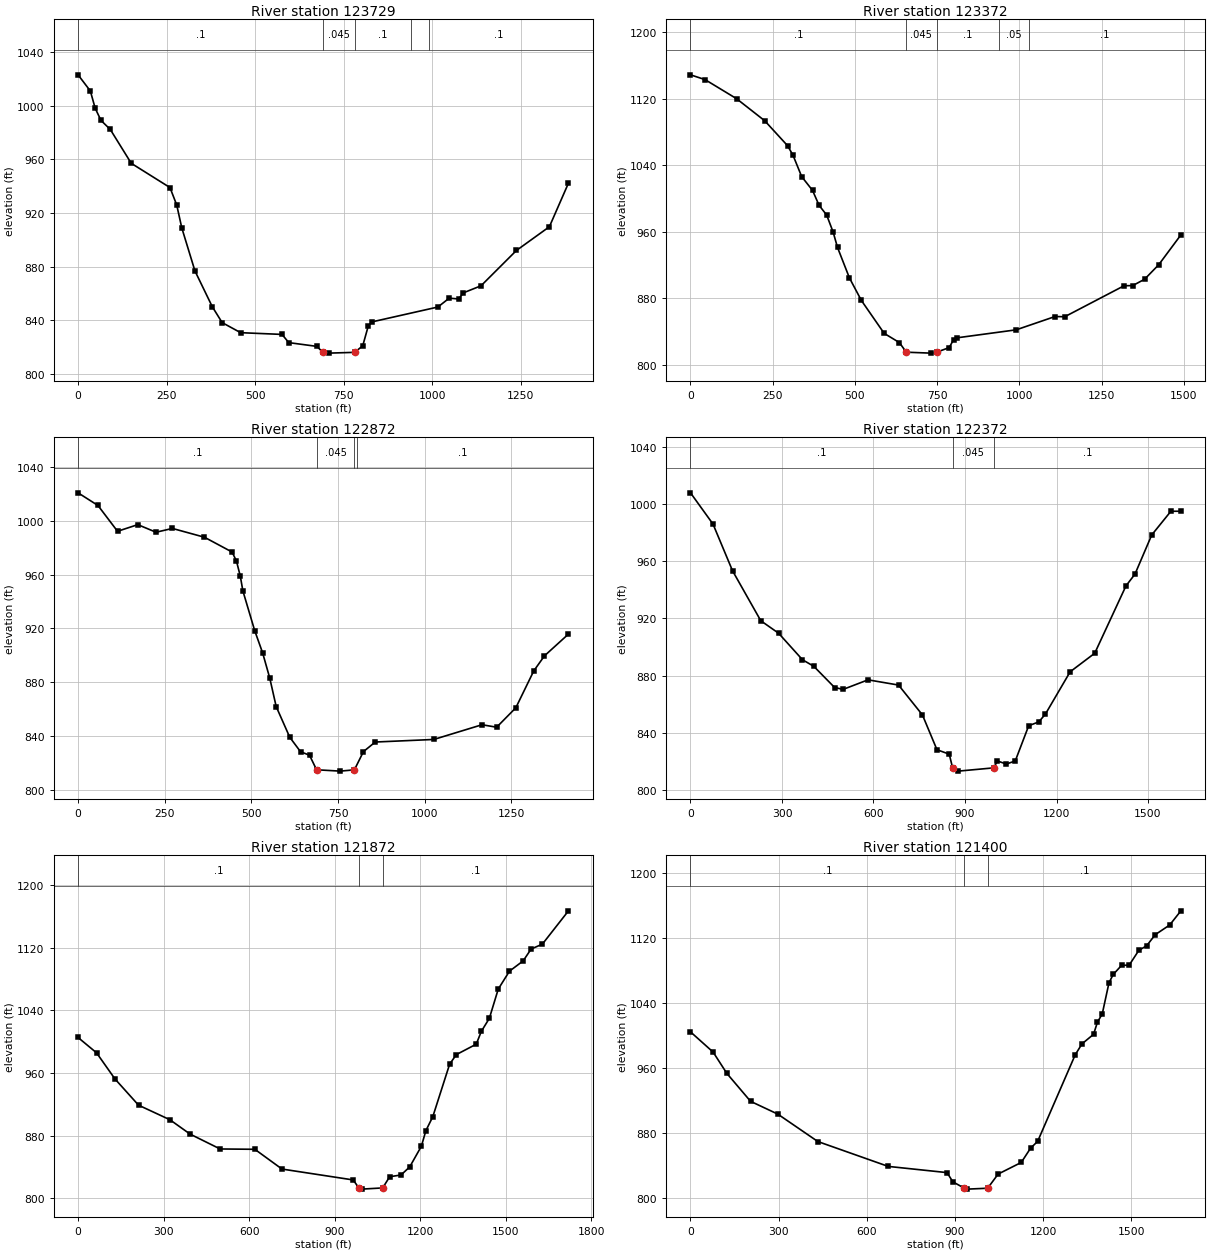
Type RM Length L Ch R = 1 ,123729  ,385.7,356.4,309
XS GIS Cut Line= 5
1664091.55685531451051.9098738131664489.72447644451469.543639813
1664678.82522444451732.0323083141664747.69177895451825.204705594
1665111.32622872451763.606777019
#Sta/Elev= 30
       0 1023.06    34.7 1011.02    48.3  998.18    64.7   989.1    91.1  982.31
   150.3   957.1   259.6  939.03   278.7  926.01   292.9  909.05   330.1  876.92
   379.2  850.18     407  838.37   459.3  830.86   576.1  829.57   595.2  823.45
   674.8  820.64   691.3  816.22   707.9  815.62   781.2   816.2   804.1  821.07
   819.7  835.83   829.9  838.89  1016.4  849.99  1048.4   856.6    1075  855.98
  1088.3  860.56  1138.2  865.81  1238.1  892.12  1331.3  909.83  1385.2  942.35
#Mann= 5 ,-1,0
       0      .1       0   691.3    .045       0   781.2      .1       0
  940.53     .05       0  990.53      .1       0
Bank Sta=691.3,781.2
XS Rating Curve= 0 ,0
Exp/Cntr(USF)=0,0
Exp/Cntr=0.3,0.1

Type RM Length L Ch R = 1 ,123372  ,523.5,500.4,468.7
XS GIS Cut Line= 6
1663714.80498414451820.2830089781664460.69850548451902.317293733
1664539.84237605451896.2188807281664746.76879947451893.975446895
1664972.61939764451897.619796559 1665200.9168413451911.595162317
#Sta/Elev= 30
       0 1149.02    44.4 1143.25   140.1 1120.31   225.9 1093.71   295.3 1063.73
   311.8 1052.27   338.2 1026.53   371.2 1009.98     391  992.05   414.1  980.37
   433.9  959.72   447.1   941.4   483.4  904.65   519.7  877.58     589     838
   635.3  826.91   656.2815.3433   730.7  814.22   748.4815.3447   786.9  820.86
   800.1  830.56   809.9  832.61   990.5  842.25  1108.6  858.25  1138.1  857.98
  1318.6  895.27  1344.9  895.47    1381  903.11  1423.8  920.48  1491.4  956.45
#Mann= 5 ,-1,0
       0      .1       0   656.2    .045       0   748.4      .1       0
  938.52     .05       0 1028.52      .1       0
Bank Sta=656.2,748.4
XS Rating Curve= 0 ,0
Exp/Cntr(USF)=0,0
Exp/Cntr=0.3,0.1

Type RM Length L Ch R = 1 ,122872  ,500.9,500,501.1
XS GIS Cut Line= 6
1663977.12827839452613.567183554 1664090.9367778452618.655099899
1664352.24957539452482.7718414811664579.59885822452364.550293148
1665156.98254597452064.3097518981665245.35769731452018.354791313
#Sta/Elev= 30
       0 1020.97    57.4 1011.56   113.9  992.34   172.3  997.29   225.1  991.64
   272.2  994.47   364.6  987.93   444.5  976.89   457.1  970.14   468.2  958.89
   475.6  947.98   509.7  918.41   532.7  901.75   553.2  883.03   571.7  861.89
   610.9  839.03     642  828.28   667.9  825.68  688.19814.8442   756.6  813.84
   797.4814.8058   823.5  828.38   857.6   835.5  1026.5  837.41  1165.6  848.36
  1207.9  846.52  1263.2  860.99  1314.9   888.4  1345.8  899.63  1415.1  915.85
#Mann= 4 ,-1,0
       0      .1       0  688.19    .045       0   797.4     .08       0
   804.7      .1       0
Bank Sta=688.19,797.4
XS Rating Curve= 0 ,0
Exp/Cntr(USF)=0,0
Exp/Cntr=0.3,0.1

Type RM Length L Ch R = 1 ,122372  ,456.7,500,561.1
XS GIS Cut Line= 6
 1664025.2459643452716.0899443921664187.17247772452823.700293481
1664334.31916505452910.4396213141664462.94193931452958.643593147
1664558.08709022452932.9139858041665459.19814889452484.219673231
#Sta/Elev= 30
       0 1008.04    73.9  986.11   137.8  953.43   230.5   918.4   288.8  909.67
   367.2  891.07   404.2  886.49   472.5  871.62   500.5  870.32   582.1     877
   682.1  873.34   760.4  852.42   808.1  828.01   848.3  824.94   859.4  815.26
   877.8  813.03   994.4815.3228  1006.1  820.16  1035.5     818  1064.8  820.16
  1108.8  844.83  1141.9  847.54  1163.7  853.02  1244.7  882.63  1325.3  895.64
  1427.8  942.86  1457.3  951.09  1512.2  978.53    1575  995.12  1607.8  995.14
#Mann= 3 ,-1,0
       0      .1       0   859.4    .045       0   994.4      .1       0
Bank Sta=859.4,994.4
XS Rating Curve= 0 ,0
Exp/Cntr(USF)=0,0
Exp/Cntr=0.3,0.1

Type RM Length L Ch R = 1 ,121872  ,431.8,471.8,511.1
XS GIS Cut Line= 6
1664029.27056256452727.4196461441664495.13905339453049.281535223
1664622.48131838 453114.189869971664715.80199789453143.687514395
1664792.53675255453186.4531769011665474.97042705453650.731119722
#Sta/Elev= 30
       0 1005.39    64.8  985.83   129.3  952.48   212.2  918.89   322.1   900.3
   392.9  881.95   498.4  862.92   620.1  862.51   715.4  837.25   965.2  823.34
   984.9 813.188   994.4   811.6 1068.68813.1281  1093.2  827.46  1132.9  829.65
  1163.6  840.07  1204.4  866.44  1220.2  886.37  1244.5  904.21  1303.5  971.29
  1327.1  983.53  1396.9  996.85  1414.6 1013.14  1442.9 1029.95  1474.1 1067.29
  1513.5 1090.18  1561.4 1103.27  1589.3 1118.41  1628.9 1124.73  1720.4 1167.27
#Mann= 3 ,-1,0
       0      .1       0   984.9    .045       0 1068.68      .1       0
Bank Sta=984.9,1068.68
XS Rating Curve= 0 ,0
Exp/Cntr(USF)=0,0
Exp/Cntr=0.3,0.1

Type RM Length L Ch R = 1 ,121400  ,526.3,535.1,542.8
XS GIS Cut Line= 3
1664015.37699297452751.8089992151664518.76348908453182.547448227
1664518.76348908454189.188151473
#Sta/Elev= 30
       0 1004.43      77  979.49   123.8  953.19   204.5  918.76   297.2  902.98
   433.6  869.14   673.1  838.49   873.3  830.84   892.9  819.53   932.1811.5977
   942.2  810.47  1011.5811.5788  1047.1  829.04  1125.9  843.39  1157.4  860.89
  1181.7  869.45  1309.6  976.22  1332.6  989.65  1371.9 1001.41  1385.1 1016.37
  1401.5 1026.53  1424.4 1064.88  1438.8 1075.22  1467.1 1086.39  1493.3 1086.78
  1526.1 1105.01  1552.4  1110.5  1581.9 1124.31  1631.1 1136.25  1669.2 1153.71
#Mann= 3 ,-1,0
       0      .1       0   932.1    .045       0  1011.5      .1       0
Bank Sta=932.1,1011.5
XS Rating Curve= 0 ,0
Exp/Cntr(USF)=0,0
Exp/Cntr=0.3,0.1

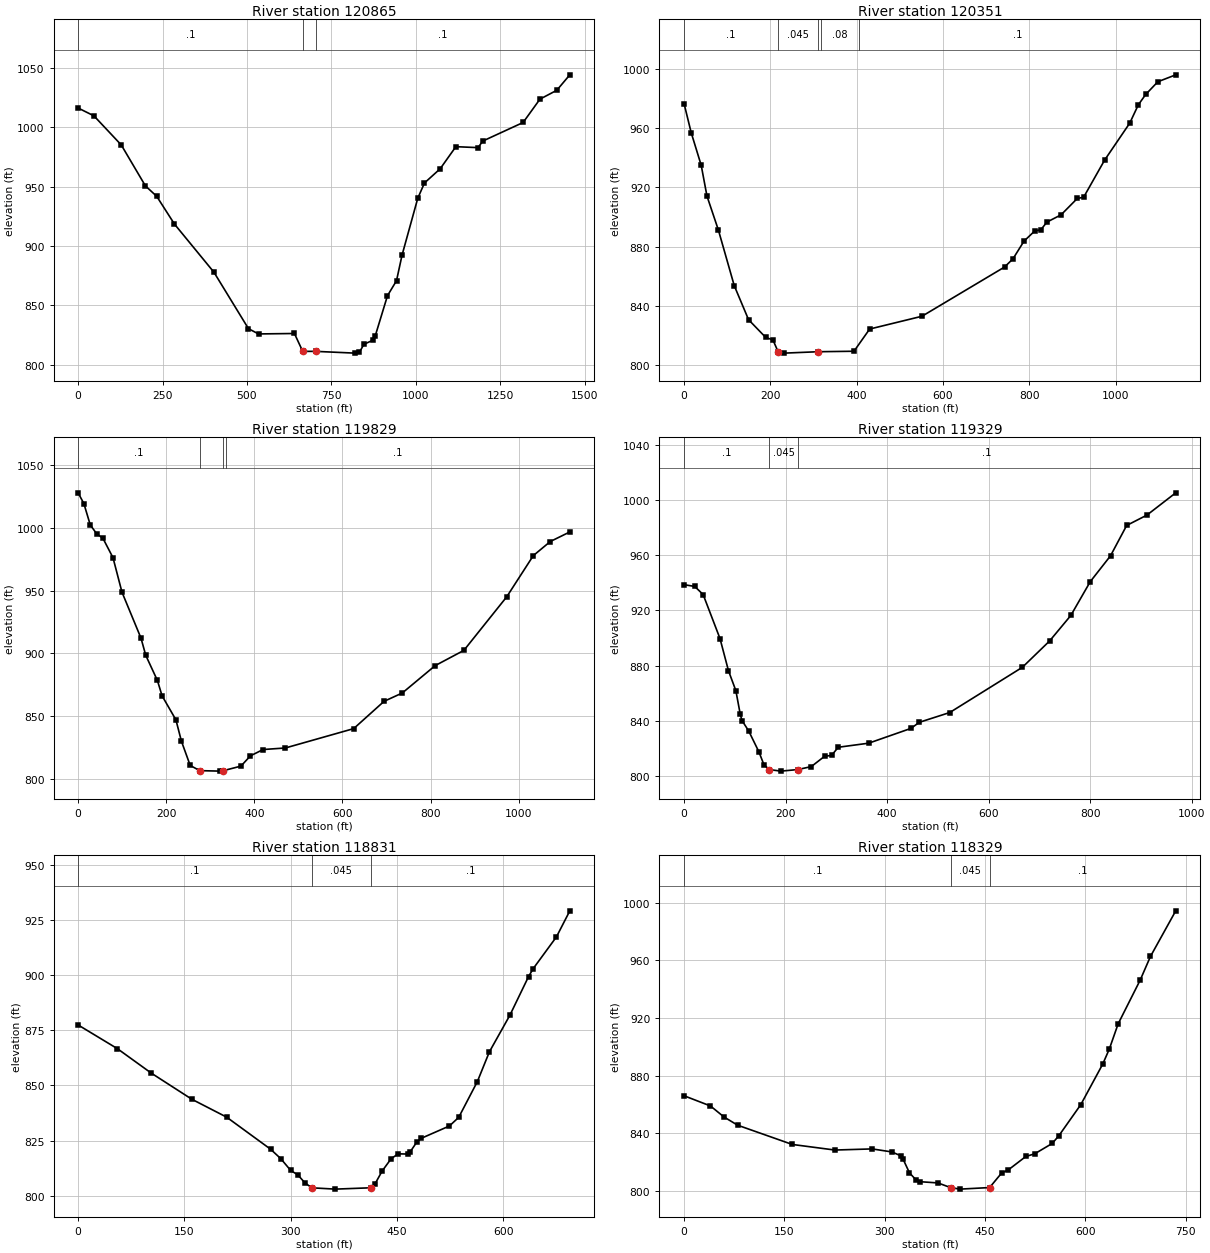
Type RM Length L Ch R = 1 ,120865  ,516.1,514.3,512
XS GIS Cut Line= 6
1663959.37437689452724.1076449011664055.42897481452839.736350641
 1664070.8324873452942.5114075541663947.51088355453740.854955226
1663902.54771888454031.9340974841663887.34105639454130.375829726
#Sta/Elev= 30
       0 1016.24    46.8 1009.65   127.8  985.12   199.2  950.68   232.7  941.87
   285.4  918.44   402.3   877.9   504.5  830.37   534.3  825.95   640.6  826.33
  665.14811.2813   703.7  811.27   819.9  809.79   832.7  810.41   846.5  817.22
     873   820.7   879.7  824.09   916.2  858.19   942.9  870.78   959.3  892.32
  1005.8  940.17  1025.7  953.11  1072.2  965.06  1118.7  983.69  1184.4  982.87
  1198.4  988.42  1317.9 1004.06  1367.7 1023.72  1417.5 1031.16  1456.2  1044.2
#Mann= 3 ,-1,0
       0      .1       0  665.14    .045       0   703.7      .1       0
Bank Sta=665.14,703.7
XS Rating Curve= 0 ,0
Exp/Cntr(USF)=0,0
Exp/Cntr=0.3,0.1

Type RM Length L Ch R = 1 ,120351  ,570.5,521.5,474.6
XS GIS Cut Line= 6
1663474.75994295453055.4448274211663507.59632709453256.045803289
1663487.53739405453483.2580294761663505.36905131453668.554574892
1663579.55853547453880.2263956371663765.59458072454111.214450732
#Sta/Elev= 30
       0  976.43    16.5  956.86    39.8  934.73    53.1  914.06    79.7  891.01
   116.3  853.65   149.5  830.66   189.4  818.66     206  817.04     218809.0143
   232.2  808.12  311.17809.0713   393.8  809.39   430.1  824.36   551.4  832.99
   742.6  866.16   762.2   871.7   787.7   883.6   812.6  890.51   826.8  891.34
     841  896.51   873.6  901.37   911.2  912.41     926  913.27   974.6   938.3
  1032.8  963.22  1052.7  975.58  1069.7  982.53  1097.9  991.12  1139.4  995.79
#Mann= 5 ,-1,0
       0      .1       0     218    .045       0  311.17      .1       0
  316.51     .08       0  406.51      .1       0
Bank Sta=218,311.17
XS Rating Curve= 0 ,0
Exp/Cntr(USF)=0,0
Exp/Cntr=0.3,0.1

Type RM Length L Ch R = 1 ,119829  ,522.3,500,490.2
XS GIS Cut Line= 6
1662844.74963763453511.5663718131663402.80331156453764.018950894
1663483.77755906 453820.060505481663553.91718255453904.092489645
1663649.59940588454006.0643985571663759.18416047 454117.18097423
#Sta/Elev= 30
       0    1028    13.1 1019.36    27.5 1002.48    41.9   995.4    56.3  991.75
    79.2  976.24    99.5  948.82   142.8  912.03   153.5  898.44     180  878.33
   190.6  866.09     222  846.96   234.5  829.93   254.4  810.59   276.2806.4384
   322.8  806.05   329.8806.4346   369.6  810.04   391.2  818.25     420  823.28
   470.4  824.51   625.6  839.95   694.5  861.71   735.9  868.35   810.6  890.19
   875.8  902.36   973.1   945.1  1033.4  977.93  1071.9  989.15  1116.3  996.81
#Mann= 4 ,-1,0
       0      .1       0   276.2    .045       0   329.8     .08       0
  336.25      .1       0
Bank Sta=276.2,329.8
XS Rating Curve= 0 ,0
Exp/Cntr(USF)=0,0
Exp/Cntr=0.3,0.1

Type RM Length L Ch R = 1 ,119329  ,483.6,498.4,504.7
XS GIS Cut Line= 6
1662826.16535722454149.7665389781662912.43027656454135.116961971
1663084.95978713454105.8171518151663530.14852931454030.213956565
1663637.71524331454069.1249679771663753.24191514 454148.71142298
#Sta/Elev= 30
       0  938.68      21  937.41    37.6  931.54    70.9  899.54    87.5  876.34
   102.1  861.82   110.8  844.62   114.2  840.21   127.5  832.54   147.6  817.41
   157.4  808.16   168.1804.6464   190.7  803.53   223.9804.6511   250.6   806.8
   277.2  814.38   290.5  814.87   303.8  820.83   363.8  823.79   446.9  834.49
   463.6  838.93   523.5  846.01   666.6  878.81   720.1  897.85     762  916.37
   800.3  940.89   840.2  959.62     872  981.61   911.9  989.11   968.7 1005.26
#Mann= 3 ,-1,0
       0      .1       0   168.1    .045       0   223.9      .1       0
Bank Sta=168.1,223.9
XS Rating Curve= 0 ,0
Exp/Cntr(USF)=0,0
Exp/Cntr=0.3,0.1

Type RM Length L Ch R = 1 ,118831  ,436.2,501.6,538
XS GIS Cut Line= 6
1662778.37673889454440.9916783121662892.38372873454569.768323645
1662980.11878946454591.3250390591663054.65702622454602.616355062
 1663154.3815643454610.7065619831663410.32724664454623.190788984
#Sta/Elev= 30
       0  877.46    55.4   866.7   103.3  855.59   160.6  843.72   209.6  835.62
   271.6  821.07     286  816.78   300.1   811.4     310  809.44     320  805.82
   329.8  803.54   362.9  802.94   413.2803.5509   418.9  805.24   429.2   811.2
   441.9  816.79   451.8  818.96   464.9  818.87   468.2  819.64   478.1  824.34
   484.6  826.05     524   831.6   537.2  835.53   563.5  851.77   580.5  865.28
   609.4  881.88   635.7  899.39   642.3  903.03   675.1  917.44     694  929.27
#Mann= 3 ,-1,0
       0      .1       0   329.8    .045       0   413.2      .1       0
Bank Sta=329.8,413.2
XS Rating Curve= 0 ,0
Exp/Cntr(USF)=0,0
Exp/Cntr=0.3,0.1

Type RM Length L Ch R = 1 ,118329  ,478.5,499.1,511.6
XS GIS Cut Line= 6
1662715.77417381454503.4541518091662767.17859855454694.693598732
1662763.71666323454800.274752393 1662762.1756558454875.459641397
 1662767.4315508454975.3213183131662780.90035589455231.217131972
#Sta/Elev= 30
       0  865.99    39.5   858.9    59.8  851.23    80.2  845.53   161.8  832.18
   225.4   828.3   281.2  829.08   310.7  826.98   323.8  824.36   327.1  822.35
     337  812.47   346.8  807.57   353.4   806.3   379.6  805.46   398.4802.2382
   412.5  801.16   456.8802.2511   474.9   812.4   484.7  814.48     511  823.85
   524.2  825.67   550.4  832.87   560.3   838.2   593.2  859.87     626  888.03
   635.9  898.57     649  915.93   681.9  946.27   697.3  962.72   735.1  994.39
#Mann= 3 ,-1,0
       0      .1       0   398.4    .045       0   456.8      .1       0
Bank Sta=398.4,456.8
XS Rating Curve= 0 ,0
Exp/Cntr(USF)=0,0
Exp/Cntr=0.3,0.1

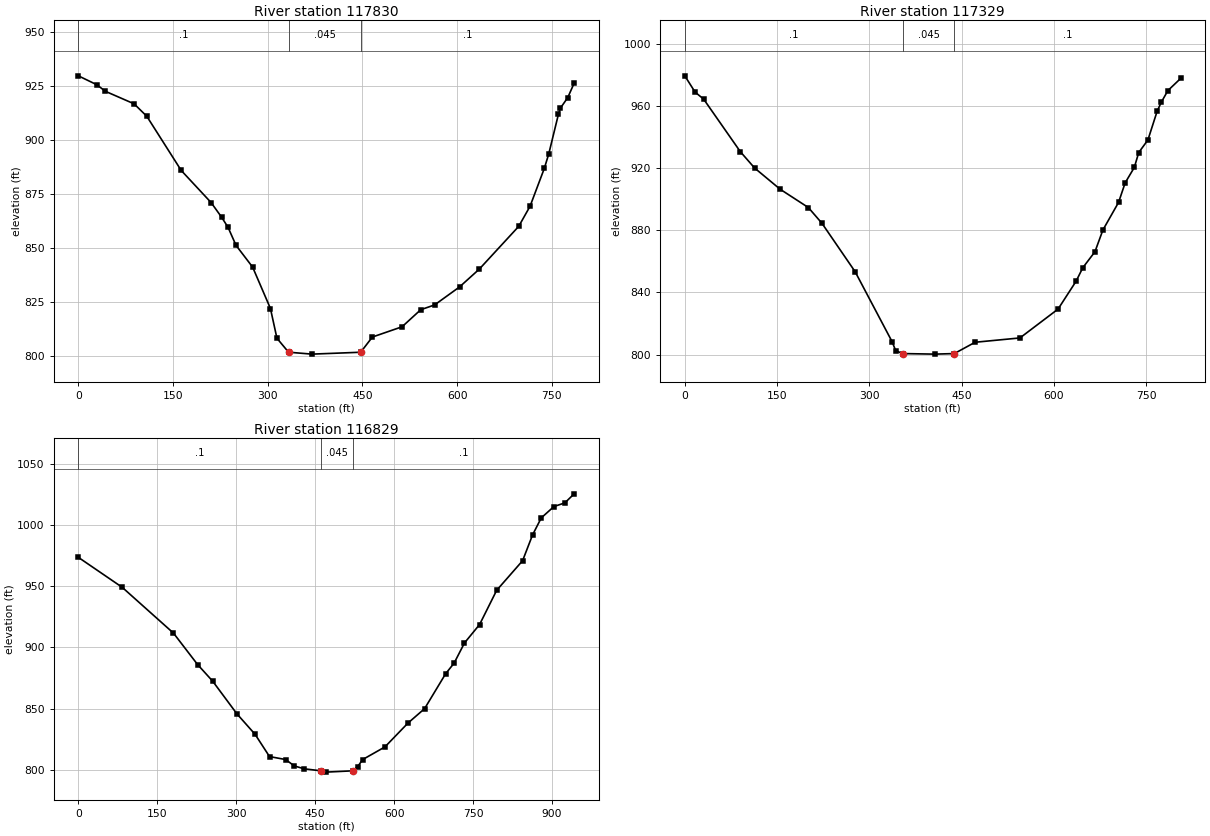
Type RM Length L Ch R = 1 ,117830  ,508.8,500.8,491.2
XS GIS Cut Line= 6
1662469.24550925454252.9412022711662449.23718214454554.566336502
1662373.77649823454657.5480037331662327.79233822454716.889748558
1662269.69698197454782.9798394741662138.85013081454923.936250478
#Sta/Elev= 30
       0  929.66    29.5  925.51    42.7  922.52    88.3  916.71   108.4  910.97
     163  885.88   210.3  871.04   226.8  864.33   237.1  859.61   249.8  851.24
   276.1  841.18   304.3  822.03   314.6  808.27     333801.8214     370  800.93
   447.2801.7995   465.8  808.84   512.8  813.58   542.4  821.48   564.3  823.68
   603.8     832   635.1  840.24   697.6  860.03   715.6  869.37   738.1  886.83
   745.1  893.47   760.5   911.9   763.7  914.75   775.3  919.61   785.4  926.29
#Mann= 3 ,-1,0
       0      .1       0     333    .045       0   447.2      .1       0
Bank Sta=333,447.2
XS Rating Curve= 0 ,0
Exp/Cntr(USF)=0,0
Exp/Cntr=0.3,0.1

Type RM Length L Ch R = 1 ,117329  ,475.9,500.1,509
XS GIS Cut Line= 6
1662154.71722506454005.0355292261662067.95689988454174.818982303
 1662028.2775173454252.8230913881661994.52003889454319.806225151
 1661950.7953888454409.7404284781661796.73598564454727.487168312
#Sta/Elev= 30
       0  979.38    16.7  968.92    30.7  964.36    90.4  930.52   113.5  920.06
     155  906.42   200.9  894.63     223  884.51     277  853.33     337  808.37
   342.9  802.58   354.2800.6467   406.4  800.29   438.3800.6439   472.1  807.93
     545  810.71     607  829.28   636.2  847.14   647.3  855.94     667  866.19
   679.9  880.17   705.4  897.96   716.1  910.52     731  920.44   738.2  930.04
   753.1  938.11   768.1  956.58   774.7  962.28   785.6  969.89   806.3  977.68
#Mann= 3 ,-1,0
       0      .1       0   354.2    .045       0   438.3      .1       0
Bank Sta=354.2,438.3
XS Rating Curve= 0 ,0
Exp/Cntr(USF)=0,0
Exp/Cntr=0.3,0.1

Type RM Length L Ch R = 1 ,116829  ,498.6,500,502.1
XS GIS Cut Line= 6
1661950.23206972453791.1888440551661882.04716672453865.559430227
1661810.07651013453931.7472899711661455.99257264454177.920354053
1661384.14921239454227.8684168911661197.07679376454352.414919218
#Sta/Elev= 30
       0  973.46    83.3  949.01   180.8  911.59   226.6  885.94   255.4  872.29
   301.4  845.65   335.9  828.94   363.3  810.79     394  808.36   410.4  803.14
   429.3  800.79   461.2799.1569   470.3  798.09   521.4799.1536   530.7  802.42
   540.1  808.31   582.6  818.66   626.2  838.06     658  849.93     698  878.44
   714.1  887.11   733.8  903.58   762.5  918.61     795  946.58   844.2   970.7
   863.1  991.72   879.7 1005.68   903.8 1014.96   924.4  1017.9   942.2 1025.32
#Mann= 3 ,-1,0
       0      .1       0   461.2    .045       0   521.4      .1       0
Bank Sta=461.2,521.4
XS Rating Curve= 0 ,0
Exp/Cntr(USF)=0,0
Exp/Cntr=0.3,0.1