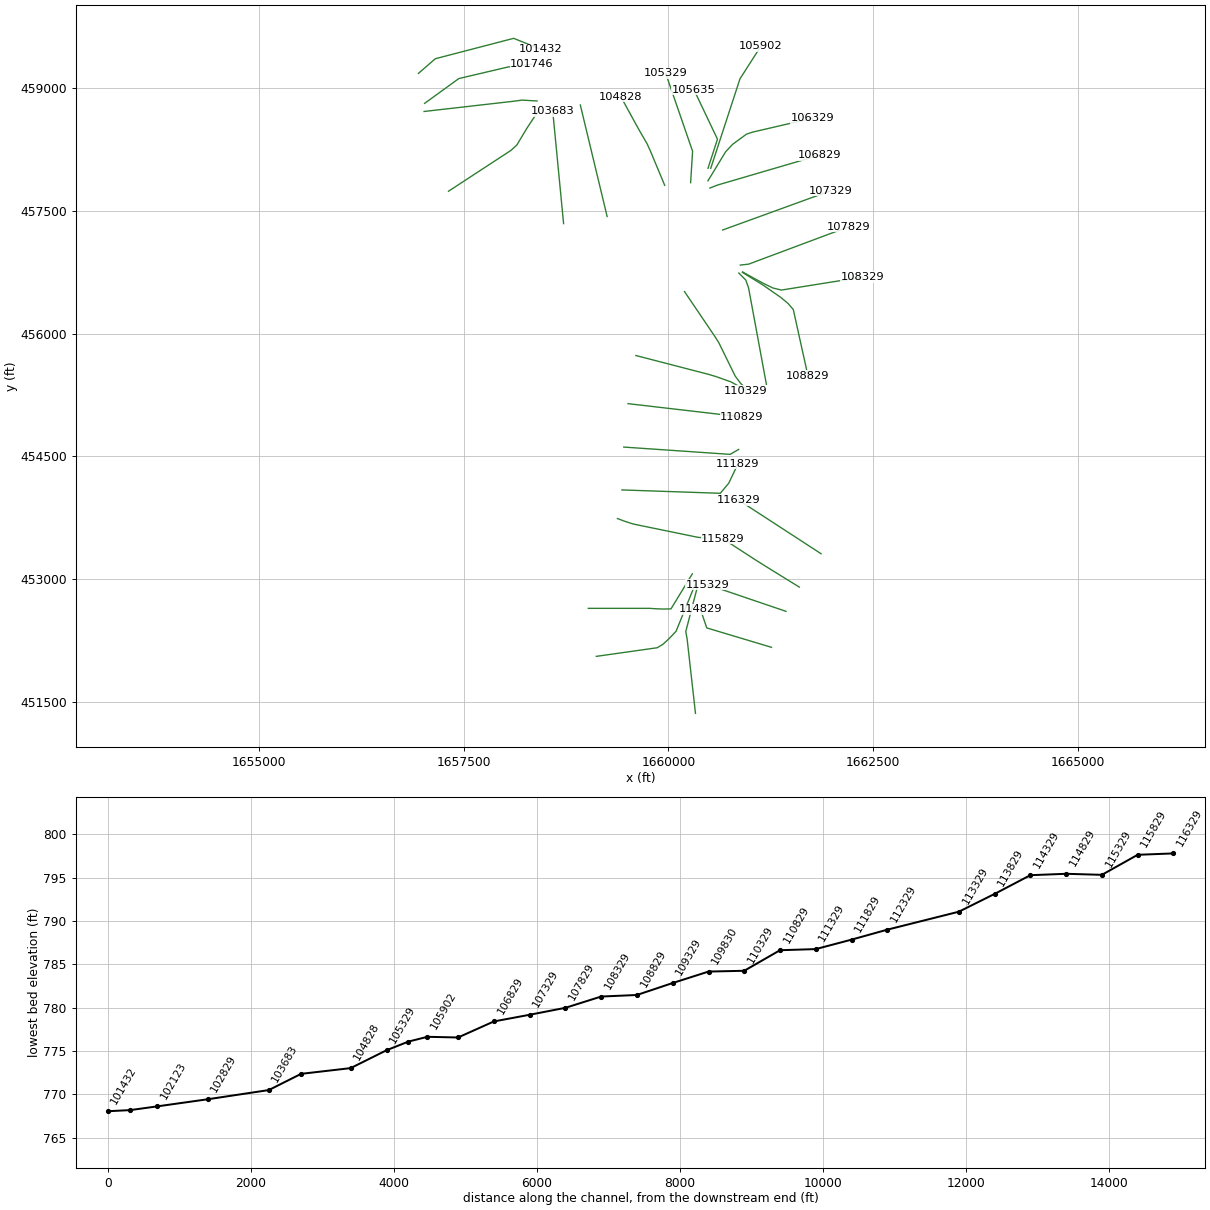
HEC-RAS study FshCrk.prj: FshCrk

--- FshCrk.g01 (geometry) --- (continued)

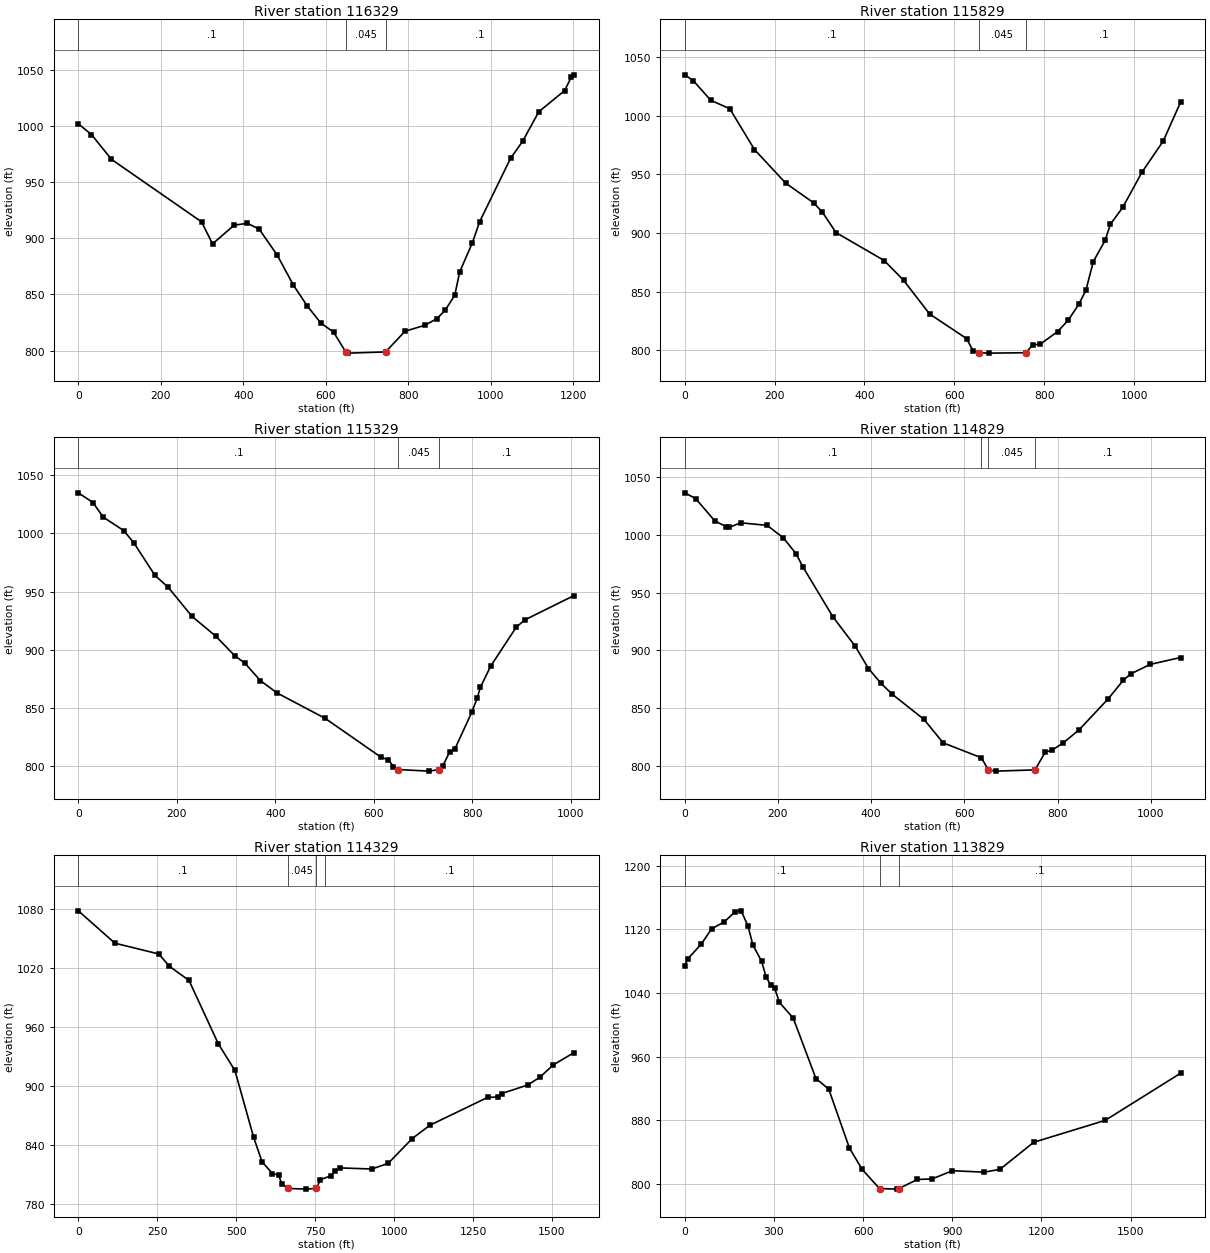
Type RM Length L Ch R = 1 ,116329  ,500,500,500.2
XS GIS Cut Line= 6
 1661863.0022573453311.9260230661661380.81030831453625.876838729
1661317.95839989453666.7993290571661019.41175289453861.180501983
1660938.22786014 453914.038335891660855.73491488453967.748858392
#Sta/Elev= 30
       0 1002.04    31.8   992.5    80.4  970.35   298.6  914.73   325.4  895.07
   377.6  911.74     410  913.41   438.5  908.18     482  885.15   521.4  858.33
   554.6  839.99   587.8  824.61   618.7  816.52   648.3 798.835   654.2  797.78
   744.9 798.844   791.8  817.21   840.6  822.68   869.6  828.57   889.2  835.96
   912.5  849.31   924.5  870.07   955.4  896.21   972.9  914.85  1047.8  971.29
  1077.1  986.43  1116.2 1012.74  1178.9 1031.61  1194.8 1043.41    1202 1045.66
#Mann= 3 ,-1,0
       0      .1       0   648.3    .045       0   744.9      .1       0
Bank Sta=648.3,744.9
XS Rating Curve= 0 ,0
Exp/Cntr(USF)=0,0
Exp/Cntr=0.3,0.1

Type RM Length L Ch R = 1 ,115829  ,487.4,500,510.7
XS GIS Cut Line= 6
1661597.62122639452904.3313658091661262.23967931453111.582263649
1661182.58203022453161.0565741511661108.39320222453207.476428807
1661045.14300063453247.7863875631660665.41246089453495.025722474
#Sta/Elev= 30
       0 1034.85      19 1029.83    57.8 1013.13   100.1 1005.94   155.1  971.13
   224.5  942.56   286.7  925.72   306.1  917.89   336.7  900.34     444  876.52
   486.9  859.75     545  830.97   627.2  810.02   642.1  799.39   654.2797.9586
   677.3  797.62   759.8 797.948   774.3  804.83   790.8  805.09     830  816.03
   853.5  825.68     877  839.23   892.8   851.1   909.4  875.71   935.7  893.78
   947.4  907.45   974.8  921.85  1017.9  951.98  1064.9  978.36  1103.7  1011.6
#Mann= 3 ,-1,0
       0      .1       0   654.2    .045       0   759.8      .1       0
Bank Sta=654.2,759.8
XS Rating Curve= 0 ,0
Exp/Cntr(USF)=0,0
Exp/Cntr=0.3,0.1

Type RM Length L Ch R = 1 ,115329  ,498.1,500,503.4
XS GIS Cut Line= 6
1661434.68356013452608.2243464741661061.57046121 452735.24213706
1660972.82195106 452765.454346971660818.99155006452817.822680563
1660570.49598405452902.4169995641660481.74747388452932.629537568
#Sta/Elev= 30
       0 1035.03    29.7 1026.68    50.5 1014.09    92.1 1002.53   112.9  991.84
   155.6  963.86   182.2  953.79   230.7  928.63   278.9  911.62   317.3   894.8
   338.1  888.34   369.4  873.31     404  862.52     501  840.79     615  807.14
   629.3  805.17   639.7  799.23   649.7796.6478   712.4  795.31   732.3796.6737
   740.2  800.02     754  812.01   764.4  814.34   798.6  845.95   809.5  857.96
   816.4  867.65   837.3  885.89     889  919.27   906.5   925.6  1006.6  946.59
#Mann= 3 ,-1,0
       0      .1       0   649.7    .045       0   732.3      .1       0
Bank Sta=649.7,732.3
XS Rating Curve= 0 ,0
Exp/Cntr(USF)=0,0
Exp/Cntr=0.3,0.1

Type RM Length L Ch R = 1 ,114829  ,548,500,435.8
XS GIS Cut Line= 6
1661258.33745614452168.6012099831661067.89459555452225.733641639
 1660973.6083668452254.0190181431660707.21290222452333.937821567
1660467.75636014452405.7746201461660391.27615737452631.808250472
#Sta/Elev= 30
       0 1036.59    23.3 1031.59    64.4 1012.24    88.4 1007.39    95.3 1006.66
     120 1010.63   176.8 1008.36   211.7  997.52   239.1  983.61   253.2  972.55
   317.9  929.14   365.9  903.52   394.1  884.36   420.7  871.67   444.7   862.2
   513.2  840.28   554.3  819.97   636.5  806.98   651.5796.4931   666.9  795.43
   751.6796.4988   773.5  811.92   787.2  813.41   811.2  819.58   846.2  831.23
   908.5  858.06   941.4  874.36     957  879.72   998.9  887.94    1064  893.89
#Mann= 4 ,-1,0
       0      .1       0  635.39     .08       0   651.5    .045       0
   751.6      .1       0
Bank Sta=651.5,751.6
XS Rating Curve= 0 ,0
Exp/Cntr(USF)=0,0
Exp/Cntr=0.3,0.1

Type RM Length L Ch R = 1 ,114329  ,562.4,500,456.4
XS GIS Cut Line= 6
1660330.11326273451361.8095164751660265.98445398451933.615459472
1660257.62521872452008.1481188091660228.36937173 452269.01275456
 1660211.7358748452361.4850105641660353.62043378452906.812742252
#Sta/Elev= 30
       0 1077.85     116 1044.96   254.9 1034.04   288.2 1021.59   350.6 1007.14
     443  943.02   495.9  915.73   555.3  847.77   581.7  823.17   614.7  811.06
   634.5  809.46   644.4  800.47   662.6796.0036   720.4  795.27   753.9796.0219
   766.6  804.87   799.6  808.75   812.8  813.96   829.3  816.82   929.2   815.7
   981.2  821.39  1057.1  846.55  1113.6  860.16  1296.5  888.44  1330.6   888.8
  1340.8  892.31    1423  900.97  1461.9  908.88  1503.5  921.26  1570.3  933.98
#Mann= 4 ,-1,0
       0      .1       0   662.6    .045       0   753.9     .08       0
  780.39      .1       0
Bank Sta=662.6,753.9
XS Rating Curve= 0 ,0
Exp/Cntr(USF)=0,0
Exp/Cntr=0.3,0.1

Type RM Length L Ch R = 1 ,113829  ,501.6,499.9,491.7
XS GIS Cut Line= 6
1659119.36666848452058.2244622261659862.36288589452163.308897734
1659932.20231314452205.073249891 1660010.5295843452277.253879815
1660093.26990439452364.6474058031660322.79962905452929.703034222
#Sta/Elev= 30
       0 1074.53    10.4 1083.14    55.4 1101.46    90.2 1120.74     133 1129.51
   169.5 1142.34   189.4  1143.4   212.6 1124.47   229.1 1100.39   258.6 1079.81
   273.1 1060.72   288.8 1049.82     302  1046.4   318.6 1028.16     365 1008.25
   441.2  932.34   484.3  919.05   553.8  844.98   596.9  817.88   655.2  793.85
   712.9  793.11   720.5793.8622   782.9  805.28   832.6  805.98   900.4  816.28
  1007.2  814.46  1060.5  817.97    1174  852.05  1414.6  879.64  1668.5  939.01
#Mann= 3 ,-1,0
       0      .1       0   655.2    .045       0   720.5      .1       0
Bank Sta=655.2,720.5
XS Rating Curve= 0 ,0
Exp/Cntr(USF)=0,0
Exp/Cntr=0.3,0.1

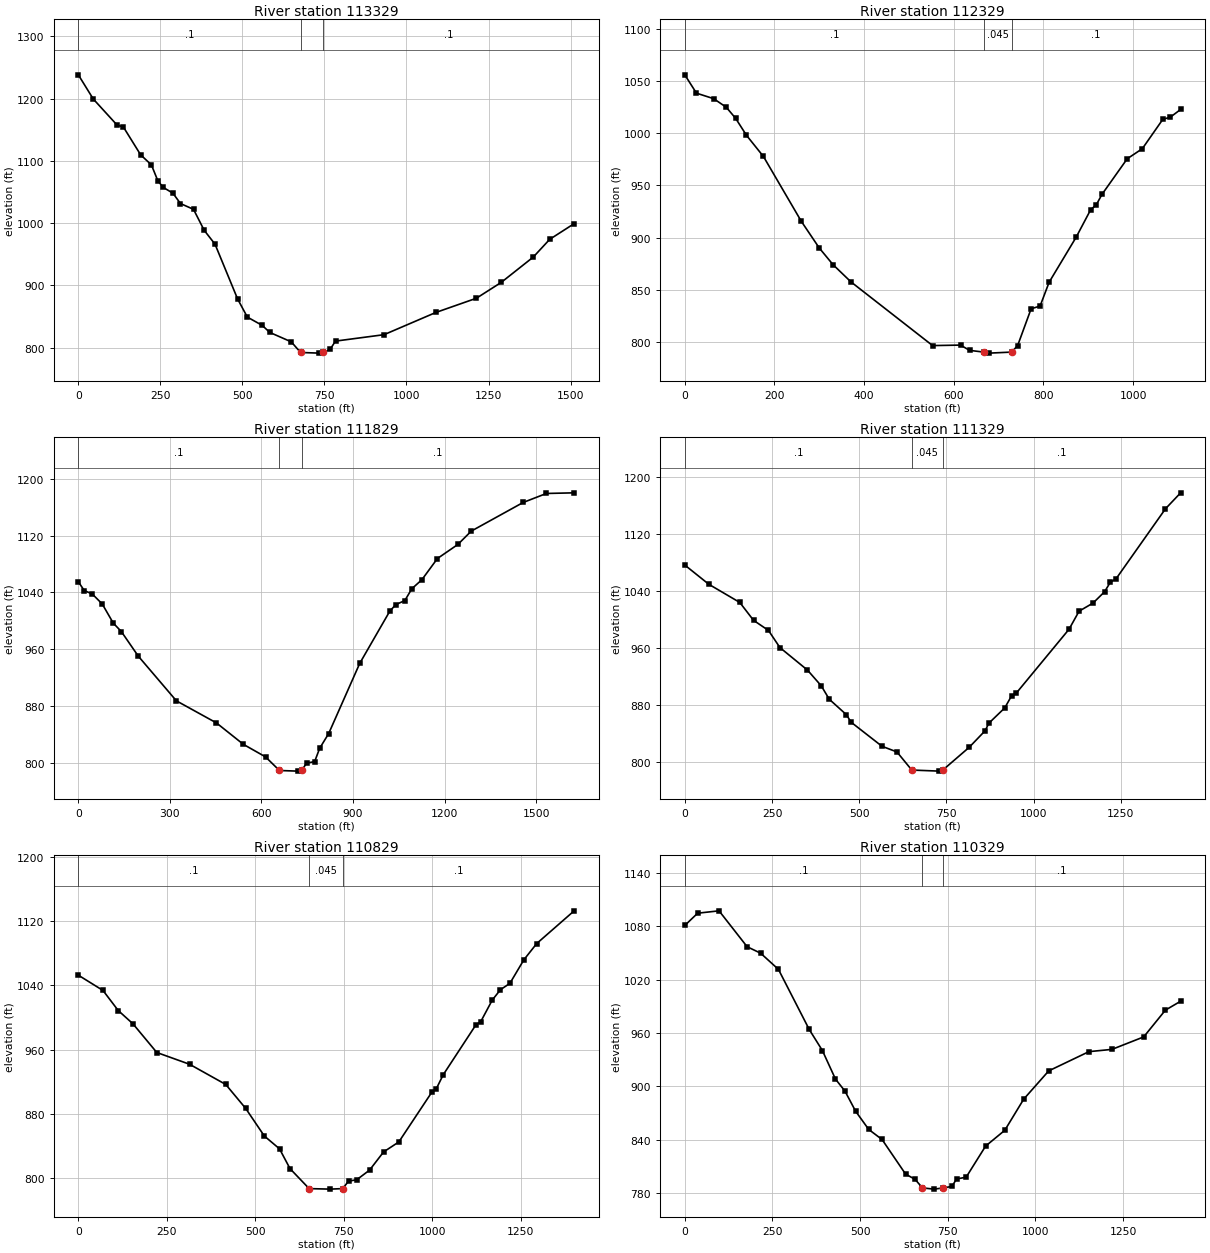
Type RM Length L Ch R = 1 ,113329  ,1001.1,1000.1,985.9
XS GIS Cut Line= 6
1659021.83143046452644.9575407211659772.22231814452644.724601567
1659847.22216813452639.7695589811659935.48281839452636.347977892
 1660031.2480468452638.168840393 1660291.7888643453066.463915557
#Sta/Elev= 30
       0 1238.04    45.5 1199.22   117.7 1157.56   137.4 1154.14   189.9 1109.56
   222.7  1093.4   242.4  1067.7   258.8 1057.23   288.3 1047.91   311.3 1031.28
     351 1022.02   383.5  988.36   416.6  965.97   485.2  878.23     515  848.96
   560.6  835.55   583.3  824.33   648.9  809.18   677.3792.1079     734  791.06
   746.7792.1154   767.3  797.22   783.8  810.38   931.6  820.68  1089.3  856.33
    1213   879.2  1288.7  904.63  1386.6  945.44  1436.5  973.82    1511  999.03
#Mann= 3 ,-1,0
       0      .1       0   677.3    .045       0   746.7      .1       0
Bank Sta=677.3,746.7
XS Rating Curve= 0 ,0
Exp/Cntr(USF)=0,0
Exp/Cntr=0.3,0.1

Type RM Length L Ch R = 1 ,112329  ,493.1,500,504.9
XS GIS Cut Line= 6
1659377.63157189453741.8424860541659472.07429639453706.591900393
1659567.08329272453676.0329063981659663.41118406453655.758012563
1660358.22672355453512.7733903971660455.27803864453503.766190559
#Sta/Elev= 30
       0 1056.23      26 1038.62    64.5 1033.32    92.6 1025.05   113.4 1014.44
   137.5  998.18   175.4  977.82   259.9  915.54   300.1  889.84   330.5  873.99
   370.5  857.44   552.7  796.23     615  796.71   635.1  791.66   666.7789.9788
   678.6  788.99   728.9  789.98   742.3  796.14   772.4  831.54   792.5  834.23
   812.6  857.08   872.9  900.33   905.5   926.9   917.6  931.24   930.5  941.44
   986.8  975.64  1020.4  985.27  1066.2  1013.5  1082.7 1015.51  1105.9 1022.97
#Mann= 3 ,-1,0
       0      .1       0   666.7    .045       0   728.9      .1       0
Bank Sta=666.7,728.9
XS Rating Curve= 0 ,0
Exp/Cntr(USF)=0,0
Exp/Cntr=0.3,0.1

Type RM Length L Ch R = 1 ,111829  ,501.7,500,498.8
XS GIS Cut Line= 6
 1659431.9303478454091.3549103891659729.02292947454081.217791557
1660256.84077147454063.2086412311660633.18450697454050.367459565
1660736.68495613454174.1716738941660848.76773722454410.184981391
#Sta/Elev= 30
       0 1055.03    19.3 1042.59    45.6 1037.77    78.4  1023.6   114.5  996.63
   140.8  984.81   196.6  949.95   321.3  887.01   452.6  855.84   540.7  825.65
   613.5  807.89   658.9788.7385   718.5  787.84   731.4788.7401   748.1  799.13
   774.3  801.28   790.7     820   820.3  840.87     922  939.83  1020.5 1013.48
  1040.2 1022.75  1069.8 1028.46  1092.7 1045.12  1125.6 1057.85  1176.6 1087.79
  1243.5  1107.6  1287.5 1126.45  1457.3 1166.81  1533.6 1179.54  1624.6 1180.45
#Mann= 3 ,-1,0
       0      .1       0   658.9    .045       0   731.4      .1       0
Bank Sta=658.9,731.4
XS Rating Curve= 0 ,0
Exp/Cntr(USF)=0,0
Exp/Cntr=0.3,0.1

Type RM Length L Ch R = 1 ,111329  ,502.3,500,498.1
XS GIS Cut Line= 6
1659454.77905539454614.9289944771659751.34637564454594.563877732
1659941.52348872454581.5041925611660555.70205039454539.328423887
1660752.89391322454525.7874404791660856.87237981 454585.99302873
#Sta/Elev= 30
       0 1076.33    68.8 1049.33   157.6 1023.79     197  998.69   239.8  984.46
   272.7  960.36   351.7   928.7   391.1  906.67   414.1  887.76   463.4  865.97
   476.6  855.53   565.3  821.65   608.1  813.71   650.7788.2625   729.8  786.75
   739.6788.2542   815.3  820.25   861.3  843.73   871.2  853.91   917.2  875.63
     937  892.83   950.1   896.3  1101.4  986.11  1130.2 1011.48  1170.4 1022.99
  1203.3 1038.82  1219.4 1051.86  1236.2 1056.99  1377.9 1155.43  1421.3 1177.82
#Mann= 3 ,-1,0
       0      .1       0   650.7    .045       0   739.6      .1       0
Bank Sta=650.7,739.6
XS Rating Curve= 0 ,0
Exp/Cntr(USF)=0,0
Exp/Cntr=0.3,0.1

Type RM Length L Ch R = 1 ,110829  ,504.6,500,494.5
XS GIS Cut Line= 6
1659506.62803306455145.4505712241660152.65200347455070.210564226
1660251.98054497 455058.642345891660506.50989155455028.998048231
1660602.73476472455017.7913777231660898.00451539454983.402338892
#Sta/Elev= 30
       0 1052.72    69.7  1033.7   112.7 1008.76   154.4   992.2   221.7  956.55
   314.2  941.94   416.5   916.8   472.7  887.07   525.5  852.67   568.4  836.74
   598.1  812.05   652.1787.2645   710.9  786.62   746.9787.2636   763.4  796.58
   786.5  798.27   822.8  810.27   862.4  832.89   905.4  845.28   998.3  906.94
  1011.1  911.25  1030.9  928.88  1123.4  991.08  1136.6  994.71  1169.6 1021.91
  1192.7 1034.72  1219.2 1042.51  1258.8 1071.92  1295.1  1092.1  1400.8 1132.76
#Mann= 3 ,-1,0
       0      .1       0   652.1    .045       0   746.9      .1       0
Bank Sta=652.1,746.9
XS Rating Curve= 0 ,0
Exp/Cntr(USF)=0,0
Exp/Cntr=0.3,0.1

Type RM Length L Ch R = 1 ,110329  ,515.9,498.7,466.6
XS GIS Cut Line= 6
1659602.73085922455733.2994611411660486.40658531455504.199525639
1660576.27910897455477.2888183151660761.14422481455412.084880471
1660850.91865155455363.0052542241660941.13730314455301.023750886
#Sta/Elev= 30
       0 1081.03    36.7 1094.82    97.7 1097.49   177.8 1057.08   216.3 1049.81
   267.1  1031.6   354.9     964   392.5  940.25   429.8  908.13   456.9  894.59
   487.4  871.89   524.7  851.43   562.7  840.11   629.8  801.21   656.9  795.26
   678.1785.6156   711.1  784.25     738785.6088   761.9   787.3   775.5  795.71
   802.6  797.66   858.2  832.69   912.9  850.47   966.9  885.54  1038.2  917.34
  1152.9  938.99  1218.7  941.55  1309.2  955.59    1371   985.7  1414.5  995.73
#Mann= 3 ,-1,0
       0      .1       0   678.1    .045       0     738      .1       0
Bank Sta=678.1,738
XS Rating Curve= 0 ,0
Exp/Cntr(USF)=0,0
Exp/Cntr=0.3,0.1

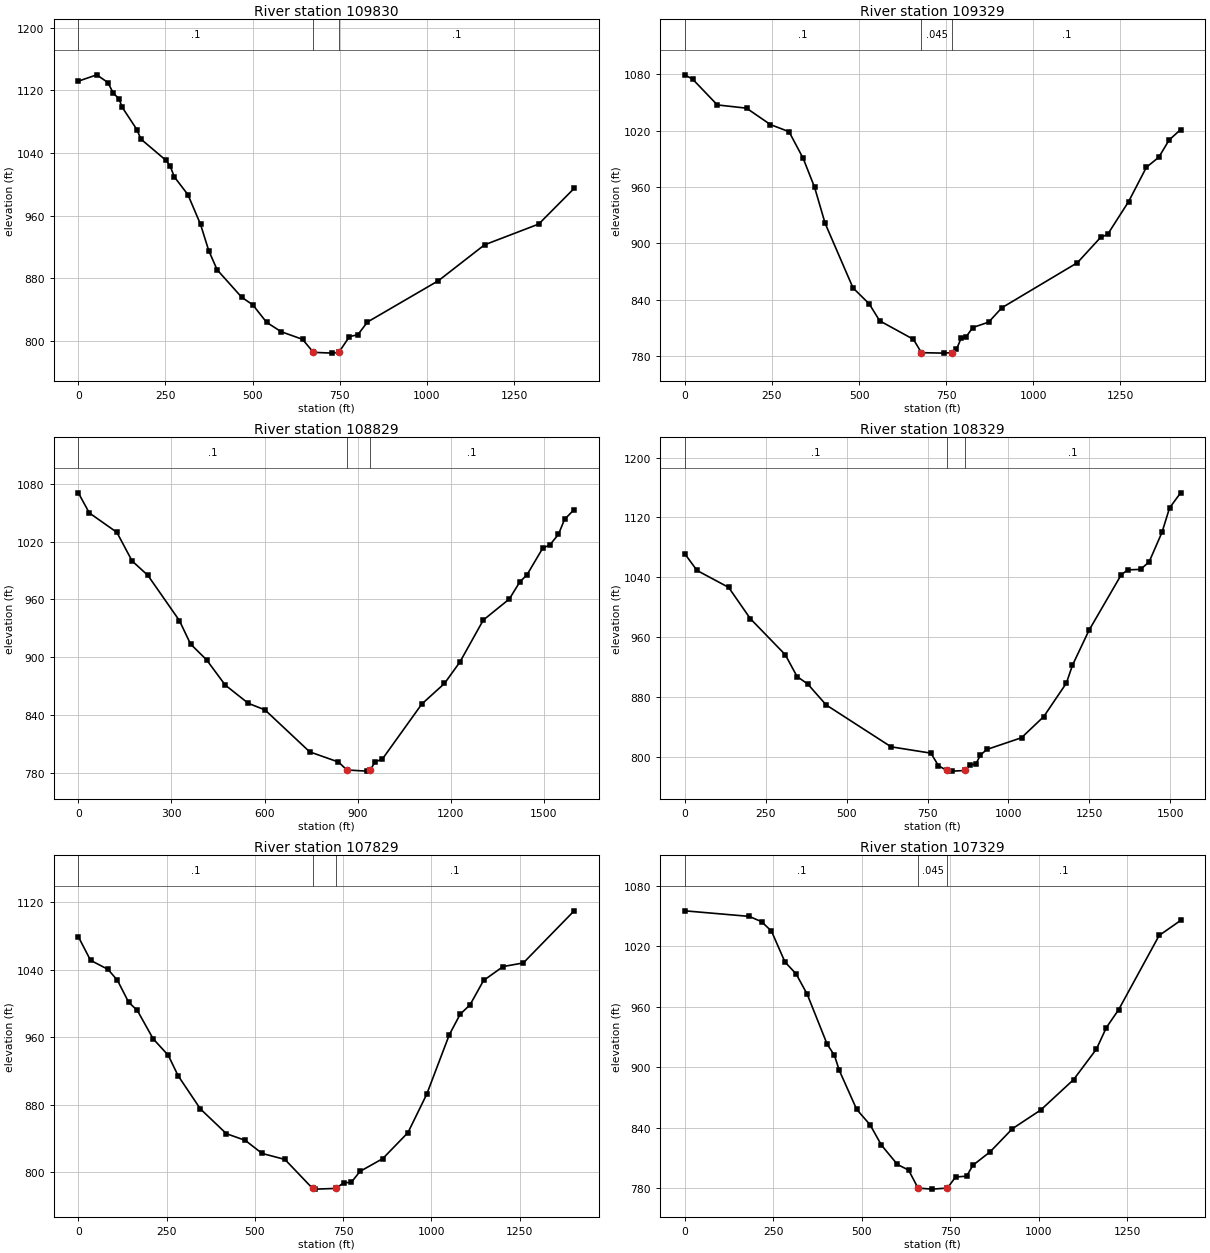
Type RM Length L Ch R = 1 ,109830  ,512.8,501.3,483.1
XS GIS Cut Line= 6
1660196.06792714456514.505247816 1660560.3336028455975.693005234
1660614.12680231 455891.351966561660815.23532397455481.068338305
1660877.96452922455397.4966550621660954.66024198455318.269779399
#Sta/Elev= 30
       0 1131.78    52.9 1139.88    84.6 1130.06   100.4 1116.44   116.3 1109.36
     126 1098.31   167.8 1069.98   179.6 1057.69   251.7 1030.44   263.4 1023.35
   275.1 1009.58   314.3  986.73   350.5  948.77   374.1  915.11   398.1   890.7
   468.7  855.52   500.4  845.91     540  823.51     582  811.52     643   801.8
   674.3  785.15     729  784.16   747.2785.1408   777.7   805.3   801.6   807.6
   829.2  823.88  1032.8  876.72  1165.1  922.57  1320.5  949.11  1422.2  994.74
#Mann= 3 ,-1,0
       0      .1       0   674.3    .045       0   747.2      .1       0
Bank Sta=674.3,747.2
XS Rating Curve= 0 ,0
Exp/Cntr(USF)=0,0
Exp/Cntr=0.3,0.1

Type RM Length L Ch R = 1 ,109329  ,498.2,500,500.7
XS GIS Cut Line= 6
1660859.14862198456740.9011204841660943.75704855456655.400635317
1660977.79635055456560.7896040531661107.43323039455858.593501896
1661159.91245614455574.3345559841661196.00916871455378.810340732
#Sta/Elev= 30
       0 1079.61    22.7 1074.92    93.3 1047.51   177.1 1044.06   245.7 1026.55
   299.1 1018.98   339.6   990.6   372.5  959.59   402.6  921.31   482.6  852.45
   529.3  835.29   559.2  817.29   656.1  797.55   678.9783.3383   742.8  782.84
   766.7783.3406   779.5  786.81   792.9  798.69   806.2   799.7   826.3  810.13
   871.9  815.88   909.7  831.19  1126.5  879.24  1193.2  906.24  1213.3  909.44
  1273.3  944.29  1324.6  981.05  1360.1   991.7  1389.9 1010.15  1422.8  1021.2
#Mann= 3 ,-1,0
       0      .1       0   678.9    .045       0   766.7      .1       0
Bank Sta=678.9,766.7
XS Rating Curve= 0 ,0
Exp/Cntr(USF)=0,0
Exp/Cntr=0.3,0.1

Type RM Length L Ch R = 1 ,108829  ,451.6,500,558.3
XS GIS Cut Line= 6
1660903.98514648456748.7091757211661157.14244856 456592.02182506
1661372.87659714456441.8928602341661459.65923198456369.578372315
1661523.98095372456294.8360677211661702.11412764455488.883611396
#Sta/Elev= 30
       0 1070.88    35.2 1050.02   124.2 1029.78   173.3  999.98   223.9  985.12
   325.7     938   361.5  913.68   413.2  897.23   473.2  871.01   547.6  851.99
   601.4  845.15   745.7  801.46   838.3  790.92   865.3782.6527     929  781.46
   940.9782.6627   955.9  791.07   979.4  793.88  1106.9  851.28  1179.8  872.62
  1229.5  894.89  1304.9  938.55  1388.8  960.46  1422.3  978.07  1445.8  985.69
  1496.2 1013.19  1519.7 1016.85  1547.1 1027.68  1566.6 1043.16  1597.7 1053.48
#Mann= 3 ,-1,0
       0      .1       0   865.3    .045       0   940.9      .1       0
Bank Sta=865.3,940.9
XS Rating Curve= 0 ,0
Exp/Cntr(USF)=0,0
Exp/Cntr=0.3,0.1

Type RM Length L Ch R = 1 ,108329  ,494.7,500,506.4
XS GIS Cut Line= 6
1660904.30798048 456754.399124981661034.07576555456682.396972388
1661158.43378456456614.7816220671661275.93322147456558.026486233
1661378.04194114456532.933032483 1662372.0917903456691.647938147
#Sta/Elev= 30
       0  1071.5    37.9 1049.22   135.4 1026.68   202.7  984.78   310.5  936.73
   346.9  907.62   379.8  897.65   436.7  869.72   637.5  813.74   760.5  805.29
   783.7  788.62   809.7782.1218   826.9  781.28     867782.1346   880.1   789.2
   899.9  791.02   913.3  802.64   933.2  810.17  1040.5  825.89  1109.3  854.14
  1179.1  898.78    1198  922.73  1248.9  969.19  1348.5 1043.39  1368.5 1050.03
  1408.3 1050.69  1434.9 1060.73  1474.8 1100.38    1498 1132.77  1532.2 1152.94
#Mann= 3 ,-1,0
       0      .1       0   809.7    .045       0     867      .1       0
Bank Sta=809.7,867
XS Rating Curve= 0 ,0
Exp/Cntr(USF)=0,0
Exp/Cntr=0.3,0.1

Type RM Length L Ch R = 1 ,107829  ,500.1,500,497.4
XS GIS Cut Line= 6
1660876.86151305456838.070217475 1660979.1831588456849.739157394
1661424.81940664457016.3999133111661658.98002756457103.972572804
1662011.68404655457235.8781488981662197.91464522457305.525647387
#Sta/Elev= 30
       0 1079.18    34.5 1051.26    84.1 1040.43   110.9 1027.44   142.5 1001.48
     167  991.84   211.9  958.16   254.6  938.68   282.6  914.38   345.6  875.08
   419.2  845.71   472.6  837.83   520.4  822.28     585  815.18   663.4780.8343
   671.4  779.98   729.3780.8137   751.9  787.55     773  787.95   797.5  800.94
     862   816.1   933.4  846.91   986.6  892.39  1050.6  962.96  1081.3  987.24
  1109.3  998.44  1147.7 1027.36  1203.1 1043.85  1260.2  1048.1  1404.2 1109.88
#Mann= 3 ,-1,0
       0      .1       0   663.4    .045       0   729.3      .1       0
Bank Sta=663.4,729.3
XS Rating Curve= 0 ,0
Exp/Cntr(USF)=0,0
Exp/Cntr=0.3,0.1

Type RM Length L Ch R = 1 ,107329  ,502.6,500,497.3
XS GIS Cut Line= 6
 1660661.4692273457266.5631268921661202.21748964457463.198888481
1661519.39762956457578.5375685541661791.05719122457677.322147891
1661884.30208348457711.2298884841661977.91442905457745.270502806
#Sta/Elev= 30
       0 1055.15   181.9 1049.64   216.8 1044.39   244.8 1035.07   282.9 1004.47
   314.6  992.54     346  972.29   401.9  923.13   422.8  911.72   436.5  896.88
   485.6  858.25   523.6  842.91   555.5  822.81   600.8  803.61   632.3  798.05
   658.9780.2154   698.6  779.18   741.9780.2141   764.9  791.17   796.3  792.04
   813.8   802.8   862.7   816.2   925.5  839.09  1005.8   857.7  1098.4  887.78
  1162.9  918.02  1190.8  939.26  1225.7  957.12  1340.2 1030.75  1400.8 1045.58
#Mann= 3 ,-1,0
       0      .1       0   658.9    .045       0   741.9      .1       0
Bank Sta=658.9,741.9
XS Rating Curve= 0 ,0
Exp/Cntr(USF)=0,0
Exp/Cntr=0.3,0.1

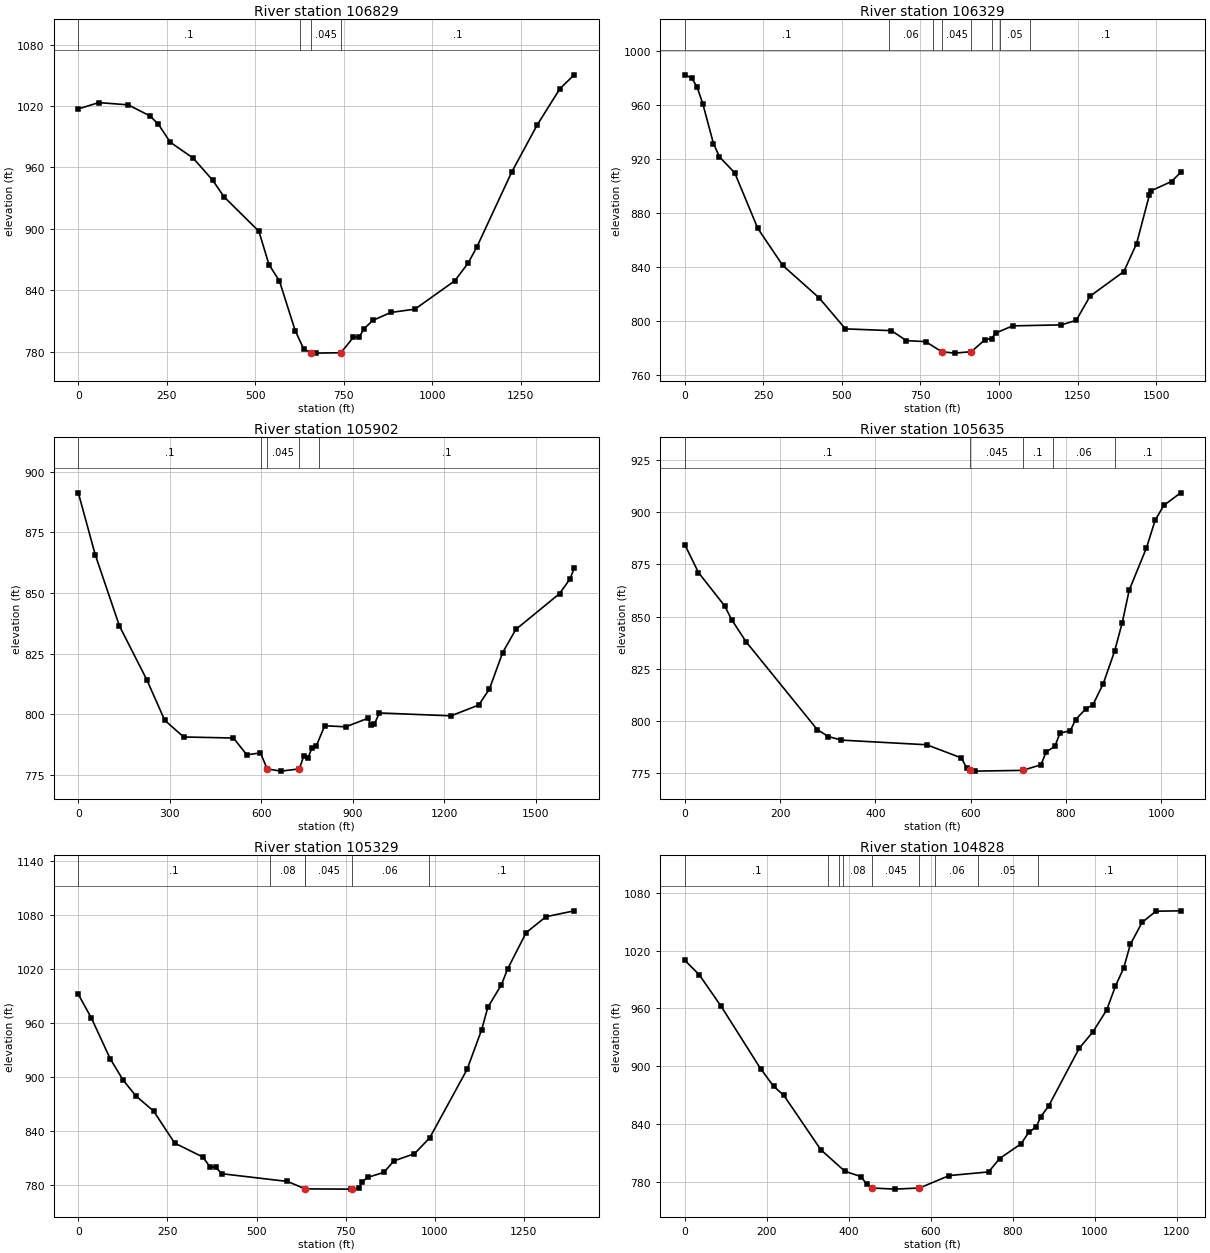
Type RM Length L Ch R = 1 ,106829  ,502.1,500.5,497.6
XS GIS Cut Line= 6
 1660506.5069388457779.1359206441660599.54021731457815.872395724
1660789.22225264457871.4484000651661296.04112089458019.943181813
1661752.62780614458153.720801398 1661848.2188223458181.727963224
#Sta/Elev= 30
       0 1017.11    57.7 1023.28     141 1021.09   203.1 1010.12   226.5 1001.98
   259.6  984.61   324.7  968.95   379.8  947.35   411.9  931.11   510.2  897.52
   538.8  864.92   568.3  848.95   612.8  800.52   636.7  782.53   656.7778.8088
   670.7  778.41     742778.8071   776.9  793.69     794  794.36   807.7  802.31
   832.3  810.42   883.4  818.19   951.3  821.39  1064.1  849.18  1101.7  866.49
  1126.6  882.42  1224.7  955.35  1296.5  1001.3  1361.1 1036.94  1401.2 1050.43
#Mann= 4 ,-1,0
       0      .1       0  625.81     .06       0   656.7    .045       0
     742      .1       0
Bank Sta=656.7,742
XS Rating Curve= 0 ,0
Exp/Cntr(USF)=0,0
Exp/Cntr=0.3,0.1

Type RM Length L Ch R = 1 ,106329  ,362.6,427,462.2
XS GIS Cut Line= 6
1660482.23566189457867.1393535581660698.38221122458222.778077975
 1660782.4748908 458312.435050891660952.02507664458437.234670058
1661025.46784313458461.9629670531661756.31054156458632.126996815
#Sta/Elev= 30
       0  982.61      22  980.26      39  973.67    57.5     961    91.2  931.75
     110  921.98   159.1  909.94   232.2  868.94   311.8  841.47   427.6  817.46
   511.1  794.52   657.5   793.2   705.4  785.79   766.4  785.09   817.7  777.62
   858.3  776.56   911.9777.6318   955.9  786.62   976.1  787.31   989.6  791.48
  1043.5  796.74  1198.5  797.48  1245.7  800.84  1289.5  818.67  1397.3  836.99
  1437.8  857.69  1478.2   893.4  1484.9  896.86    1549  903.63  1577.9  910.33
#Mann= 8 ,-1,0
       0      .1       0  649.33     .06       0  790.06      .1       0
   817.7    .045       0   911.9      .1       0  977.56     .06       0
 1002.56     .05       0 1100.06      .1       0
Bank Sta=817.7,911.9
XS Rating Curve= 0 ,0
Exp/Cntr(USF)=0,0
Exp/Cntr=0.3,0.1

Type RM Length L Ch R = 1 ,105902  ,227.1,266.2,307.2
XS GIS Cut Line= 3
1660516.19135459458019.0461176811660873.19003788459113.528923031
1661129.19567261459512.803766184
#Sta/Elev= 30
       0  891.29    55.4  865.78   134.8  836.43   224.5  814.27   283.1  797.61
   345.3  790.71   508.6  790.28   552.3  783.36   597.2  784.15  618.93777.5574
     664  776.64   724.6  777.56   738.7  782.71   752.5  782.01   766.3  786.23
   780.1  787.03   807.7  795.34   876.7  794.89   949.2   798.4   959.5  795.78
   969.9  795.89   987.1  800.61  1221.6  799.41  1312.8  803.88  1347.8  810.48
  1391.1  825.49  1434.4  835.02  1577.8  849.79    1612  855.84  1625.5  860.22
#Mann= 5 ,-1,0
       0      .1       0     600    .025       0  618.93    .045       0
   724.6     .06       0     790      .1       0
Bank Sta=618.93,724.6
XS Rating Curve= 0 ,0
Exp/Cntr(USF)=0,0
Exp/Cntr=0.3,0.1

Type RM Length L Ch R = 1 ,105635  ,311,306.3,298.8
XS GIS Cut Line= 3
1660483.30989692458021.3947932281660598.39499877458376.044800971
1660311.85658192458979.654416797
#Sta/Elev= 30
       0  884.36    28.7  871.02    83.9     855    98.3  848.51   128.8  837.88
     278  795.97   301.2  792.64   328.8  790.91   508.1  788.69   580.7  782.39
   592.1  777.52   599.8  776.47   609.8  776.09   709.2776.4549   747.8  779.12
   758.7  785.29   776.8  787.89   787.7  794.24   809.5  795.41   820.4  800.69
   842.2  805.93   856.7  807.71   878.5  817.87   902.3  833.36   918.5  847.13
     933  862.58   969.3  882.83   987.5  896.02  1005.6  903.09    1041  909.12
#Mann= 5 ,-1,0
       0      .1       0   599.8    .045       0   709.2      .1       0
  772.86     .06       0  902.86      .1       0
Bank Sta=599.8,709.2
XS Rating Curve= 0 ,0
Exp/Cntr(USF)=0,0
Exp/Cntr=0.3,0.1

Type RM Length L Ch R = 1 ,105329  ,494.9,501.6,510.3
XS GIS Cut Line= 6
1660270.90035257 457844.637175011660294.92009164458228.241321638
1660235.83326755 458399.589732231660178.78449714458565.030018151
1660154.33474289458635.9327634721659966.76129913459179.890993148
#Sta/Elev= 30
       0  991.64    36.9   965.1    89.4  920.04   125.6  896.36   161.5  878.71
   211.1  861.94   270.2  826.29   349.1  810.81   368.9  800.21   385.5  799.19
   402.7   792.2   586.8  783.62   636.5775.3491   763.6  775.09   767.1  775.33
   787.9  776.14   795.8  783.18   812.2   788.2   857.3  793.71   885.1  806.41
   942.9  814.47   985.7  832.05  1090.5  908.11  1131.5  952.39  1148.8   977.2
    1187 1002.41  1204.4 1019.96  1256.4 1060.34  1311.9 1077.97    1391 1084.54
#Mann= 6 ,-1,0
       0      .1       0  538.11     .08       0  635.61      .1       0
   636.5    .045       0   767.1     .06       0  983.11      .1       0
Bank Sta=636.5,767.1
XS Rating Curve= 0 ,0
Exp/Cntr(USF)=0,0
Exp/Cntr=0.3,0.1

Type RM Length L Ch R = 1 ,104828  ,700.8,692.7,678.9
XS GIS Cut Line= 6
1659954.42831856457812.6522578151659780.74953206458229.478851974
1659739.40118955458320.5839847331659657.02471389458462.576154813
1659610.81319214458545.3919340671659418.83096455458895.261313066
#Sta/Elev= 30
       0 1009.88    35.4   994.8    88.7  962.21   184.7  897.83   216.5  879.55
   241.7  870.03     332  813.72   390.8  791.43   429.9  786.01   444.1  777.91
 457.672774.1911   511.9  773.03 572.472774.1882   645.2  787.07   741.3  790.84
   767.8  804.62   820.4  819.92     839  831.71   857.3  837.47   868.8  848.18
   887.5  858.93   962.1  918.69   995.8  935.85  1029.5  958.63  1050.7  983.17
  1070.7 1001.73  1086.9 1026.22  1115.7 1049.13  1149.6 1060.69  1209.7 1061.07
#Mann= 9 ,-1,0
       0      .1       0  349.06     .08       0  376.56      .1       0
  386.56     .08       0 457.672    .045       0 572.472     .08       0
  611.61     .06       0  715.77     .05       0  860.61      .1       0
Bank Sta=457.672,572.472
XS Rating Curve= 0 ,0
Exp/Cntr(USF)=0,0
Exp/Cntr=0.3,0.1

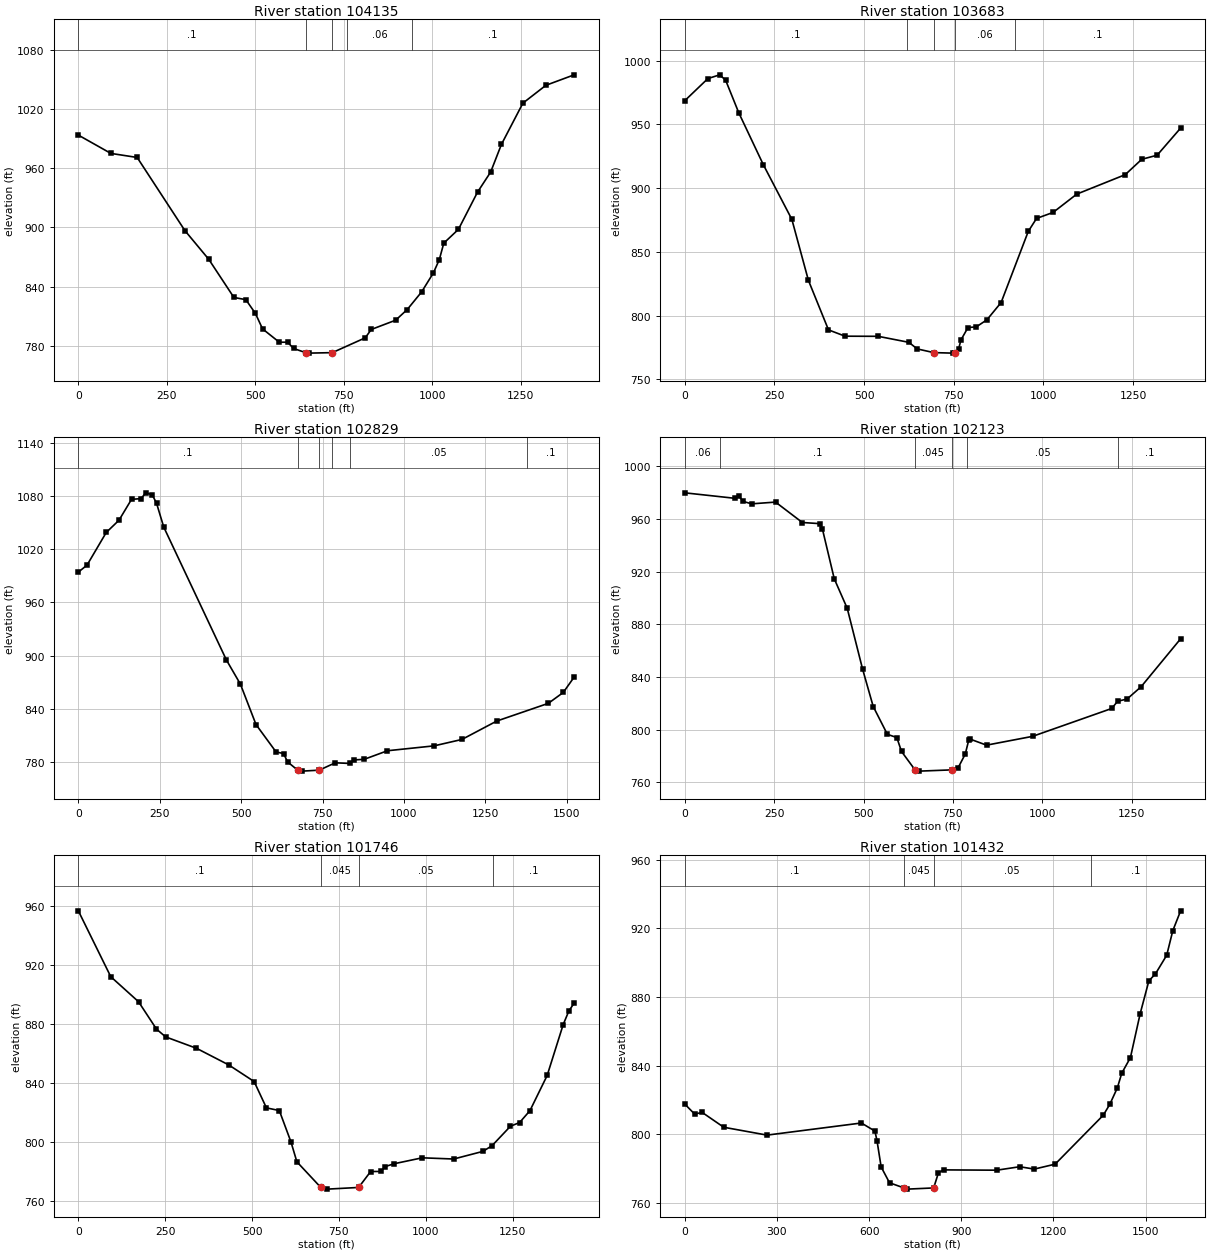
Type RM Length L Ch R = 1 ,104135  ,455.8,451.8,444.2
XS GIS Cut Line= 6
1659252.06887342457431.1439576431659159.98342766457814.376458897
1659100.11379674458063.5344251531659076.75032641458160.767170309
1659016.88069549458409.9248084861658924.79524975458793.157309724
#Sta/Elev= 30
       0  993.78    91.9  975.18   166.2  971.06   301.1  896.78   368.6  867.58
   439.5   828.9   473.2  826.68   500.2  812.74   520.5  796.98   567.7  783.46
   591.3  783.46   608.1  777.07   642.3772.8708   650.4  772.37   717.5772.8657
   810.6  787.91   827.5  796.37   896.5  805.81   929.2  816.64     970   834.6
    1003  853.79  1019.8  867.28  1032.5  884.07  1073.8  898.05  1127.8  935.85
  1164.9  956.25  1195.3  984.31    1256 1026.22  1320.9 1044.32  1400.8 1054.97
#Mann= 5 ,-1,0
       0      .1       0   642.3    .045       0   717.5      .1       0
  760.39     .06       0  942.89      .1       0
Bank Sta=642.3,717.5
XS Rating Curve= 0 ,0
Exp/Cntr(USF)=0,0
Exp/Cntr=0.3,0.1

Type RM Length L Ch R = 1 ,103683  ,881,853.9,808.6
XS GIS Cut Line= 2
1658720.63636393457344.8358830421658587.92792586458720.859842803
#Sta/Elev= 30
       0  968.58    64.4  985.93    97.4  988.86   113.9  984.61   150.4  959.13
     219   918.3   298.5  875.44   344.6  827.63   400.6  788.75   446.8  783.79
   539.1  783.69   624.8  778.97   647.8  773.82     694  770.91   746.7   770.5
   752.3  770.83   763.2  773.47   769.8   780.8   789.6  790.59   812.6  791.07
   842.3  796.64   881.9   810.2   957.7  866.06   980.7  876.18  1026.9  880.91
  1092.8  895.26  1227.9  910.52  1274.1  922.59  1316.9  925.79  1382.4  947.07
#Mann= 5 ,-1,0
       0      .1       0     620     .08       0     694    .045       0
   752.3     .06       0     920      .1       0
Bank Sta=694,752.3
XS Rating Curve= 0 ,0
Exp/Cntr(USF)=0,0
Exp/Cntr=0.3,0.1

Type RM Length L Ch R = 1 ,102829  ,721.9,706,685.3
XS GIS Cut Line= 6
1657315.89192897457740.0500408111658079.70733047458240.005405724
1658150.42405255458305.5613769741658273.25090663458510.493381813
1658347.32720205458623.3832478971658426.96418189458737.788530886
#Sta/Elev= 30
       0  994.15    26.9 1002.23    85.7 1038.97   124.9 1052.85   163.4 1076.43
   192.2  1077.2   207.3 1083.77   226.9 1081.58   240.2    1072   262.2 1045.17
   454.9  894.86   497.8  867.63   545.7  822.02   607.2  791.12   630.3  789.29
   642.5  779.93   673.6  770.54   687.1  769.44   739.9770.5322     789  778.85
   834.1   778.1   845.2  782.07   877.8  782.77   949.4  792.47  1092.5  797.98
  1178.1  805.22  1284.8  825.97  1443.4  846.01  1489.3  858.31  1522.7  875.68
#Mann= 6 ,-1,0
       0      .1       0   673.6    .045       0   739.9     .07       0
  780.39     .06       0  835.39     .05       0 1378.24      .1       0
Bank Sta=673.6,739.9
XS Rating Curve= 0 ,0
Exp/Cntr(USF)=0,0
Exp/Cntr=0.3,0.1

Type RM Length L Ch R = 1 ,102123  ,372.5,377.2,385.4
XS GIS Cut Line= 6
1657018.12601234458714.5801657581657215.66859625458737.156236081
1657409.71774883458759.3336851741658114.50505316458839.880768164
1658212.05111791458853.2878935921658396.89818917458842.764648368
#Sta/Elev= 30
       0  979.84   140.7  975.67   150.6  977.48   163.8  973.29     187  971.48
   253.9  972.81   328.9  957.31   378.5  956.44   385.1  952.22   418.1  914.62
   454.4  892.19   497.4  846.01   527.1  817.66   566.7  796.54   593.1  794.11
   606.3  783.53   644.1769.5566   655.9  768.62   746.4 769.565   764.8  771.26
   784.6  781.57   794.6  792.45   797.9  792.95   844.1  788.33   972.9  795.01
  1194.4  816.18  1210.9  821.67  1237.2  823.32  1276.6  832.68  1387.1  869.06
#Mann= 6 ,-1,0
       0     .06       0   99.61      .1       0   644.1    .045       0
   746.4      .1       0  790.39     .05       0 1211.98      .1       0
Bank Sta=644.1,746.4
XS Rating Curve= 0 ,0
Exp/Cntr(USF)=0,0
Exp/Cntr=0.3,0.1

Type RM Length L Ch R = 1 ,101746  ,314,313.8,315.1
XS GIS Cut Line= 4
1657024.13414485 458813.332243181657441.89210048459116.528457342
1658042.58486385459257.9336818851658334.25671696459291.865858726
#Sta/Elev= 30
       0  957.01    93.3  912.33   173.2  895.35   224.9  876.77   251.1  871.49
     340  863.75   432.9  852.46   505.9  841.19   541.3  823.32   578.4  821.51
   612.1  800.09   628.9  786.74   697.9769.3155   716.6  768.19   806.6769.3282
   841.3  780.15   871.6  780.17   881.7  783.38   908.7  785.41   989.6  789.44
  1080.1  788.62  1164.2  793.79  1190.6  797.67  1243.5  810.85  1269.9  813.38
  1299.6  821.41  1349.2  845.29  1395.4  879.88  1411.9  889.19  1426.9  894.37
#Mann= 4 ,-1,0
       0      .1       0   697.9    .045       0   806.6     .05       0
  1193.3      .1       0
Bank Sta=697.9,806.6
XS Rating Curve= 0 ,0
Exp/Cntr(USF)=0,0
Exp/Cntr=0.3,0.1

Type RM Length L Ch R = 1 ,101432  ,448.8,478.3,507.7
XS GIS Cut Line= 4
1656948.81452778459179.3974539641657155.07645989459358.872122167
1658111.38178151459607.9936765381658438.18640122459476.736083374
#Sta/Elev= 30
       0  817.64    31.8  811.85    56.8  812.75   126.8  804.13   267.7  799.55
   574.7  806.61   618.8   801.9   625.6  796.26   639.1  780.98   666.3  771.76
   713.7  768.74   723.9  768.06  810.03 768.759   825.6  777.61   842.6  779.28
  1015.5   779.1    1090  781.12  1137.5  779.74  1205.3  782.61    1362  811.14
  1383.2  817.46    1408  827.16  1422.1   835.6  1450.4  844.74  1482.2   870.4
  1510.5  889.51  1531.7  893.51  1568.5  904.41  1588.3  918.71  1613.8   930.3
#Mann= 4 ,-1,0
       0      .1       0   713.7    .045       0  810.03     .05       0
 1321.64      .1       0
Bank Sta=713.7,810.03
XS Rating Curve= 0 ,0
Exp/Cntr(USF)=0,0
Exp/Cntr=0.3,0.1