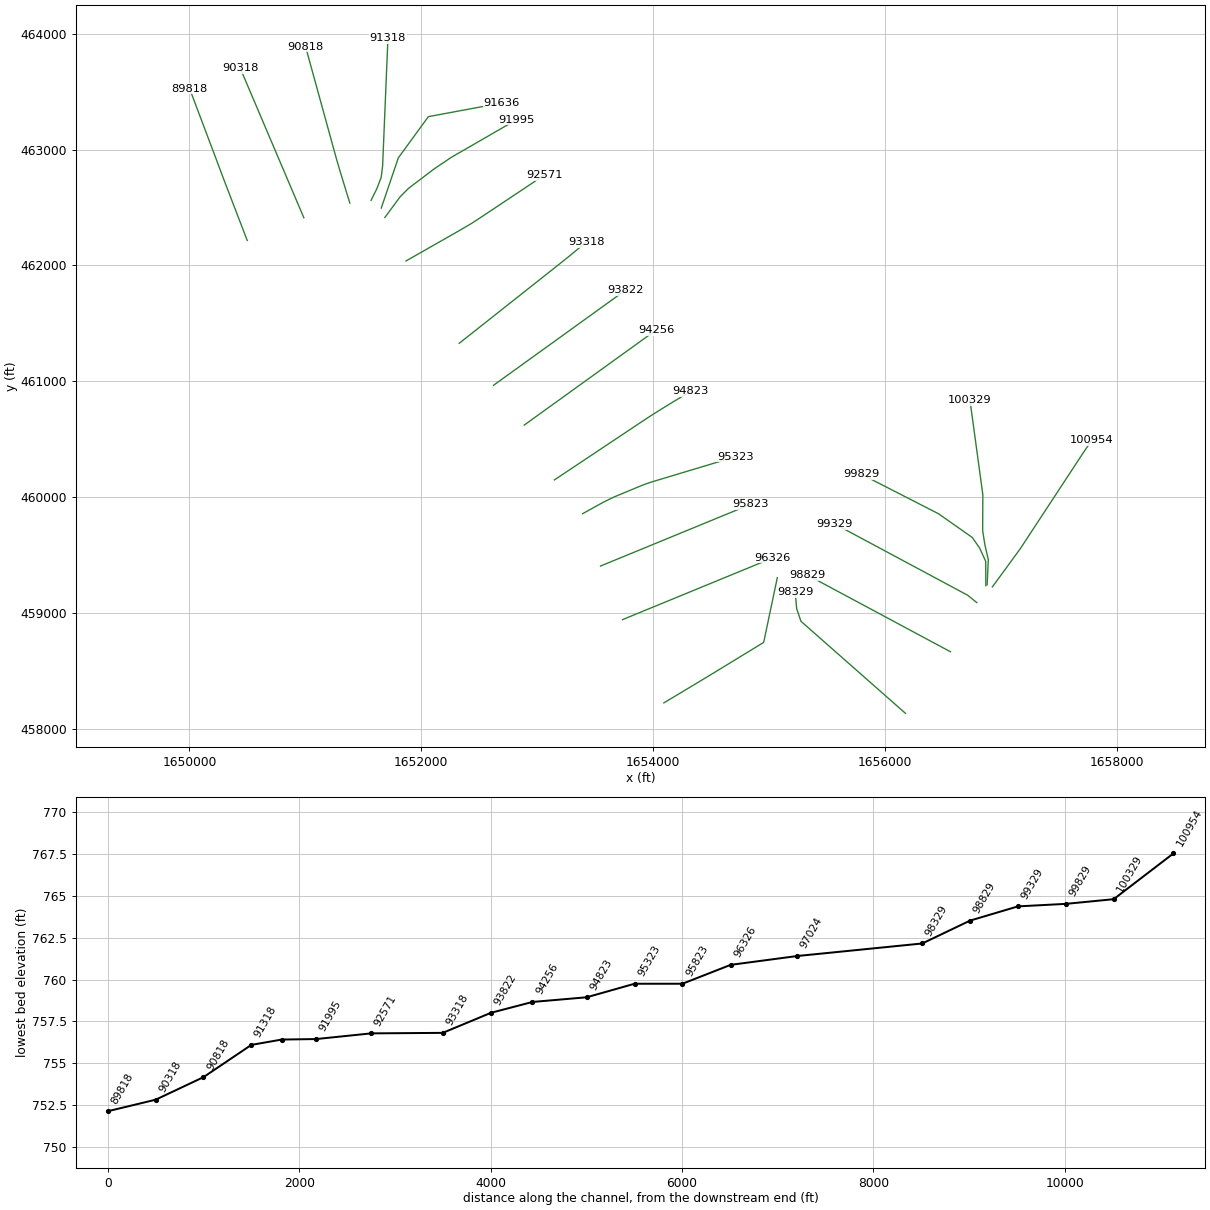
HEC-RAS study FshCrk.prj: FshCrk

--- FshCrk.g01 (geometry) --- (continued)

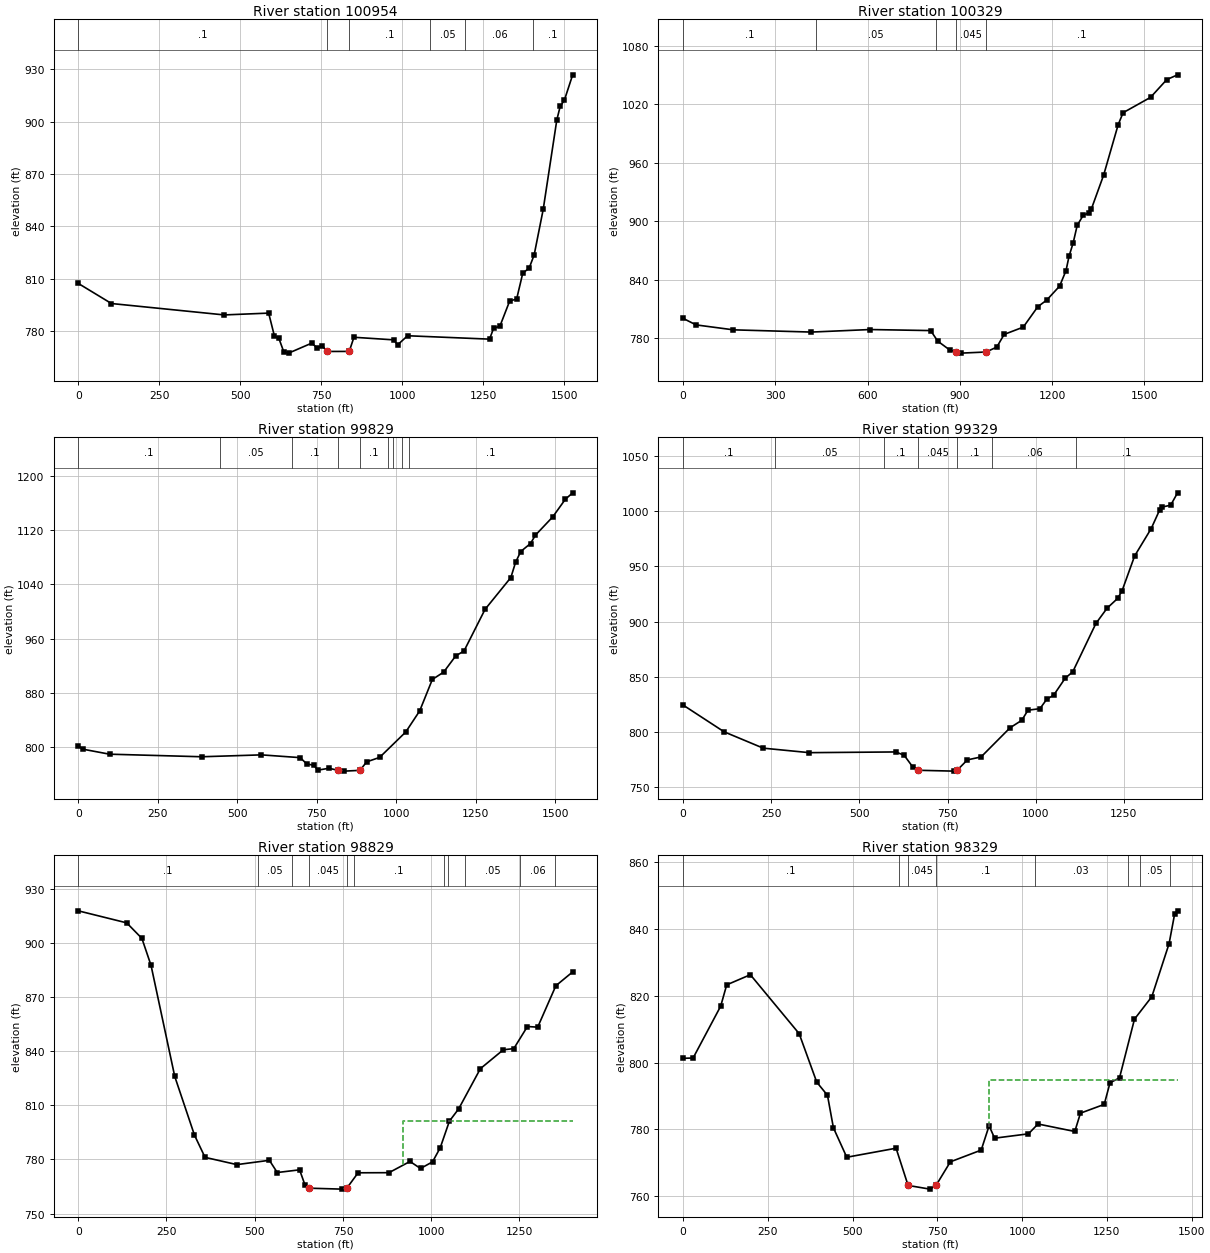
Type RM Length L Ch R = 1 ,100954  ,605.7,624.7,672
XS GIS Cut Line= 4
1656923.59842221459225.6573058071657162.71901889459552.851518396
1657714.64638227460394.4048818081657779.25853681460489.471766978
#Sta/Elev= 30
       0  807.42   102.5  795.92   450.8   789.4   587.9  790.44   605.9  777.16
   619.2   776.1   634.9  768.15   649.5  767.55   721.3   773.3   737.5  770.44
   753.8  771.76   767.4   768.5   836.7  768.53   851.2  776.62   974.1  775.14
     986  772.26  1016.8  777.49    1270  775.55  1282.3  781.71  1301.9  782.95
  1331.9  797.27  1353.7  798.57  1372.5  813.28  1392.2  816.18  1407.6  823.66
  1435.6  849.73  1477.7  900.98    1488  908.63    1501  912.22  1526.6  926.73
#Mann= 6 ,-1,0
       0      .1       0   767.4    .045       0   836.7      .1       0
 1085.26     .05       0 1195.26     .06       0 1405.26      .1       0
Bank Sta=767.4,836.7
XS Rating Curve= 0 ,0
Exp/Cntr(USF)=0,0
Exp/Cntr=0.3,0.1

Type RM Length L Ch R = 1 ,100329  ,471.7,500.1,551
XS GIS Cut Line= 6
1656878.74122848459243.7350255551656888.84455472459460.932425812
1656859.03654347459590.6470613931656840.17995389459711.364667729
1656841.65534464 460021.066804231656730.39014722460839.318776637
#Sta/Elev= 30
       0   800.4    41.9  793.75   163.4  788.68     417  786.39     608  788.99
     805  787.92   828.2  777.07   867.7  767.88   887.4765.9741   904.1  764.81
   985.2765.9713  1020.1  770.98  1044.1     784  1106.2  791.45  1153.6  812.39
  1182.4  819.13  1224.5  833.49  1245.3   849.4  1255.2  864.15  1268.5   877.7
  1281.7  895.73  1301.6  906.26  1318.9  908.31  1328.1  912.81  1367.8  947.39
    1415  998.98    1431 1011.24  1520.2 1026.96  1573.2  1045.2  1608.2 1050.06
#Mann= 5 ,-1,0
       0      .1       0  430.53     .05       0  822.42      .1       0
   887.4    .045       0   985.2      .1       0
Bank Sta=887.4,985.2
XS Rating Curve= 0 ,0
Exp/Cntr(USF)=0,0
Exp/Cntr=0.3,0.1

Type RM Length L Ch R = 1 ,99829   ,500.6,499.9,501.2
XS GIS Cut Line= 6
1656867.51060788459236.4089247291656866.38331355459446.280552223
1656814.11438923 459561.34331423 1656750.3353173 459652.75684531
1656458.53832872459857.6763829741655790.73717089460199.907325804
#Sta/Elev= 30
       0  801.45    16.4  796.72    98.4  789.52   388.5  785.72   576.1  788.51
   698.1  784.42   717.9  775.43   741.5   772.9   753.3  765.94   788.2  768.76
   818.3765.6505   837.3  764.53   885.9 765.675   907.1  778.22   947.7  784.76
  1029.8  822.17  1073.7  853.29  1113.6  899.77  1149.2   910.6  1187.3  934.61
  1213.1  941.67  1279.4 1003.18  1360.5 1050.09  1375.3 1072.51  1391.6 1088.46
  1422.3 1100.28  1437.9 1112.66  1492.4 1139.64  1531.9 1165.57  1554.9 1175.03
#Mann= 9 ,-1,0
       0      .1       0  446.25     .05       0     671      .1       0
   818.3    .045       0   885.9      .1       0  974.51     .06       0
  989.51      .1       0 1019.51     .06       0 1039.51      .1       0
Bank Sta=818.3,885.9
XS Rating Curve= 0 ,0
Exp/Cntr(USF)=0,0
Exp/Cntr=0.3,0.1

Type RM Length L Ch R = 1 ,99329   ,500.1,500,500.2
XS GIS Cut Line= 6
1656789.77454288459090.2343483121656710.91118355 459153.93139939
1656451.38775247459293.201790139 1656291.6807228459378.906343147
 1656071.3957303459497.1200174841655564.39543197459769.195588812
#Sta/Elev= 30
       0  824.26   116.2  800.03   227.1  785.22   357.9  781.13   603.1  781.78
   626.9  778.77   651.1  768.25   666.3765.1503   768.4  764.38   777.1  765.15
   806.2  774.58     845  777.24   927.3  803.69   960.5  810.49   978.2  819.65
  1012.1  821.03  1031.5  829.63  1050.9  833.23  1083.4  848.53  1105.3  854.55
  1170.8   898.3  1202.5  912.16  1232.3  920.99  1244.8  927.76  1280.7  959.56
  1327.7   984.4  1351.4  1001.1  1358.6  1003.9  1382.9 1005.58  1402.5  1016.8
#Mann= 7 ,-1,0
       0      .1       0  260.59     .05       0  569.66      .1       0
   666.3    .045       0   777.1      .1       0  877.16     .06       0
 1115.28      .1       0
Bank Sta=666.3,777.1
XS Rating Curve= 0 ,0
Exp/Cntr(USF)=0,0
Exp/Cntr=0.3,0.1

Type RM Length L Ch R = 1 ,98829   ,509.7,500,487.1
XS GIS Cut Line= 6
1656562.25400056458666.2601306441656214.96073189458852.631148979
1656055.25370222458938.3357019721655675.26168005459142.253929317
1655589.90128647459188.0619085581655327.96841139459328.624947637
#Sta/Elev= 30
       0  917.71   137.2  911.05   180.3  902.44   206.2  887.48   273.4  825.93
   329.3  793.43   359.2  781.13   449.4  777.11   541.5   779.5   563.8  772.73
   627.1  774.22     642  766.03     655764.0435   746.8  763.53   760.9 764.045
   792.8  772.58   880.3  772.64   939.9  778.86   969.7  774.97  1003.7  778.63
  1025.5  786.43  1051.6  801.21  1077.7  807.97  1139.3  830.26  1204.3  840.73
    1234  841.38  1272.6  853.62  1301.7  853.26  1353.2  876.21  1400.8  883.87
#Mann= 11 ,-1,0
       0      .1       0  507.89     .05       0  605.39      .1       0
     655    .045       0   760.9     .06       0  780.39      .1       0
 1036.64     .05       0 1046.64      .1       0 1096.64     .05       0
 1251.95     .06       0 1351.17      .1       0
#XS Ineff= 2 , 0
                          919.84          801.02
Permanent Ineff=
       F       F
Bank Sta=655,760.9
XS Rating Curve= 0 ,0
Exp/Cntr(USF)=0,0
Exp/Cntr=0.3,0.1

Type RM Length L Ch R = 1 ,98329   ,1366.1,1305.3,1190.8
XS GIS Cut Line= 6
1656174.74427688458134.3468243931655808.81521872458457.043685555
1655743.18838148458514.9175855671655273.25264156 458929.33375147
1655236.48467048459037.6504639831655223.59197973459179.203002393
#Sta/Elev= 30
       0  801.27    29.3  801.35   110.7  816.86   128.4  823.22   198.2  826.25
   342.2  808.63   394.1  794.13   425.7  790.21   443.2   780.5   482.6  771.69
   628.1  774.39   663.5763.2639   728.1  762.16   745.9763.2566   788.2  770.32
   879.2  773.83   902.5   781.1   918.7  777.39  1018.6  778.69  1046.8  781.63
  1155.3  779.39    1172  784.87  1242.1  787.49  1259.2  793.95  1287.2  795.42
  1331.4  812.98  1382.5  819.68  1433.5  835.56    1450   844.5  1458.5  845.35
#Mann= 8 ,-1,0
       0      .1       0  635.39     .08       0   663.5    .045       0
   745.9      .1       0 1036.64     .03       0 1311.95     .06       0
 1346.34     .05       0 1436.34      .1       0
#XS Ineff= 2 , 0
                          900.85           794.9
Permanent Ineff=
       F       F
Bank Sta=663.5,745.9
XS Rating Curve= 0 ,0
Exp/Cntr(USF)=0,0
Exp/Cntr=0.3,0.1

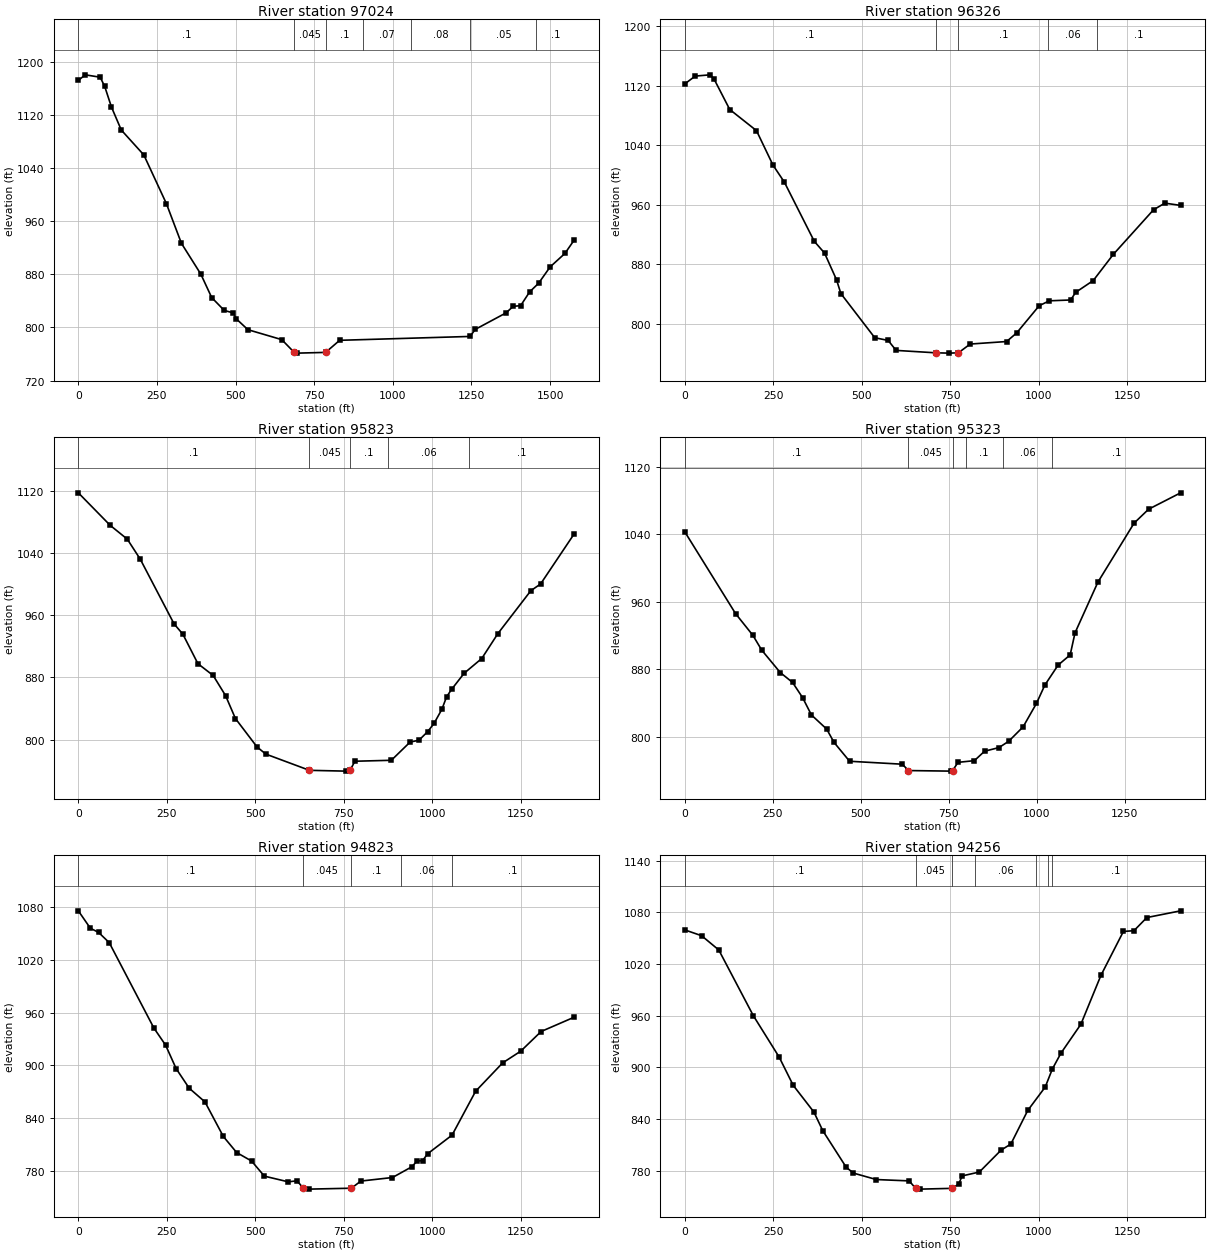
Type RM Length L Ch R = 1 ,97024   ,701.3,697.3,688.6
XS GIS Cut Line= 6
1654091.05634959458224.9922587321654261.65476168458327.130505894
1654429.05862634458427.7533361361654509.21102509458476.381191645
1654951.85121593458746.8832753041655069.21016955459304.559032291
#Sta/Elev= 30
       0 1171.72    22.2 1180.05    69.5 1176.46    83.9 1162.53   105.4 1131.49
   136.5 1097.06   208.3  1059.5     280  986.29   327.8  926.56   389.5  880.22
     424  845.02     464  825.62   492.7   821.9   502.2  812.99   539.2  796.67
   646.9  781.69   686.4762.5061   696.8  761.41   786.3762.5133   830.9  780.69
  1245.4  786.51  1262.1  797.14  1359.4   821.8  1382.8  831.82  1406.3   832.8
  1434.9  853.48  1463.3  866.45  1500.2  891.15  1547.1  911.34  1576.5  931.48
#Mann= 7 ,-1,0
       0      .1       0   686.4    .045       0   786.3      .1       0
   905.4     .07       0 1056.65     .08       0 1246.65     .05       0
 1456.65      .1       0
Bank Sta=686.4,786.3
XS Rating Curve= 0 ,0
Exp/Cntr(USF)=0,0
Exp/Cntr=0.3,0.1

Type RM Length L Ch R = 1 ,96326   ,506.3,503.3,501.9
XS GIS Cut Line= 6
1653735.14449731458943.5338543061653919.02142614459019.177075729
1654336.62820247459190.9713515641654579.38919988459290.838277817
 1654846.7151088459400.8101707251655030.59236573459476.453392148
#Sta/Elev= 30
       0 1122.16    29.4 1132.67    71.9 1134.35    82.6 1128.74     127 1087.81
   202.5 1059.45   249.3 1013.07   281.3  990.34   365.8  910.92   394.8  895.16
   428.7  859.28   440.9  840.83   536.7  781.54   574.5  777.91     597  764.54
   708.6  761.31     746  760.88     773761.3124   806.3  773.06   909.2  776.45
   937.6     788  1001.4  824.56  1029.8  831.08  1090.1   832.2  1104.3  842.43
    1154  858.32  1210.7  893.44  1324.2  953.22  1356.2  962.16  1400.8  959.12
#Mann= 5 ,-1,0
       0      .1       0   708.6    .045       0     773      .1       0
 1026.64     .06       0 1163.52      .1       0
Bank Sta=708.6,773
XS Rating Curve= 0 ,0
Exp/Cntr(USF)=0,0
Exp/Cntr=0.3,0.1

Type RM Length L Ch R = 1 ,95823   ,505.7,500.4,494.7
XS GIS Cut Line= 6
 1653544.9224368459405.9358166461653819.83461663459519.029094398
1653909.42498864459555.8843356371654475.86742531459788.906835482
 1654565.4577973459825.7620767211654840.36997713459938.855354473
#Sta/Elev= 30
       0 1117.08      90 1075.33   138.3  1057.6   174.9 1031.93   270.5  948.79
   295.4  935.52   337.9  897.68     381  882.54     416  856.67   443.8  827.29
   504.7  790.88   529.5  781.65     653760.7719   755.5  759.75   767.6760.7622
   781.4  772.45   884.3  773.67   937.5  797.14   962.3  799.39   987.2  810.57
  1004.9     821    1027  839.04  1040.4  855.16  1054.3   864.6    1090  885.43
  1139.7  904.34  1185.3  936.34  1278.3  991.34    1306 1000.08  1400.8 1064.34
#Mann= 5 ,-1,0
       0      .1       0     653    .045       0   767.6      .1       0
  875.39     .06       0 1103.52      .1       0
Bank Sta=653,767.6
XS Rating Curve= 0 ,0
Exp/Cntr(USF)=0,0
Exp/Cntr=0.3,0.1

Type RM Length L Ch R = 1 ,95323   ,477.4,500,512.8
XS GIS Cut Line= 6
1653390.59138064459857.5841915611653568.49095923 459956.39337714
1653658.06886405460000.3227512241653916.15758672460107.840252727
1653987.21223463460131.9911230651654705.76394714460348.254141971
#Sta/Elev= 30
       0 1042.89   144.2  946.11   193.4  920.43   218.4  902.98   271.2  876.38
   306.1  864.69   334.6  846.72   359.6  826.25     403  809.49   423.9  793.72
   468.1  771.42   617.9  767.94   635.3760.4261   755.4  759.75   760.8760.4485
     776  770.14   822.5  772.14   851.4  783.29   892.5  787.64     920  795.09
     961  812.19   998.7   839.8  1022.6  861.51  1060.3  885.21  1094.6  897.28
  1108.3  923.32  1173.4   983.4  1276.2 1053.23  1317.3 1069.64  1408.3 1089.04
#Mann= 6 ,-1,0
       0      .1       0   635.3    .045       0   760.8     .08       0
  797.94      .1       0  902.94     .06       0 1044.19      .1       0
Bank Sta=635.3,760.8
XS Rating Curve= 0 ,0
Exp/Cntr(USF)=0,0
Exp/Cntr=0.3,0.1

Type RM Length L Ch R = 1 ,94823   ,566.5,566.9,567.4
XS GIS Cut Line= 6
 1653147.2716573460149.2574927211653906.84330089460655.637713566
1653985.15810488460707.175340146 1654067.1891088460758.772677898
1654151.07804863460810.4001993091654321.17810214460913.692643642
#Sta/Elev= 30
       0 1076.16      34  1056.3      57 1051.64    87.3 1039.91   213.4  942.63
   246.6  923.06   276.5  896.22   313.3  873.96   357.8  858.38   409.8  818.93
   447.4  800.64   489.5  790.97   525.7  773.74   593.3  767.24     618  768.43
   635.9 759.999   651.1  758.94   771.7759.9818   798.3  768.13   887.7  772.18
   942.1  784.34   957.1   790.9   972.9  791.54   987.3  799.32  1056.1  820.51
  1122.7  870.54    1199  902.82  1250.1  916.19  1307.7  938.59  1401.1  954.91
#Mann= 5 ,-1,0
       0      .1       0   635.9    .045       0   771.7      .1       0
  912.89     .06       0 1056.64      .1       0
Bank Sta=635.9,771.7
XS Rating Curve= 0 ,0
Exp/Cntr(USF)=0,0
Exp/Cntr=0.3,0.1

Type RM Length L Ch R = 1 ,94256   ,435.7,434.3,433.6
XS GIS Cut Line= 6
1652887.22376414 460622.50048265 1653048.4878773460738.804055811
1653627.64485548461156.4908844841653703.68308922461211.329685555
1653782.25576673 461267.995910811654023.35994331461441.880077483
#Sta/Elev= 30
       0 1059.49    47.4 1052.77      96 1036.21   193.5  960.02   266.5  911.96
   306.3  879.11   364.8  848.07   389.9  826.43     456  784.05   476.2  777.29
   541.1  769.78     634  768.21   652.1 759.575   665.6  758.66   755.9759.5685
   773.7  764.59   783.6  773.99   832.2  778.52   893.6  803.93   921.2     811
   968.8  849.91  1018.3  877.18  1038.5  898.14  1062.7  916.45    1119  949.99
  1175.6 1006.68  1239.1 1057.69    1269 1058.59  1305.4 1073.84  1400.8 1081.63
#Mann= 7 ,-1,0
       0      .1       0   652.1    .045       0   755.9      .1       0
  820.39     .06       0  992.89      .1       0 1026.64     .06       0
 1036.64      .1       0
Bank Sta=652.1,755.9
XS Rating Curve= 0 ,0
Exp/Cntr(USF)=0,0
Exp/Cntr=0.3,0.1

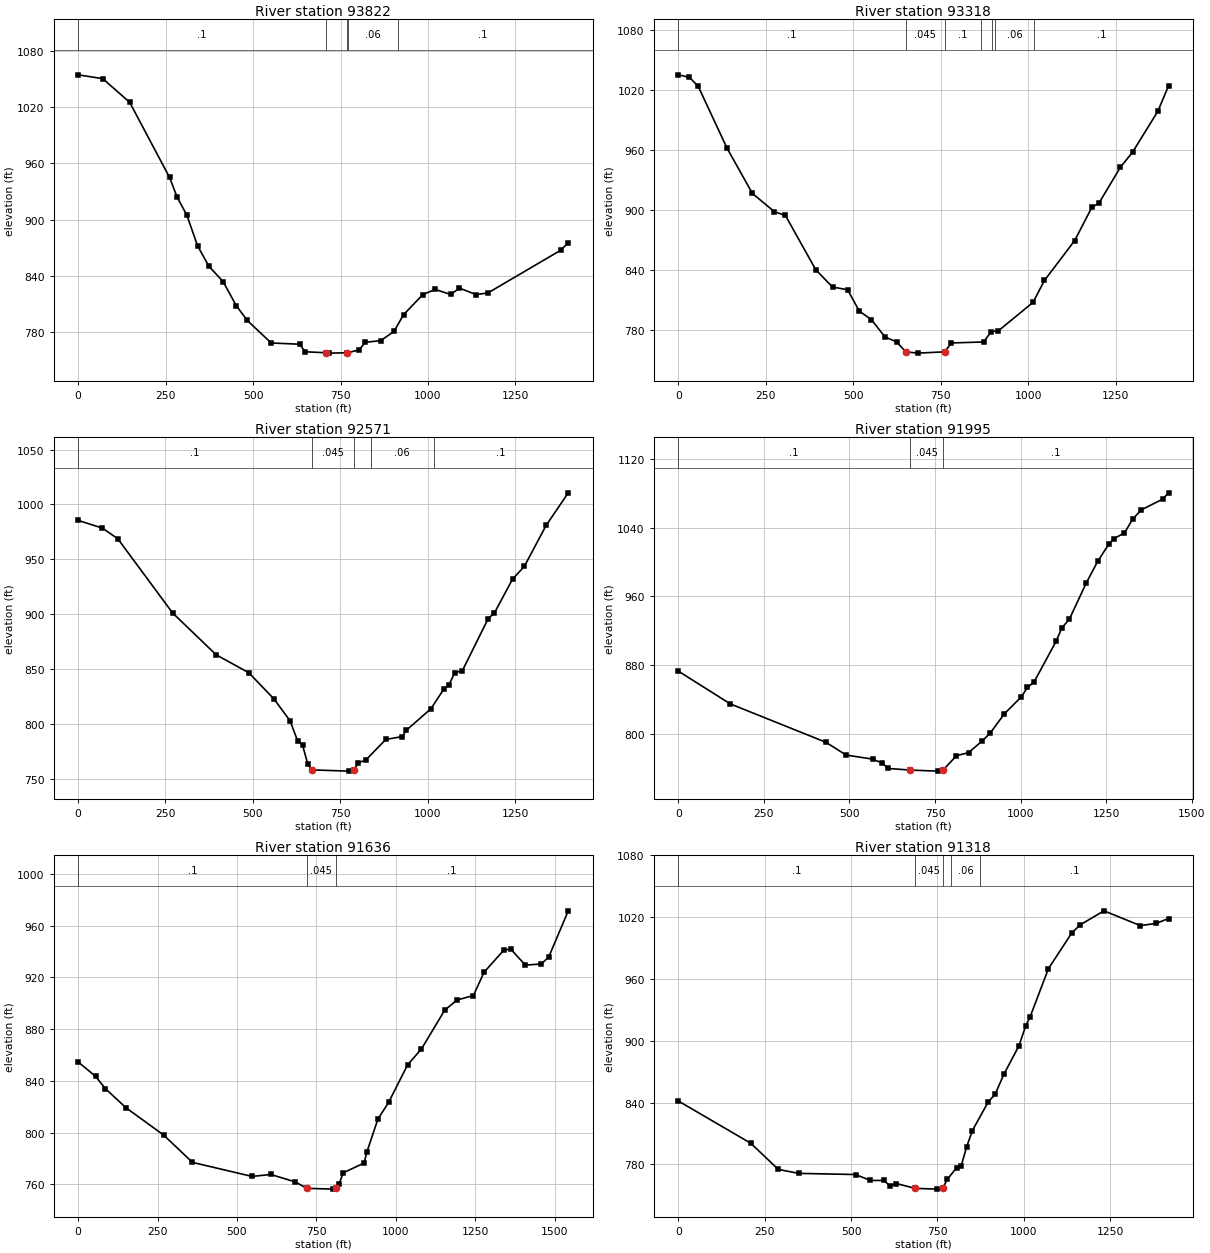
Type RM Length L Ch R = 1 ,93822   ,504.3,503.5,502.5
XS GIS Cut Line= 6
 1652622.3632583 460965.910386981653089.04703622461302.482220396
1653149.87762322461346.3528675591653438.82258339  461554.7395899
1653517.39526089461611.4058151391653758.49943747461785.289981812
#Sta/Elev= 30
       0 1054.37    70.6  1050.3   147.5 1025.12   261.6  945.04   282.7  924.47
   310.9  904.92   341.6  872.21     374  850.45   414.5  834.24   451.9   808.7
   483.2  792.95     552  768.82   632.9   767.5   649.1  759.44   709.3758.3982
   717.5  758.01   768.9758.3958   802.8   761.3   820.9  769.53   865.1  771.35
   903.1   781.2   930.1  798.91   985.4  820.42  1020.6  825.83  1064.7  820.51
    1090  827.22  1137.6  820.31  1171.3  822.12  1378.8  867.47  1400.8  875.55
#Mann= 5 ,-1,0
       0      .1       0   709.3    .045       0   768.9      .1       0
  770.39     .06       0  912.89      .1       0
Bank Sta=709.3,768.9
XS Rating Curve= 0 ,0
Exp/Cntr(USF)=0,0
Exp/Cntr=0.3,0.1

Type RM Length L Ch R = 1 ,93318   ,751.4,746.9,741.9
XS GIS Cut Line= 6
1652326.63747181461328.3574967241653115.88884605461953.183346808
1653191.84309047462013.3144601431653268.71662439462074.801213816
1653345.21187823462138.0245125591653421.51815605462202.116247892
#Sta/Elev= 30
       0 1035.45    31.8 1032.96    56.9 1023.84   139.3  961.95   211.7   916.7
   274.5  898.39   305.9  894.66     393  840.18   440.6  823.02   483.7  820.24
   517.2  798.86   551.6  790.41   590.8  772.86   623.5  768.15     650758.1135
   683.7  756.81   761.4758.1068     780     767   872.9  767.99   893.8  778.37
   914.7   779.2  1013.5   807.6  1046.2  829.57  1132.4  869.41  1181.6  902.68
    1202     907  1262.9  942.73  1298.2   958.1  1370.4  999.05  1400.8  1024.4
#Mann= 7 ,-1,0
       0      .1       0     650    .045       0   761.4      .1       0
  865.39     .06       0  895.39      .1       0  905.39     .06       0
 1016.64      .1       0
Bank Sta=650,761.4
XS Rating Curve= 0 ,0
Exp/Cntr(USF)=0,0
Exp/Cntr=0.3,0.1

Type RM Length L Ch R = 1 ,92571   ,576.7,576,573.7
XS GIS Cut Line= 6
 1651867.8011788462038.9700951031652292.69862297462281.181552936
1652368.61251314462325.0538405231652433.28101897462363.259144683
1652517.06398788462417.861725767 1653058.2220263462778.633642023
#Sta/Elev= 30
       0  985.51    69.6  978.45   113.6  968.76   270.4  901.09     395  862.93
   488.9  846.43   560.9  822.43   606.4  802.74     628  784.49   642.3  780.53
   656.6  763.73   669.2  757.91   773.8  756.78   790.2757.9229   801.4  764.44
   822.5  766.69   880.3  785.67   927.6   788.3   939.4  794.17  1009.4  813.65
  1047.2  831.99  1061.6  835.69  1077.4  846.58  1099.3  848.34  1173.4  895.95
  1191.2  901.14    1243  931.92  1276.7  943.57    1339  980.91  1402.3 1010.63
#Mann= 5 ,-1,0
       0      .1       0   669.2    .045       0   790.2      .1       0
  836.88     .06       0 1018.13      .1       0
Bank Sta=669.2,790.2
XS Rating Curve= 0 ,0
Exp/Cntr(USF)=0,0
Exp/Cntr=0.3,0.1

Type RM Length L Ch R = 1 ,91995   ,343.4,359.2,378.5
XS GIS Cut Line= 6
1651685.27223996462413.9507935151651817.59907506462593.310999106
1651890.48213139462666.306916098 1652113.6782073462835.947652932
1652259.28749613462933.736827429 1652822.4386008463259.112160932
#Sta/Elev= 30
       0  872.97   151.9  834.77   431.7  789.97   490.2  775.17   567.5  770.44
   595.6  765.88   612.7  759.57     677757.6855   757.5  756.44   773.7757.6851
   812.8  774.43   847.9  777.94   888.1  791.63   912.1  801.15   952.9  823.32
  1002.3     843  1020.2  853.98  1039.4  860.23  1103.6  907.55    1121  923.55
  1142.7  933.53  1191.7  975.45  1225.8 1001.09  1257.9 1020.88  1272.3  1027.3
  1303.6 1033.84  1327.6 1050.07  1352.8 1060.81  1415.3 1073.36  1432.4 1080.69
#Mann= 3 ,-1,0
       0      .1       0     677    .045       0   773.7      .1       0
Bank Sta=677,773.7
XS Rating Curve= 0 ,0
Exp/Cntr(USF)=0,0
Exp/Cntr=0.3,0.1

Type RM Length L Ch R = 1 ,91636   ,292.9,317.9,343.4
XS GIS Cut Line= 4
1651654.36183178462495.2069374681651801.69874637462928.798428968
1652060.59075343463284.5118370431652694.13948616463402.381368713
#Sta/Elev= 30
       0  854.69    54.9  843.58    85.6  834.12   150.5  819.32   269.2  798.18
     360  777.06   547.5  766.22   606.3  767.72   683.3  761.99   719.8  757.04
   801.4  756.41   810.5  756.99   821.3  760.29     834  768.96   900.2  776.62
   908.4  784.82   943.6  810.64     977  823.35    1037  852.47  1080.4  864.66
  1153.8  894.71  1192.8  902.51  1243.9  905.96  1277.4  923.93  1339.1   940.9
  1360.7  941.95  1407.4  929.44  1457.5  930.31  1480.9  935.67  1542.3  971.36
#Mann= 3 ,-1,0
       0      .1       0   719.8    .045       0   810.5      .1       0
Bank Sta=719.8,810.5
XS Rating Curve= 0 ,0
Exp/Cntr(USF)=0,0
Exp/Cntr=0.3,0.1

Type RM Length L Ch R = 1 ,91318   ,491.2,500,514.9
XS GIS Cut Line= 6
1651566.61635405462561.7142819761651615.87445764462661.698662058
1651653.61027455462759.8310117271651666.04955414462857.835736975
1651680.75096831463210.6545851381651711.99237564463960.394555479
#Sta/Elev= 30
       0  841.64   209.7  800.61   289.5   775.2   348.8  771.37     513  770.27
   555.7  764.53   595.1  764.49   611.5  759.54   631.2   761.5   685.7756.8387
   749.4  756.09   764.8756.8331   778.9  765.76   805.2  776.73   818.3  778.19
   834.8  797.37   851.2  812.96   897.1  840.82   916.9  848.11   943.1  868.12
   985.8  895.09  1005.5  914.55  1018.6  923.58  1071.2  970.04  1138.5 1004.55
  1163.1 1012.59  1232.1  1026.2  1337.2 1011.85  1383.1 1013.99  1418.9 1018.73
#Mann= 5 ,-1,0
       0      .1       0   685.7    .045       0   764.8      .1       0
  788.51     .06       0  873.51      .1       0
Bank Sta=685.7,764.8
XS Rating Curve= 0 ,0
Exp/Cntr(USF)=0,0
Exp/Cntr=0.3,0.1

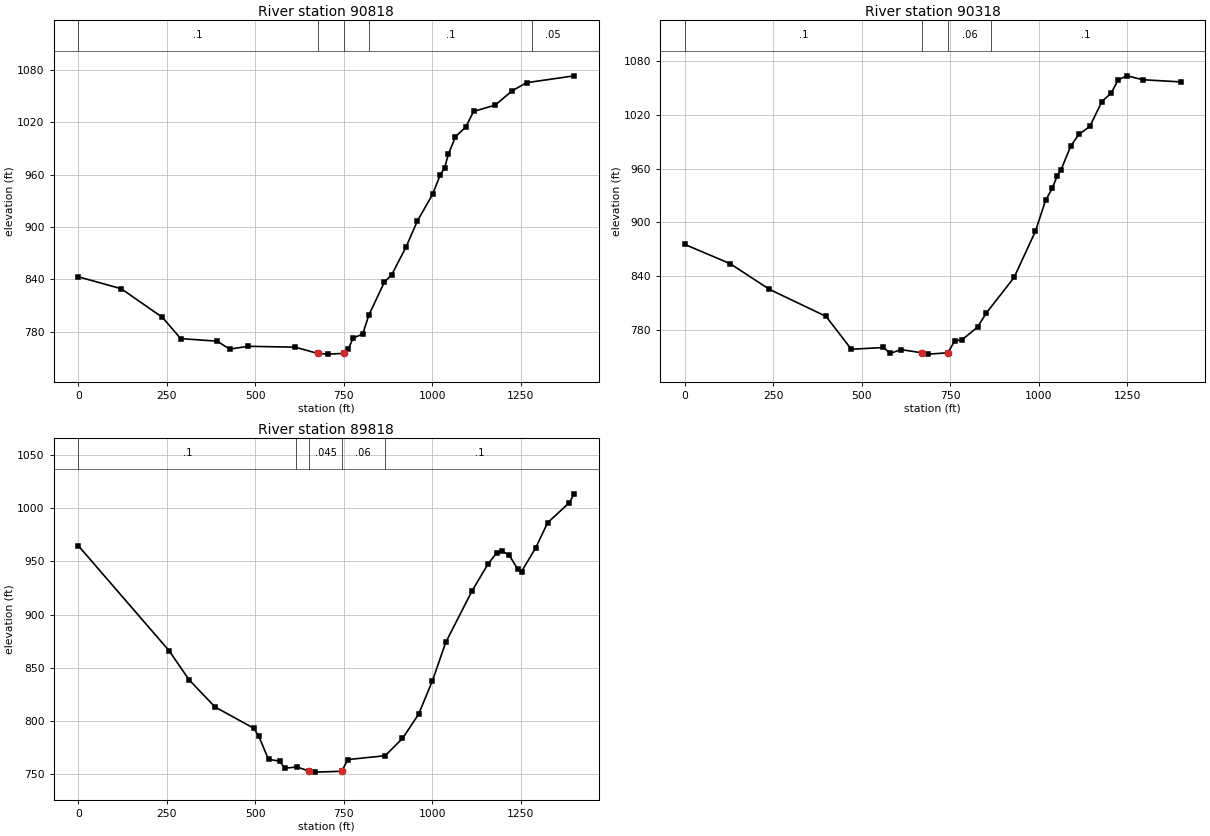
Type RM Length L Ch R = 1 ,90818   ,496.1,500,505.9
XS GIS Cut Line= 6
1651383.39034255462539.1536315531651324.91670622462729.282844484
1651296.41610706462823.5369210541651269.09332706462916.494412303
1651244.12651347463006.8590609731651002.06991097 463887.07350789
#Sta/Elev= 30
       0   842.8   121.2   829.1   237.8  796.22   289.2  771.94   392.6  768.99
   427.2  759.93   480.5  763.13   613.1  762.12   676.1754.9843   705.3  754.16
   750.9754.9991   762.8  760.02   776.4  772.62   803.5  777.17   820.6  798.68
   864.8   836.8   885.3  845.08   926.1   877.1   958.2  906.96  1000.9  937.24
  1022.3  959.35    1035  967.71  1045.2     983  1065.6 1003.41  1094.9 1014.52
  1116.6 1032.27  1177.9 1039.57  1225.5 1055.88  1266.4 1065.22  1400.9 1073.09
#Mann= 5 ,-1,0
       0      .1       0   676.1    .045       0   750.9     .06       0
  820.53      .1       0 1282.09     .05       0
Bank Sta=676.1,750.9
XS Rating Curve= 0 ,0
Exp/Cntr(USF)=0,0
Exp/Cntr=0.3,0.1

Type RM Length L Ch R = 1 ,90318   ,502.7,500.4,498.3
XS GIS Cut Line= 6
1650986.78811739462412.2103158981650870.51505597462685.793102056
1650663.94460297463171.842982978 1650629.7196058463252.372021392
1650555.15873131463427.8103188131650438.88599797463701.392776892
#Sta/Elev= 30
       0  875.25   127.6  853.91   238.8   825.2   399.2  794.89   470.5  758.22
   560.4  760.21   581.1  753.72   610.4  757.88  669.71754.3066   688.1  752.81
  742.97  754.25   762.9  767.66     783  768.75     827  782.99     852  798.77
   930.4  838.43   990.7   890.1  1019.5   924.8  1038.2  937.87  1051.6  951.39
  1062.3  958.05  1090.7  985.29  1113.2  998.08  1144.3 1006.96  1178.3 1034.72
  1204.9 1044.39  1224.7 1059.13  1249.9 1063.48    1294  1059.1  1400.8 1056.73
#Mann= 4 ,-1,0
       0      .1       0  669.71    .045       0  742.97     .06       0
  865.39      .1       0
Bank Sta=669.71,742.97
XS Rating Curve= 0 ,0
Exp/Cntr(USF)=0,0
Exp/Cntr=0.3,0.1

Type RM Length L Ch R = 1 ,89818   ,503.7,500.2,499.8
XS GIS Cut Line= 6
1650498.74578638462215.5338719791650292.62940072462753.343491897
1650266.18129089462823.5844931451650231.44481181462917.369738638
1650204.67944539462987.4243885581650002.09815764463525.664125726
#Sta/Elev= 30
       0  964.53   256.4  866.07   312.8   838.8   386.1  813.29   495.3  793.37
   509.3  786.28   537.4  764.02     569   762.5     583  755.74   618.1  756.97
   652.9 752.934   668.8  752.12   744.3752.9203   761.6  763.91   866.9   767.5
     916  783.69   961.6  806.47  1000.6   837.8  1038.1  873.75    1112  921.82
  1157.9  947.43  1182.4  957.96  1196.4  959.63  1217.5  955.77    1242  942.39
  1252.5  940.29  1292.9  962.87  1326.1  986.17  1387.1 1004.75  1401.1 1013.23
#Mann= 5 ,-1,0
       0      .1       0  615.95     .08       0   652.9    .045       0
   744.3     .06       0  866.01      .1       0
Bank Sta=652.9,744.3
XS Rating Curve= 0 ,0
Exp/Cntr(USF)=0,0
Exp/Cntr=0.3,0.1