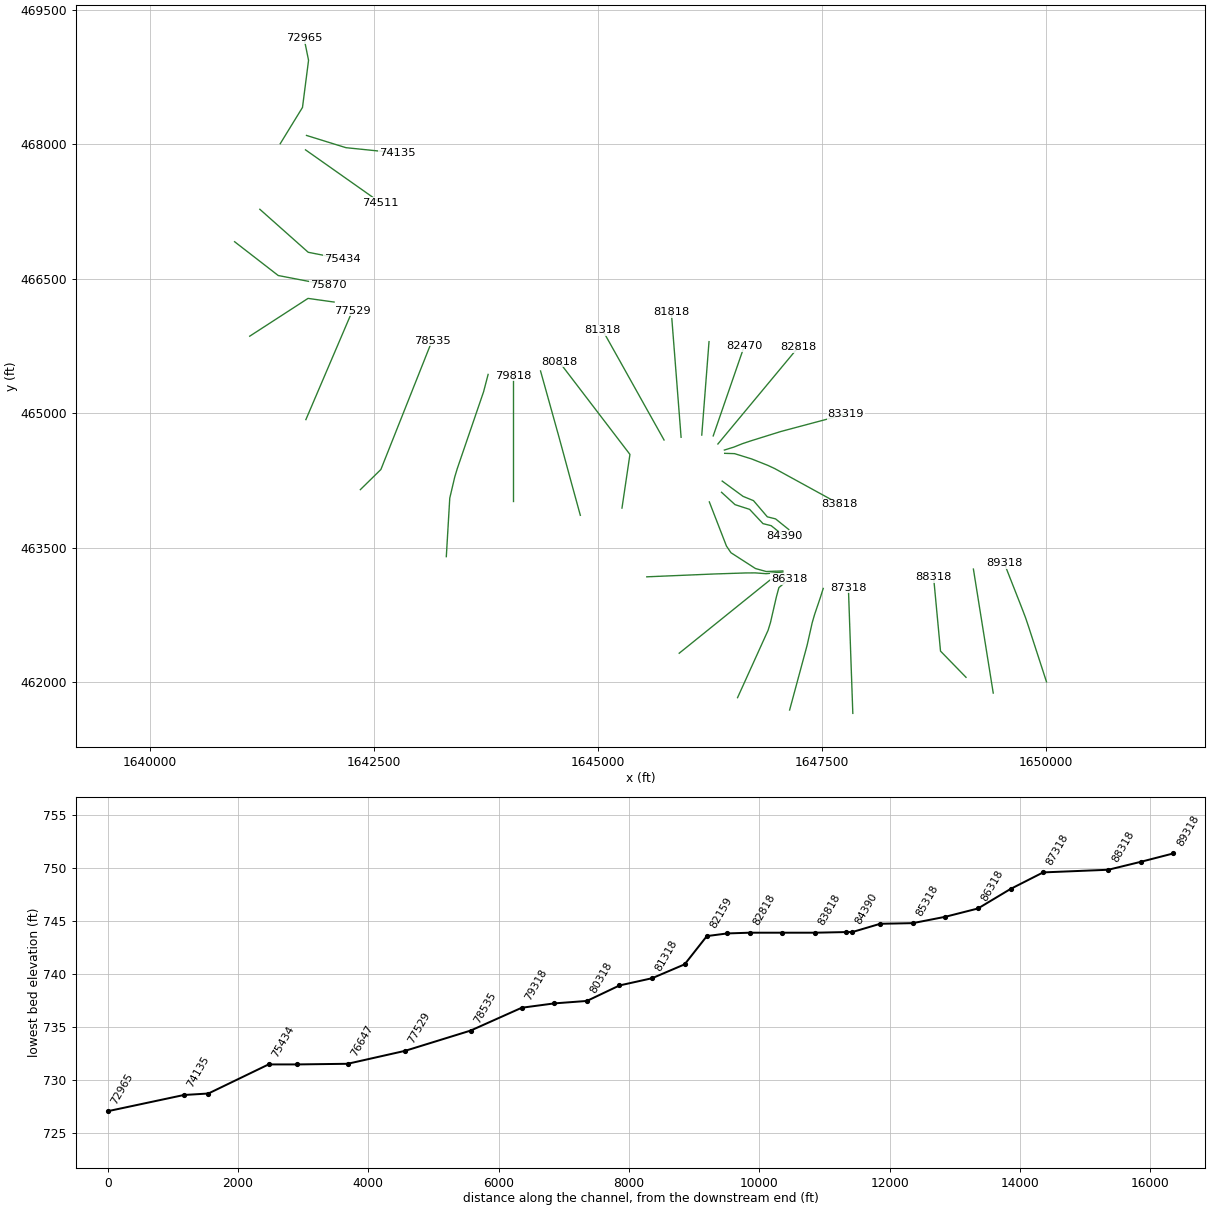
HEC-RAS study FshCrk.prj: FshCrk

--- FshCrk.g01 (geometry) --- (continued)

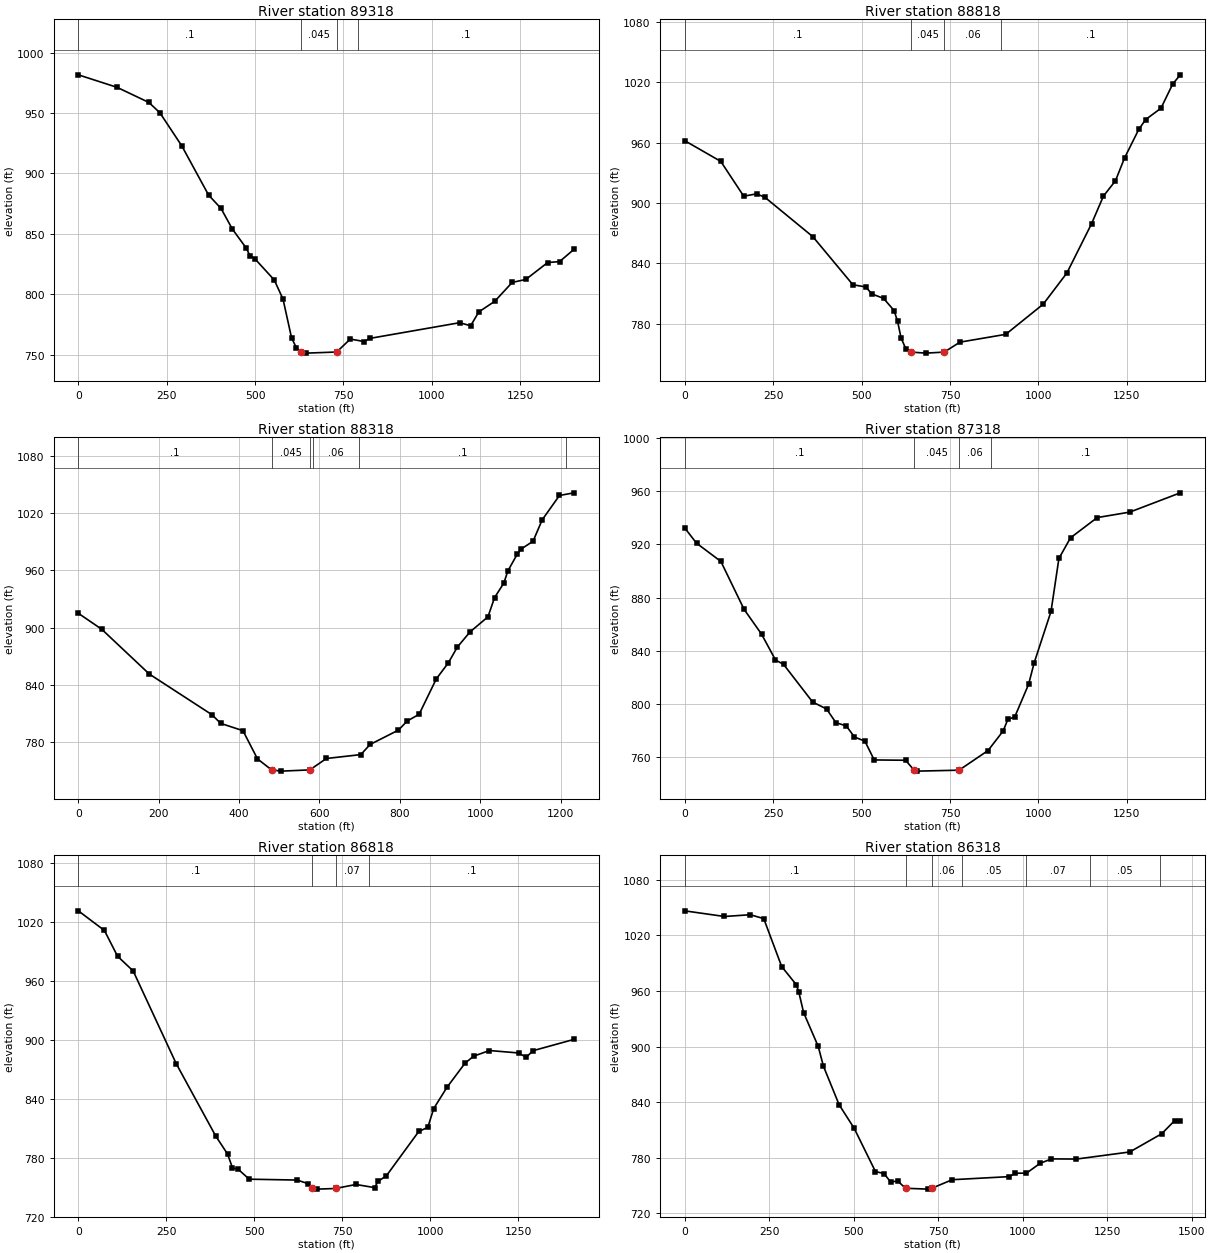
Type RM Length L Ch R = 1 ,89318   ,510.3,499.4,494.1
XS GIS Cut Line= 6
1650009.15555821462002.737709641 1649808.1287293462621.281091973
1649776.09401648462716.0187633931649749.43527713462786.216129556
1649717.73783398462867.9193782211649538.93963514463322.820699394
#Sta/Elev= 30
       0  981.63   109.7  971.27   199.4   958.8   230.5  950.31   292.6  922.86
   368.5  882.12   403.6   871.1   435.4  854.13   475.4   838.1   485.7  831.69
   499.5   829.4   554.1  811.92   578.9  796.11     603  764.16   616.8  755.68
   630.2752.2861   644.4  751.38   730.6752.2935   769.3  763.03   807.9  760.98
   825.1   763.6  1078.4  776.55  1109.6  774.03  1132.8   785.5  1177.8  794.26
  1227.1  809.87  1265.7  812.35  1327.6  826.36  1361.1  827.08  1401.9  837.25
#Mann= 4 ,-1,0
       0      .1       0   630.2    .045       0   730.6     .06       0
   790.4      .1       0
Bank Sta=630.2,730.6
XS Rating Curve= 0 ,0
Exp/Cntr(USF)=0,0
Exp/Cntr=0.3,0.1

Type RM Length L Ch R = 1 ,88818   ,502.7,500,496.5
XS GIS Cut Line= 6
1649414.98909564461876.8829744761649312.23437989462519.105443314
1649255.95037173462870.881314561 1649225.0924938463063.740836978
 1649209.4173283463161.7134100651649193.67982697463260.071809143
#Sta/Elev= 30
       0  962.06   102.2  941.38   167.1  906.74   203.2  909.06   226.5  905.77
   362.7  866.36   475.6   818.6   512.2  816.46   528.8  809.53   562.1  805.11
     592  792.98   601.9   782.1   611.9   765.5   625.2  754.94   640.4751.6047
   681.7  750.59   733.7751.6062     778   761.5   907.6  769.29  1013.6  799.35
  1080.4  830.36  1150.2  879.43  1183.6  906.83  1217.6  922.06  1243.3  944.78
  1283.4  973.16    1303  983.03  1346.2  994.29  1379.4 1018.34  1400.8 1027.52
#Mann= 4 ,-1,0
       0      .1       0   640.4    .045       0   733.7     .06       0
  895.39      .1       0
Bank Sta=640.4,733.7
XS Rating Curve= 0 ,0
Exp/Cntr(USF)=0,0
Exp/Cntr=0.3,0.1

Type RM Length L Ch R = 1 ,88318   ,1002.7,1000,994.9
XS GIS Cut Line= 6
1649111.31848236462052.6299551261648826.76028521462344.936500311
1648795.25772355462680.9630592321648786.50741297462774.303751811
1648759.01435772463067.5492283111648749.43662097463166.697652057
#Sta/Elev= 30
       0  915.07    58.1  898.39   176.7  851.44   332.4  808.91   354.4  799.78
   409.6  792.19   445.8  762.64   480.9751.1246   505.2  749.84     576751.1237
   617.2  763.06   702.9  767.14   725.9  777.72   796.6  792.81   818.2  802.27
   847.9   809.3   890.7  846.38   920.4  863.04   943.4  879.89   974.7  895.56
  1019.2  911.36  1035.7  931.52  1058.8   946.7  1068.6   959.3  1091.7  976.64
  1101.6   982.3  1131.4  990.45  1154.3 1012.99  1197.2  1038.4  1233.3 1041.17
#Mann= 6 ,-1,0
       0      .1       0   480.9    .045       0     576     .08       0
  582.94     .06       0  697.94      .1       0 1213.72     .05       0
Bank Sta=480.9,576
XS Rating Curve= 0 ,0
Exp/Cntr(USF)=0,0
Exp/Cntr=0.3,0.1

Type RM Length L Ch R = 1 ,87318   ,511.5,500,490.5
XS GIS Cut Line= 6
1647848.12543148461650.3335588131647837.64120047461947.414329484
1647825.18584481462300.3194635661647819.01361306462475.210846066
 1647809.2035933462753.162717983 1647798.7193623463050.243160561
#Sta/Elev= 30
       0  932.38    33.6  920.83   102.5   907.1   168.1  871.11   217.4   852.5
   256.8  833.12   279.8  829.73   361.8  801.49   401.2  796.27   427.5  786.04
     457  783.52     480  775.22   509.6  772.09   535.8     758   624.5  757.75
   648.7750.2846   657.3  749.59   775.5 750.288   857.5  765.05   900.2  779.73
   913.4  788.39   933.1  790.39   972.1  814.76   987.9  830.96  1035.5  869.56
  1057.8  909.33  1090.6  924.85  1166.1  940.05  1258.1  944.16  1400.8  958.64
#Mann= 4 ,-1,0
       0      .1       0   648.7    .045       0   775.5     .06       0
  865.39      .1       0
Bank Sta=648.7,775.5
XS Rating Curve= 0 ,0
Exp/Cntr(USF)=0,0
Exp/Cntr=0.3,0.1

Type RM Length L Ch R = 1 ,86818   ,506,500.1,492.7
XS GIS Cut Line= 6
1647142.90407288461687.801331639 1647338.6887863462412.200801477
1647395.04037964462662.4145398891647422.47372372 462756.08889322
1647487.14518231462946.5435648111647517.86821797463043.867845222
#Sta/Elev= 30
       0 1031.58    74.1 1011.56   111.5  985.27   155.7  970.35     278  875.88
   390.1  802.19   423.8  783.81   437.7  769.81   454.7  768.03   485.4  758.15
   621.2  757.27   651.8  753.71     665748.7012     679  748.03   730.4 748.694
   788.5  752.77   841.3  749.58   851.4  756.04     875  761.64   966.9  806.79
   992.5  810.94  1009.4  830.16    1047  851.77  1098.1  876.28  1122.5  883.44
  1167.6  889.25  1250.7  886.75  1271.5  882.38  1292.2  889.16  1407.7  900.59
#Mann= 4 ,-1,0
       0      .1       0     665    .045       0   730.4     .07       0
  825.43      .1       0
Bank Sta=665,730.4
XS Rating Curve= 0 ,0
Exp/Cntr(USF)=0,0
Exp/Cntr=0.3,0.1

Type RM Length L Ch R = 1 ,86318   ,520.6,499.9,483.7
XS GIS Cut Line= 6
1646562.00169139461825.7738247221646902.69228297462577.297256067
1646928.84216505462662.0762859731646995.99426173462953.274522483
1647023.51520406463053.8008962271647138.20395106463149.539221808
#Sta/Elev= 30
       0 1046.47   117.9 1040.36   194.4 1042.26   234.1 1038.05   287.2  986.33
   330.5  966.73   337.7  959.05   352.1  936.62   395.2  900.24   410.8  878.74
   457.1  837.26   501.8  811.71   564.6  765.13   589.8  763.03   609.4  753.97
   630.6  754.94   653.5  747.13   719.8  746.19   731.4747.1323   791.7  756.35
   960.7  759.69   977.6  763.34  1011.4  763.44  1051.7  774.03  1085.4  778.82
  1159.3  778.63    1317  786.29  1411.4  805.93  1449.5  819.99  1466.4  820.11
#Mann= 7 ,-1,0
       0      .1       0   653.5    .045       0   731.4     .06       0
  820.06     .05       0 1010.11     .07       0 1200.47     .05       0
 1406.96     .06       0
Bank Sta=653.5,731.4
XS Rating Curve= 0 ,0
Exp/Cntr(USF)=0,0
Exp/Cntr=0.3,0.1

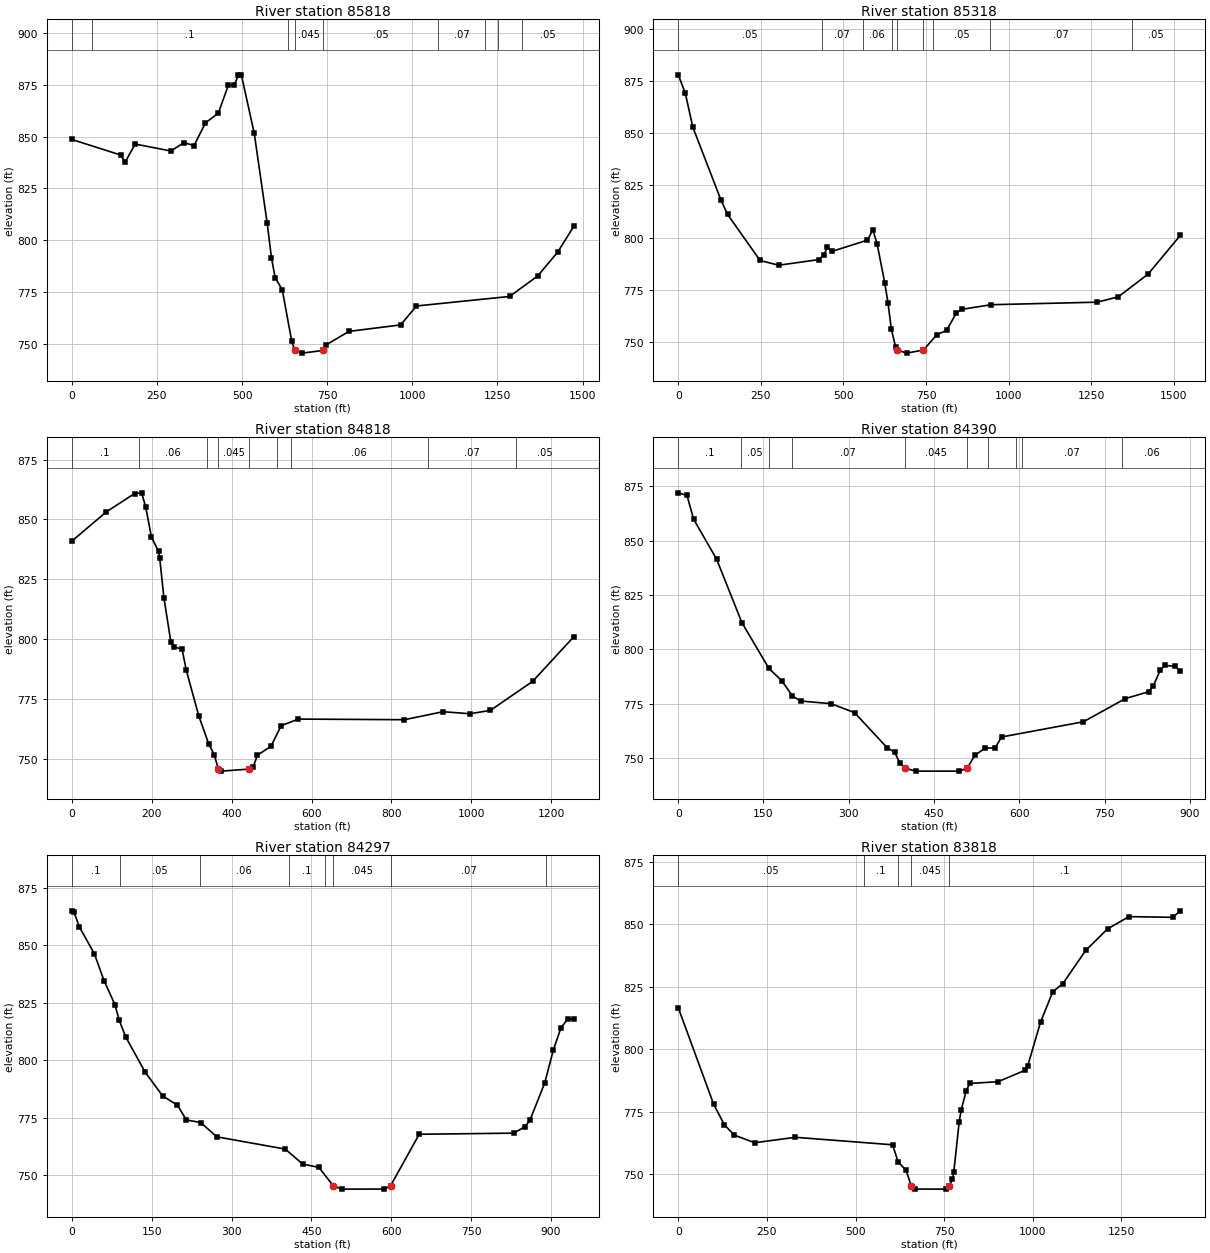
Type RM Length L Ch R = 1 ,85818   ,524.5,499.8,474.1
XS GIS Cut Line= 6
1645910.78613031 462321.39816156 1645988.4552663 462383.82323356
1646694.50175448462953.212514728 1646846.5362273463075.819552973
1646924.10267322463137.6914764791647088.49768564463191.484347895
#Sta/Elev= 30
       0  848.62   143.9  841.08   156.5   837.6   186.1  846.39   291.2  843.04
   329.4  847.08   358.9  845.68   392.6  856.59   430.5  861.37     460  874.96
   476.9  874.84   489.5   879.7   497.9  879.83   535.9   851.5   573.6  808.37
   586.4   791.4   597.2  781.87     618  776.06     646  751.05   655.3  746.69
     675  745.41   738.3746.6918   746.6  749.38   813.9  755.91   965.6  759.04
  1012.1  768.18  1285.7  772.79  1367.9  782.67  1426.6  794.16  1474.2   806.7
#Mann= 9 ,-1,0
       0     .05       0      60      .1       0  635.43     .06       0
   655.3    .045       0   738.3     .05       0 1076.68     .07       0
 1211.99     .08       0 1251.99     .07       0 1321.21     .05       0
Bank Sta=655.3,738.3
XS Rating Curve= 0 ,0
Exp/Cntr(USF)=0,0
Exp/Cntr=0.3,0.1

Type RM Length L Ch R = 1 ,85318   ,545,500.2,446.1
XS GIS Cut Line= 6
1645548.95712955463173.5604992211646299.77682213463205.339635149
1646652.61469914463216.8153339771646759.92583622463217.373403728
1646880.79731363463208.4682378171647066.84516989 463226.87305665
#Sta/Elev= 30
       0  877.94    21.2  869.28    44.2  852.89   129.6  817.94   149.3  811.16
   247.8  789.14   303.7  786.86   425.1  789.53   441.5  791.83   451.4  795.55
   464.4  793.43   572.9  798.86   589.3  803.79   602.4  796.87   625.2  778.37
   635.3  768.59   645.1  756.28   658.2  747.66   663.7 746.295   691.1  744.81
   742.3746.2906     783  753.62   812.6  755.69   842.1  764.08   857.8  765.74
   947.2  767.97  1268.9  769.19  1332.4  771.75  1422.5  782.63    1520  801.12
#Mann= 9 ,-1,0
       0     .05       0  434.75     .07       0  558.67     .06       0
  646.33      .1       0   663.7    .045       0   742.3      .1       0
   771.5     .05       0  943.99     .07       0 1373.04     .05       0
Bank Sta=663.7,742.3
XS Rating Curve= 0 ,0
Exp/Cntr(USF)=0,0
Exp/Cntr=0.3,0.1

Type RM Length L Ch R = 1 ,84818   ,410.2,428.3,445.8
XS GIS Cut Line= 6
1646246.88158672464009.413486317 1646437.9169658463517.043408066
1646488.38241605463442.3509721461646761.85004497 463266.05408065
1646881.75958206463232.8084122241647067.32614006463239.042979807
#Sta/Elev= 30
       0   840.9    86.7  853.18   157.2  860.81   174.7  861.11   185.2   855.1
   199.3  842.65   217.2   836.6   220.1  833.76   230.6  817.22   248.1  798.67
   255.1  796.71   276.1  795.77   286.5  786.97     318  767.77   342.4  756.25
   356.4  751.66   366.9   745.6   373.9  744.75   444.4745.6024   454.3  746.62
   464.7  751.43   498.5  755.11   524.1  763.77   567.1  766.51   832.6  766.25
   929.1  769.59   996.7  768.74  1047.8  770.16  1153.6  782.31  1256.5  800.96
#Mann= 9 ,-1,0
       0      .1       0  167.23     .06       0  338.48      .1       0
   366.9    .045       0   444.4      .1       0  513.48     .05       0
  548.48     .06       0  890.53     .07       0 1110.82     .05       0
Bank Sta=366.9,444.4
XS Rating Curve= 0 ,0
Exp/Cntr(USF)=0,0
Exp/Cntr=0.3,0.1

Type RM Length L Ch R = 1 ,84390   ,95.4,92.6,90.2
XS GIS Cut Line= 6
1646383.20943246464116.4507442411646534.02063253463978.620044218
1646696.44442683463926.1194238381646845.74306604463766.976918311
 1646937.6191517463744.0078968951647085.09716051463625.184289155
#Sta/Elev= 30
       0  872.01    15.4  870.83      27   859.9    67.5  841.49   111.9  812.35
   159.4  791.27   182.2  785.54   200.8   778.6   215.1  776.23   268.9  775.01
   310.1  770.89   367.5  754.75   380.7  752.68     390  747.65   398.3  745.43
   417.5  743.97   494.7  743.97   508.6  745.41   521.7  751.24   539.7  754.51
   557.7  754.72   568.8  759.67   712.8  766.68   786.7  777.35   827.8  780.51
     836  783.32   848.3  790.58   856.5   792.6   874.2  792.18   883.3  789.86
#Mann= 10 ,-1,0
       0      .1       0     110     .05       0     160      .1       0
     200     .07       0   398.3    .045       0   508.6     .05       0
  545.75     .07       0  593.97     .05       0  603.97     .07       0
  781.48     .06       0
Bank Sta=398.3,508.6
XS Rating Curve= 0 ,0
Exp/Cntr(USF)=0,0
Exp/Cntr=0.3,0.1

Type RM Length L Ch R = 1 ,84297   ,459.5,479.1,498.3
XS GIS Cut Line= 6
1646390.56638095464241.6197196581646623.40980037464070.976131897
1646739.89555184464023.3974446781646894.11612421463842.926562121
1646985.99220987463819.9575407051647133.47021868463701.133932965
#Sta/Elev= 30
       0  864.91     3.8  864.54    14.5  857.83    42.3  846.32    60.8  834.46
    81.1  824.12    89.2  817.27   101.4  810.05     138  794.75   170.6   784.5
   198.5  780.43   215.3  774.03   242.1  772.92   272.3   766.7   400.9  761.37
   433.6  754.88   464.1   753.4   491.2745.4285   507.2  743.97   587.3     744
   598.6745.3945   652.5  767.81   829.6   768.3   851.5  771.12   860.7  774.07
   888.2  790.12   904.3  804.36   918.7  814.09   931.6  817.96   942.9  817.74
#Mann= 8 ,-1,0
       0      .1       0      90     .05       0     240     .06       0
  407.92      .1       0  476.18     .07       0   491.2    .045       0
   598.6     .07       0  891.08      .1       0
Bank Sta=491.2,598.6
XS Rating Curve= 0 ,0
Exp/Cntr(USF)=0,0
Exp/Cntr=0.3,0.1

Type RM Length L Ch R = 1 ,83818   ,453.3,499.5,533.9
XS GIS Cut Line= 6
1646418.31857981464551.2106310581646528.60477656 464547.69128114
1646720.04533856464488.3226334751646898.51643831464417.453024566
1646978.00381213464380.4248833951647701.71693164 463983.55067715
#Sta/Elev= 30
       0  816.63     100  777.87   130.3  769.67   157.6   765.6   215.6  762.49
   330.1  764.68   604.6  761.68   620.1  754.81   642.5   751.5   656.9745.3257
   668.7  743.94   754.8  743.91   764.3745.3386   773.5  747.81   777.2  750.86
   792.2  770.62   797.9  775.58   812.4  783.39   822.1  786.25   901.9  786.96
     979  791.57   985.8  793.38  1021.8  810.84  1056.5  823.05  1084.1  826.15
  1149.6  839.64    1211   848.2  1271.2  853.11  1394.6  852.83    1416  855.43
#Mann= 5 ,-1,0
       0     .05       0  522.91      .1       0   620.6     .08       0
   656.9    .045       0   764.3      .1       0
Bank Sta=656.9,764.3
XS Rating Curve= 0 ,0
Exp/Cntr(USF)=0,0
Exp/Cntr=0.3,0.1

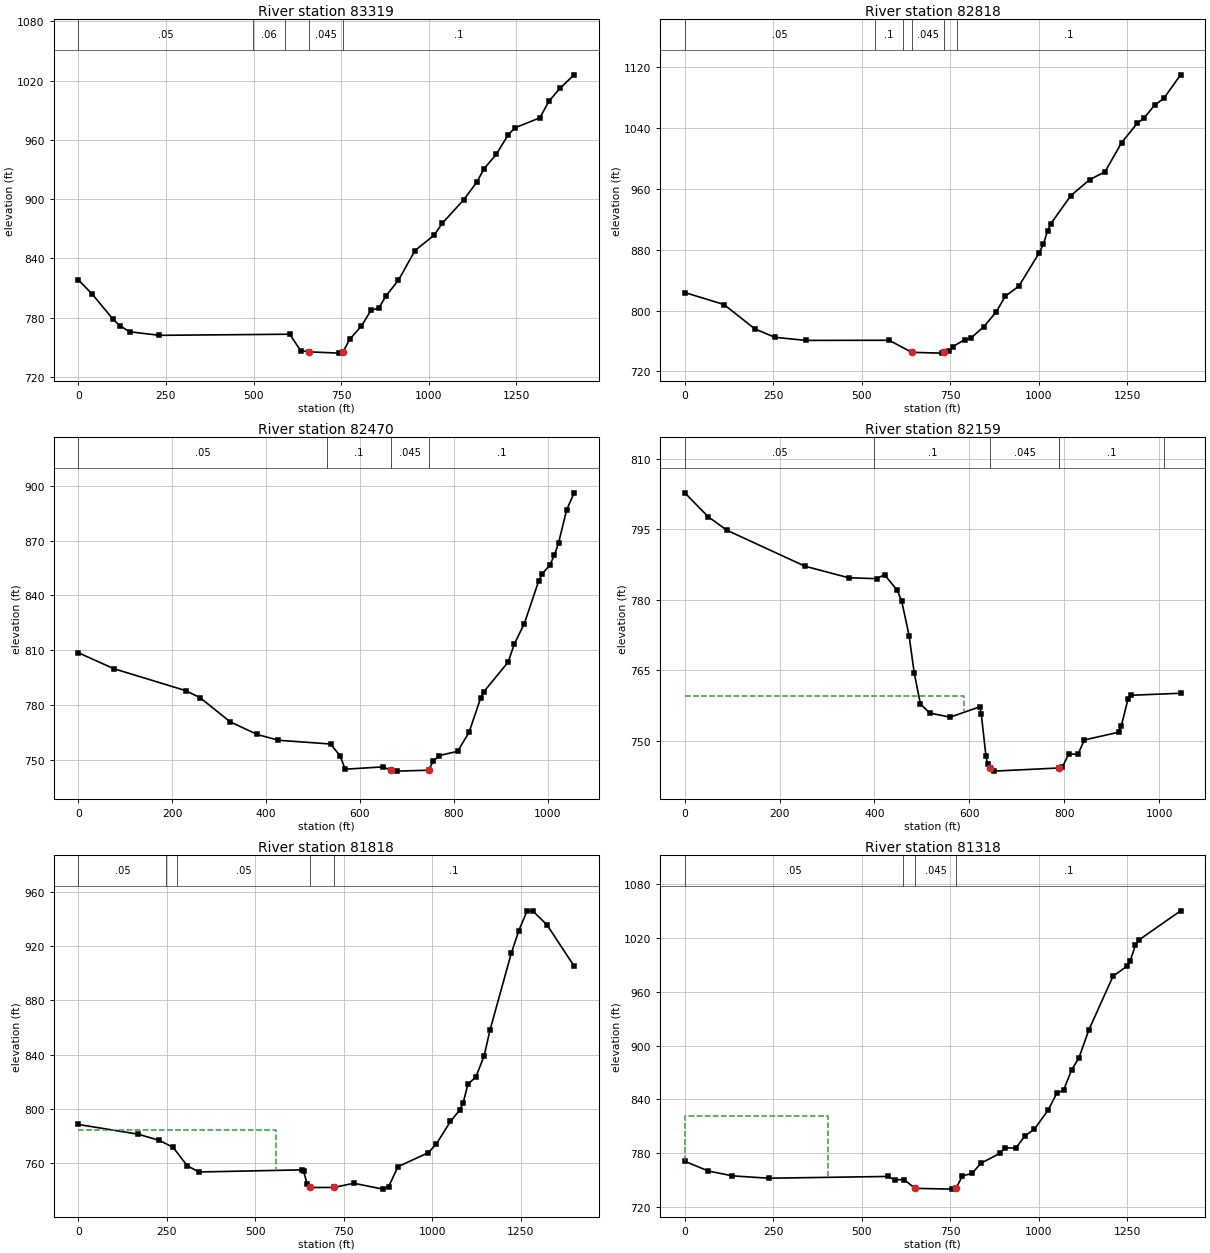
Type RM Length L Ch R = 1 ,83319   ,465.3,500.5,523.6
XS GIS Cut Line= 6
1646415.04988556464587.9546520561646522.06738806464621.179323137
1646614.84673005464658.3882382211646708.39050622464689.669671729
1647045.81601247464794.8909179721647770.85065164464988.313431397
#Sta/Elev= 30
       0  818.14    39.4   803.8    97.8  778.75   118.6  771.59   146.9  765.51
   231.3  761.95   603.1  763.06     634  746.48   657.8745.2024     744  743.91
   755.4745.2159   773.7  757.72   807.7  771.41   834.8  787.23   857.5  789.75
     878  802.09   912.9  817.59   960.4   847.8  1015.2  863.53  1038.5  875.59
  1099.6  899.39  1136.9  917.21  1157.3   930.7  1191.9  945.21  1226.8  965.35
  1245.5  972.19  1316.8  982.37  1342.1  998.93  1374.3 1012.45  1414.5 1025.92
#Mann= 5 ,-1,0
       0     .05       0  497.63     .06       0  589.05     .08       0
   657.8    .045       0   755.4      .1       0
Bank Sta=657.8,755.4
XS Rating Curve= 0 ,0
Exp/Cntr(USF)=0,0
Exp/Cntr=0.3,0.1

Type RM Length L Ch R = 1 ,82818   ,333.6,347.8,361.7
XS GIS Cut Line= 6
1646342.63894114464655.4948713031646654.53201814465030.674895227
1646710.46760181465097.9611779751647048.08142789465504.080772564
1647111.00912355465579.7777996361647238.11385623465732.673163146
#Sta/Elev= 30
       0  823.65   110.6  807.92   197.8  775.86   254.3  764.74   341.5  760.66
   577.3  760.83   641.2744.9257   726.4  743.91   733.4744.9313     747  746.45
   757.2  752.46   790.3  761.58   807.4  763.25   845.2  778.95   879.9  798.23
   905.7  818.87   943.9  832.14  1001.3  876.02  1012.9  887.19  1024.9  904.85
  1034.3  914.38  1090.8  951.36  1144.4  972.43  1187.1  982.59  1234.2 1021.12
  1278.5 1046.56    1298 1053.59  1327.4 1070.37  1353.5  1079.4  1400.8 1110.27
#Mann= 6 ,-1,0
       0     .05       0  537.89      .1       0  615.39     .08       0
   641.2    .045       0   733.4     .07       0  770.39      .1       0
Bank Sta=641.2,733.4
XS Rating Curve= 0 ,0
Exp/Cntr(USF)=0,0
Exp/Cntr=0.3,0.1

Type RM Length L Ch R = 1 ,82470   ,300.8,311.7,326.4
XS GIS Cut Line= 2
1646290.18404714464745.3978187991646635.55387761465744.170031234
#Sta/Elev= 30
       0  808.61    75.8  799.88   228.5  787.91   259.8  783.98   323.4  770.87
   381.3  763.89   426.6  760.72   537.5  758.69   558.1  752.18   568.7  744.89
   648.6  746.15   665.9  744.38   679.8  743.84   746.4  744.35   756.7   749.4
   769.6  752.36   808.3  754.68   832.6  764.99   857.3  783.66   863.8  787.14
   915.9  803.42   929.5  813.54   950.6  824.58   981.1   847.8   988.9  851.84
  1004.4  856.41  1014.7  861.92  1023.5  868.66  1040.8   886.8  1056.8  896.12
#Mann= 4 ,-1,0
       0     .05       0     530      .1       0   665.9    .045       0
   746.4      .1       0
Bank Sta=665.9,746.4
XS Rating Curve= 0 ,0
Exp/Cntr(USF)=0,0
Exp/Cntr=0.3,0.1

Type RM Length L Ch R = 1 ,82159   ,331.9,340.5,360.8
XS GIS Cut Line= 2
1646162.61501066464754.7321385411646243.51244843465797.064509774
#Sta/Elev= 30
       0  802.73    49.3  797.64    88.8  794.78   253.3  787.14   345.5  784.68
   404.7  784.49   421.2  785.34     448     782   457.4   779.7     473  772.36
   483.7  764.48   496.9  757.83   516.6  755.93   559.4  755.06   621.9  757.25
   625.2  755.68   635.1  746.73   638.4  745.08   644.2  744.25   651.5  743.59
   789.1  744.26   796.3  744.49   809.5  747.21   829.2  747.19   842.4  750.21
   914.8  751.86   920.4  753.19   934.5  758.89   941.1  759.71  1045.5  760.14
#Mann= 6 ,-1,0
       0     .05       0     400      .1       0   644.2    .045       0
   789.1     .05       0     790      .1       0    1010     .06       0
#XS Ineff= 2 , 0
           588.3  759.55
Permanent Ineff=
       F       F
Bank Sta=644.2,789.1
XS Rating Curve= 0 ,0
Exp/Cntr(USF)=0,0
Exp/Cntr=0.3,0.1

Type RM Length L Ch R = 1 ,81818   ,478.5,500,522.7
XS GIS Cut Line= 6
1645931.78904106464730.326414555 1645887.0361778465303.973889306
1645867.59199098465553.2168291511645845.95981638465830.499082983
1645830.58681564 466027.556759731645822.83912772466126.864303887
#Sta/Elev= 30
       0  788.61   169.2  781.42   228.5  776.89     268  771.66   307.4  758.24
   340.4  753.56   633.2  755.15   636.5  754.07   646.4   744.7  655.38742.1404
   722.4  742.16     778  745.27   860.3  740.93   876.8  742.84   903.1  757.49
   988.6  767.74  1011.7   774.3  1051.2  790.83  1077.5  799.15  1087.4  804.74
  1100.5  818.14  1123.6  823.84  1146.6  839.36    1163  858.12    1223  914.66
  1244.4  931.49  1267.8   946.1  1284.8   945.8  1324.3  935.66  1400.8   905.3
#Mann= 5 ,-1,0
       0     .05       0  248.83      .1       0  278.83     .05       0
  655.38    .045       0   722.4      .1       0
#XS Ineff= 2 , 0
          558.06  784.71
Permanent Ineff=
       F       F
Bank Sta=655.38,722.4
XS Rating Curve= 0 ,0
Exp/Cntr(USF)=0,0
Exp/Cntr=0.3,0.1

Type RM Length L Ch R = 1 ,81318   ,493.2,500,509.3
XS GIS Cut Line= 6
1645741.60799097464700.0676168051645692.89877081464786.952613637
1645596.25132631464959.353187472 1645548.8872478465043.839567065
1645250.09519447465578.5166473091645057.34197105465922.347652555
#Sta/Elev= 30
       0  770.72    66.4  759.85   134.7  754.42   236.6  751.81     574  753.78
   592.7  750.06   619.3  750.27   650.5 740.505     754  739.62     766 740.505
   784.5  754.36   812.1  757.35   836.2  768.44   889.7   779.5   904.7  785.99
   934.8  785.27   961.1  799.05   987.4  806.47  1026.7  828.02  1050.8  846.61
    1070  850.04  1092.7  872.64  1113.5  886.18  1141.6  917.54  1209.9  977.47
  1250.7  988.98  1258.2  994.47  1273.3 1012.07  1284.5 1018.32  1400.8 1050.42
#Mann= 4 ,-1,0
       0     .05       0  615.36      .1       0   650.5    .045       0
     766      .1       0
#XS Ineff= 2 , 0
           405.2  820.81
Permanent Ineff=
       F       F
Bank Sta=650.5,766
XS Rating Curve= 0 ,0
Exp/Cntr(USF)=0,0
Exp/Cntr=0.3,0.1

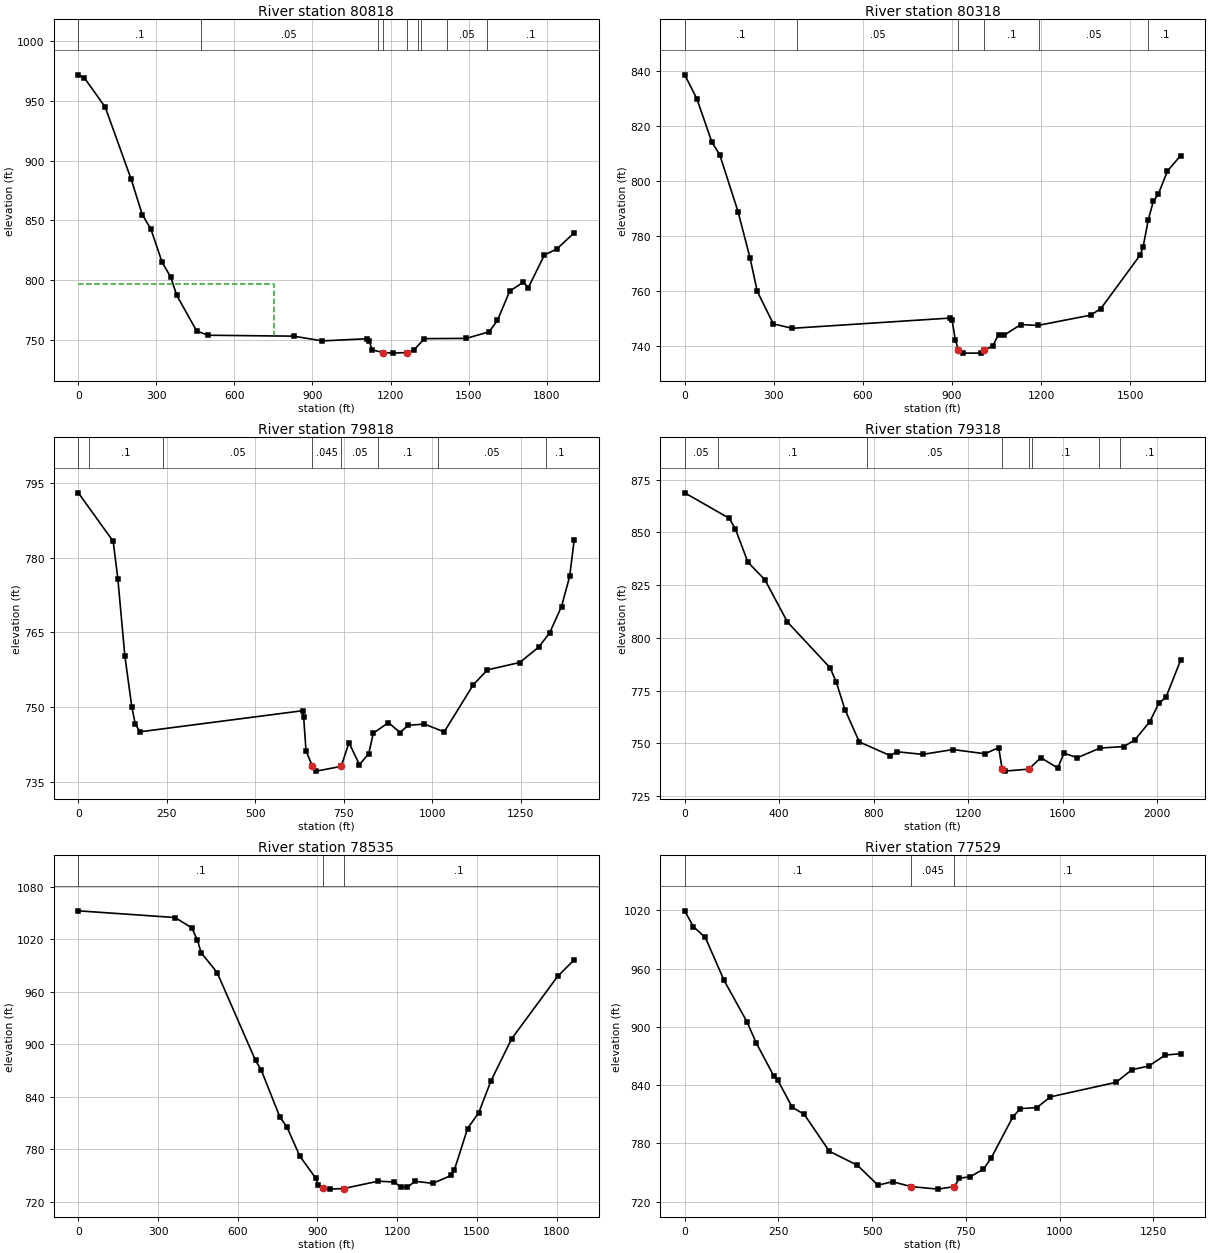
Type RM Length L Ch R = 1 ,80818   ,515.7,500,482.2
XS GIS Cut Line= 6
1645272.35795332 463940.649034091645361.01459205464539.035786644
1645125.22733398464847.5269675551645026.54741322464976.633664727
1644867.14222021465185.1913184821644570.86590989465572.822104886
#Sta/Elev= 30
       0  971.67    23.6  968.97   103.2  944.72   202.7   884.6   245.8  854.78
     279  842.57   322.1  814.88   355.3  802.48   378.5  787.16   454.8   757.5
   497.9  753.91   827.2  753.13   938.3  749.16  1108.1  750.97  1117.5  749.24
  1129.2  741.681170.709739.4537  1210.8  738.941261.809739.4521  1289.3  741.49
  1330.4  751.05  1491.6  751.28  1578.8  756.77  1611.2  766.37  1658.1   790.8
  1709.6  798.12    1730  793.81  1791.5  821.04  1838.5  825.93  1906.1  839.54
#Mann= 9 ,-1,0
       0      .1       0     470     .05       0  1150.7      .1       0
1170.709    .045       01261.809      .1       0  1305.7     .05       0
  1315.7      .1       0  1418.2     .05       0 1571.95      .1       0
#XS Ineff= 2 , 0
          750.71   796.7
Permanent Ineff=
       F       F
Bank Sta=1170.709,1261.809
XS Rating Curve= 0 ,0
Exp/Cntr(USF)=0,0
Exp/Cntr=0.3,0.1

Type RM Length L Ch R = 1 ,80318   ,511.4,500,488.7
XS GIS Cut Line= 6
1644807.54507683463859.8925469031644709.66746956 464215.65684022
1644607.99411647464590.4005133061644585.01942489464674.832431063
1644565.21992381464747.1728375551644363.54578647465469.954528481
#Sta/Elev= 30
       0  838.69    40.8  829.99      91  814.32   118.2  809.53   179.6   788.9
   220.3  771.95   244.1  759.98   298.5   748.1   362.3  746.51     893  750.23
   900.4  749.42   911.7  742.11921.7708738.6436   937.8  737.48   999.1   737.5
1007.571738.6554  1036.6  739.93    1057  744.25    1074   743.9  1131.9  747.87
  1189.8  747.56  1367.1  751.29  1401.8   753.7  1533.9  773.15  1544.1  776.24
  1561.1  785.88  1578.2  792.73  1595.2  795.32  1625.8  803.71  1670.2  809.31
#Mann= 6 ,-1,0
       0      .1       0  378.98     .05       0921.7708    .045       0
1007.571      .1       0 1192.28     .05       0 1561.34      .1       0
Bank Sta=921.7708,1007.571
XS Rating Curve= 0 ,0
Exp/Cntr(USF)=0,0
Exp/Cntr=0.3,0.1

Type RM Length L Ch R = 1 ,79818   ,516.2,500,481.8
XS GIS Cut Line= 2
1644060.08084223464016.4302045551644060.08084223465417.211523727
#Sta/Elev= 30
       0  792.95    98.5  783.23   111.6  775.76   131.3  760.38     151  750.12
   160.8  746.71     174  745.12   633.3  749.34   636.6  748.01   643.1  741.36
   661.2  738.22   672.6  737.25   742.7  738.21   764.5  742.94     794  738.55
   820.3  740.75   833.4  744.86   876.1  746.96   908.9  744.97   931.8  746.43
   977.8  746.66  1033.5   745.1  1115.6  754.53  1155.8  757.52  1246.8  758.99
  1300.2  762.05  1331.2   764.9  1364.9  770.19  1387.9  776.21  1400.8  783.56
#Mann= 8 ,-1,0
       0     .05       0      30      .1       0  238.83     .05       0
   661.2    .045       0   742.7     .05       0  845.39      .1       0
 1016.64     .05       0 1321.17      .1       0
Bank Sta=661.2,742.7
XS Rating Curve= 0 ,0
Exp/Cntr(USF)=0,0
Exp/Cntr=0.3,0.1

Type RM Length L Ch R = 1 ,79318   ,781.9,783.2,781.6
XS GIS Cut Line= 6
1643312.02026622463398.6322635971643350.55501814464051.334181388
1643406.32690039464288.2105008961643434.88622648464382.478685066
1643728.04508898465238.3509890591643778.54400373465431.611429304
#Sta/Elev= 30
       0  868.74   188.4  856.67   214.7  851.58   267.3   835.9   339.6  827.51
   434.9  807.53   615.7  785.81     642  778.96   678.7  765.96   739.4  750.67
   870.9  744.16   897.8  746.03  1007.7  744.78    1136  747.06  1271.2  745.08
  1329.7  747.951344.239737.7884  1354.4  736.841457.039737.7828    1508  743.19
  1579.8  738.37  1606.2  745.34    1663  743.19  1758.6  747.77  1859.3  748.48
  1905.8  751.55  1969.8  760.32  2007.9  768.98  2038.3  771.88  2100.2  789.38
#Mann= 8 ,-1,0
       0     .05       0     140      .1       0  773.84     .05       0
1344.239    .045       01457.039     .05       0 1468.82      .1       0
 1755.07     .05       0 1841.94      .1       0
Bank Sta=1344.239,1457.039
XS Rating Curve= 0 ,0
Exp/Cntr(USF)=0,0
Exp/Cntr=0.3,0.1

Type RM Length L Ch R = 1 ,78535   ,998.3,1006,1006.8
XS GIS Cut Line= 3
 1642352.7996483464146.1266495341642582.01579832464370.906208456
 1643152.6128219465806.943628401
#Sta/Elev= 30
       0 1052.64   363.7 1044.99   426.9 1033.26   448.1 1019.25   462.2  1004.8
   522.2  982.17   666.9  881.65   688.1  870.91   758.7   816.9   784.9  805.76
   833.3  772.59   892.9  747.46   903.5  738.88   921.1  735.41   945.8  734.69
   998.8   735.4  1128.9  743.79  1189.6  742.81  1214.1  736.83  1237.6  736.63
  1267.1  743.65  1334.2  741.29  1403.2  750.32  1415.4  756.83  1464.9  803.91
  1507.1  822.07    1553  858.42  1630.7  906.38  1803.7   977.7  1866.3  996.69
#Mann= 3 ,-1,0
       0      .1       0   921.1    .045       0   998.8      .1       0
Bank Sta=921.1,998.8
XS Rating Curve= 0 ,0
Exp/Cntr(USF)=0,0
Exp/Cntr=0.3,0.1

Type RM Length L Ch R = 1 ,77529   ,907.1,881.8,848.6
XS GIS Cut Line= 2
1641745.03173342464927.2931408471642265.22219625466143.823217935
#Sta/Elev= 30
       0 1019.48    22.8 1003.23    54.9  992.09   104.9  947.84   166.2  905.04
   190.7  883.47   238.2   848.9   248.2  845.05   286.8  817.14     319  809.75
   385.7  771.84   460.6  757.39   515.6  736.88   554.5   740.4   604.4  735.36
   675.6  732.78  719.57735.3556   733.1   744.2   760.6  745.33   797.1  753.39
   818.1  765.14   875.5  807.19   895.5  815.72   939.8  816.79   975.5  827.81
  1150.8   842.8  1193.2  855.79    1238  859.59  1282.4  870.94  1323.1  872.23
#Mann= 3 ,-1,0
       0      .1       0   604.4    .045       0  719.57      .1       0
Bank Sta=604.4,719.57
XS Rating Curve= 0 ,0
Exp/Cntr(USF)=0,0
Exp/Cntr=0.3,0.1

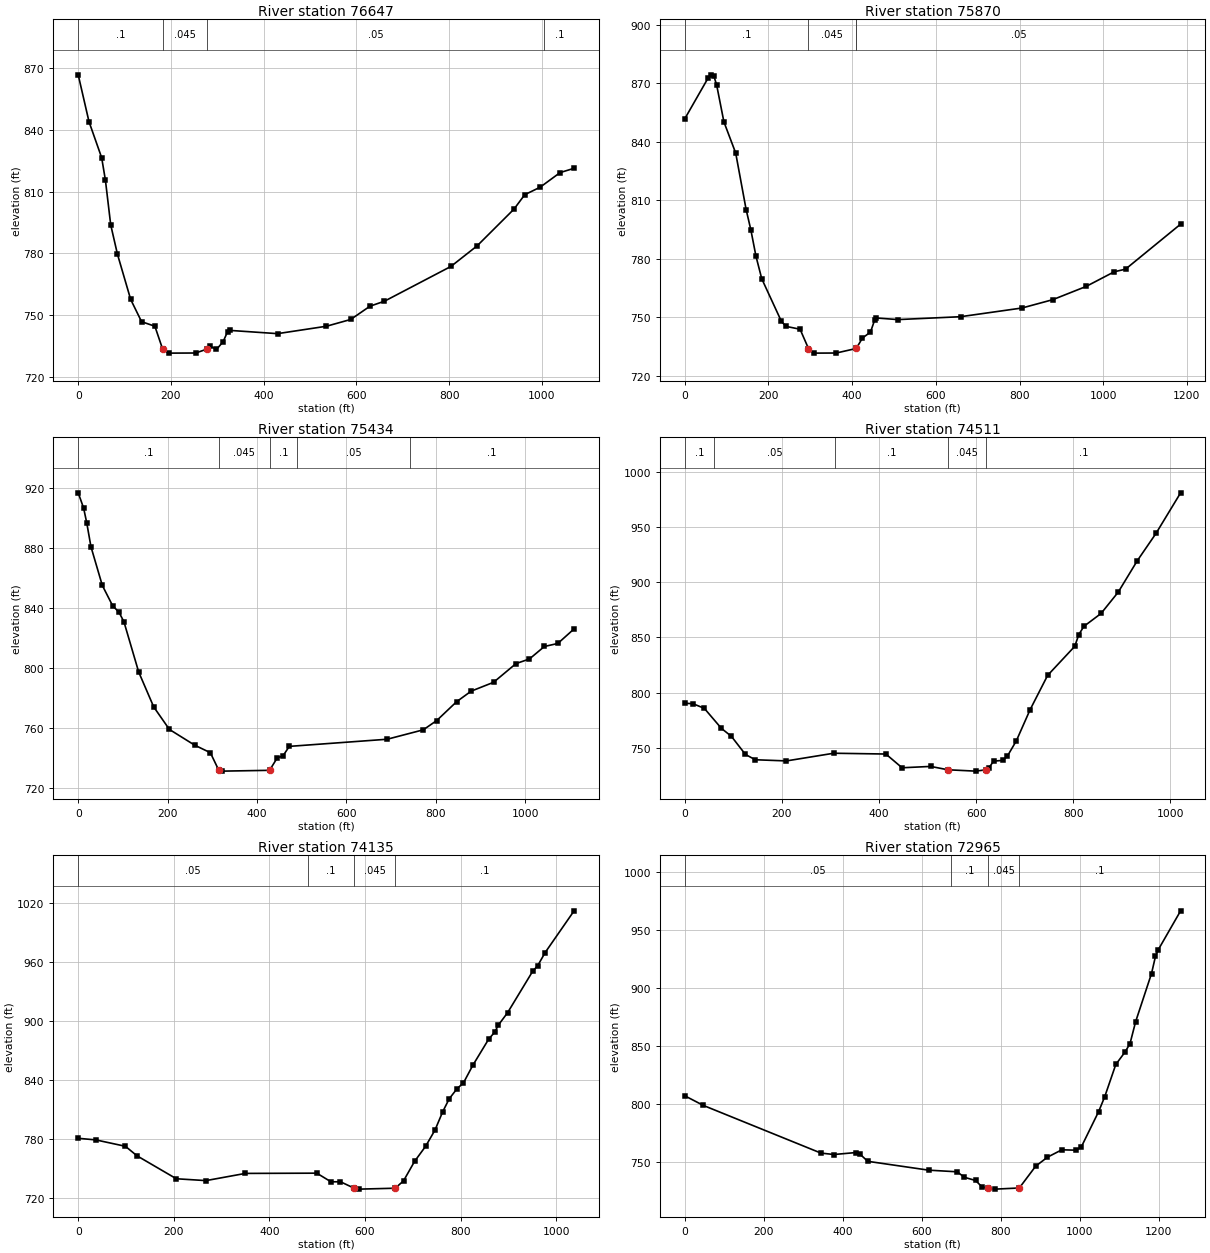
Type RM Length L Ch R = 1 ,76647   ,828.5,777.5,695.8
XS GIS Cut Line= 3
1641118.29711108465857.9207814681641769.02408936 466279.48571264
1642060.07558211 466238.73048672
#Sta/Elev= 30
       0   866.7    23.2  843.99    50.6  826.44    58.7  815.46    70.1  793.83
    84.6   779.6   113.1  757.64   136.6  746.83   165.3  744.62  182.18733.4012
   195.2  731.56   253.1  731.62   276.8  733.44   285.1   734.9   298.1  733.33
   312.4  737.09   321.9  741.89   328.1  742.58   429.8  741.02   535.3  744.62
   587.6  747.91   629.1  754.35   660.4  756.78   803.8  773.68   860.2  783.67
   939.7  801.51   962.8  808.49     996  812.13    1039  819.22  1069.2  821.32
#Mann= 4 ,-1,0
       0      .1       0  182.18    .045       0   276.8     .05       0
 1005.35      .1       0
Bank Sta=182.18,276.8
XS Rating Curve= 0 ,0
Exp/Cntr(USF)=0,0
Exp/Cntr=0.3,0.1

Type RM Length L Ch R = 1 ,75870   ,438.1,435.5,430.4
XS GIS Cut Line= 3
1640949.60822148466911.7234249651641436.77071841466534.654147678
1641995.49380812466427.313258523
#Sta/Elev= 30
       0  851.66    55.4  872.46    63.7  874.25    69.8  873.48    76.2   869.1
    93.6  850.12   121.8  834.11   146.7  805.14     158  794.71   170.3  781.14
     184  769.66   231.1  747.74   242.1  745.22   275.6  743.76   295.7 733.854
     308   731.5   362.1  731.56   409.9  733.89   424.7  739.25   443.9   742.3
   453.7  748.39     458  749.53   509.4   748.7     659  750.18     806  754.65
   879.5  758.92   959.1   765.7  1026.5  773.24  1053.3  774.56    1185  797.66
#Mann= 4 ,-1,0
       0      .1       0   295.7    .045       0   409.9      .1       0
     410     .05       0
Bank Sta=295.7,409.9
XS Rating Curve= 0 ,0
Exp/Cntr(USF)=0,0
Exp/Cntr=0.3,0.1

Type RM Length L Ch R = 1 ,75434   ,915.2,923.6,917.6
XS GIS Cut Line= 3
1641231.32693071467273.3788089141641771.16147677466793.920494979
1642151.17658485466719.338090589
#Sta/Elev= 30
       0  916.79    12.1  906.64      19  896.94    28.5  880.92    53.9  855.14
    77.1  841.57    91.1  837.35   102.3  830.93   135.2  797.57   168.9  774.25
     204  759.26   260.4  748.81   295.6  743.77   314.5 732.052   322.5   731.5
     428732.0333   445.3  740.33     458  741.62   472.2  747.98   691.1  752.73
     772  759.01   802.1   765.2   846.4   777.7     879  784.74   929.1  790.63
   979.3  803.09  1009.4  806.17  1042.8  814.48  1072.9   816.5  1109.3  826.21
#Mann= 5 ,-1,0
       0      .1       0   314.5    .045       0     428      .1       0
     490     .05       0  742.01      .1       0
Bank Sta=314.5,428
XS Rating Curve= 0 ,0
Exp/Cntr(USF)=0,0
Exp/Cntr=0.3,0.1

Type RM Length L Ch R = 1 ,74511   ,351.9,375.7,393.9
XS GIS Cut Line= 2
1641740.84820728  467936.62878611642575.49753648467348.580395074
#Sta/Elev= 30
       0  790.34    16.8  789.91    40.2  785.76    75.5  767.54    96.1   760.3
   124.9  743.92   145.2  739.08   209.4  738.02   306.8  744.99   414.1  744.27
   447.5  731.81   506.4  733.03   541.7  729.99   598.7  728.76   620.1  729.93
   625.8  731.33   635.8  737.83   654.9   738.5   664.1  742.22   682.8   756.3
   711.1  784.51   747.2  815.63     803  841.96   811.4  852.65   821.8  860.07
   857.2  871.78   892.5  891.11   931.8  919.63   970.2  944.32    1021   981.2
#Mann= 5 ,-1,0
       0      .1       0      60     .05       0     310      .1       0
   541.7    .045       0   620.1      .1       0
Bank Sta=541.7,620.1
XS Rating Curve= 0 ,0
Exp/Cntr(USF)=0,0
Exp/Cntr=0.3,0.1

Type RM Length L Ch R = 1 ,74135   ,1099.6,1169.8,1227
XS GIS Cut Line= 3
1641752.04269169468097.3449780851642191.80703271467960.877704284
 1642765.5935353467902.001931628
#Sta/Elev= 30
       0  780.31      37  778.66    98.8  772.16   122.9  762.53   205.3  739.16
   267.2  737.28   349.6   744.6   499.1  744.85   528.8  736.06   548.6   736.1
   577.3729.5616   588.2  728.62   663.1729.5493   680.5  737.02   703.6  756.83
   726.8  772.23   746.5  788.86   762.5  807.36   776.2  820.58   792.4  830.67
   805.9  836.67   825.3   854.4   858.6  881.09   871.8  888.57   878.4  895.11
   898.2  908.02   950.8  950.23   960.9  955.57   976.7  969.13  1037.3 1011.58
#Mann= 4 ,-1,0
       0     .05       0  480.45      .1       0   577.3    .045       0
   663.1      .1       0
Bank Sta=577.3,663.1
XS Rating Curve= 0 ,0
Exp/Cntr(USF)=0,0
Exp/Cntr=0.3,0.1

Type RM Length L Ch R = 1 ,72965   ,893.6,931,958
XS GIS Cut Line= 4
1641458.62568695468004.9966805471641707.23370158468409.872590092
1641774.71301984468935.5009638871641724.99141691469180.557435454
#Sta/Elev= 30
       0  807.35    47.3  799.03   344.7  758.08   377.5  756.85   432.3  758.51
   443.9  757.08   463.1  751.01   617.2   743.4   689.7  741.98   707.6  737.27
   736.1  734.52   752.6  728.93   768.3728.0567   785.7  727.09   846.8728.0725
   888.2   746.8     918  754.54   954.4   760.9   990.7  760.56    1004  763.55
  1047.5  793.68    1063  806.53    1091  834.25  1114.4  844.96    1127  852.21
  1141.2  871.02  1181.4  912.44  1191.4  927.12  1198.1  932.67  1255.1  966.36
#Mann= 4 ,-1,0
       0     .05       0  675.11      .1       0   768.3    .045       0
   846.8      .1       0
Bank Sta=768.3,846.8
XS Rating Curve= 0 ,0
Exp/Cntr(USF)=0,0
Exp/Cntr=0.3,0.1