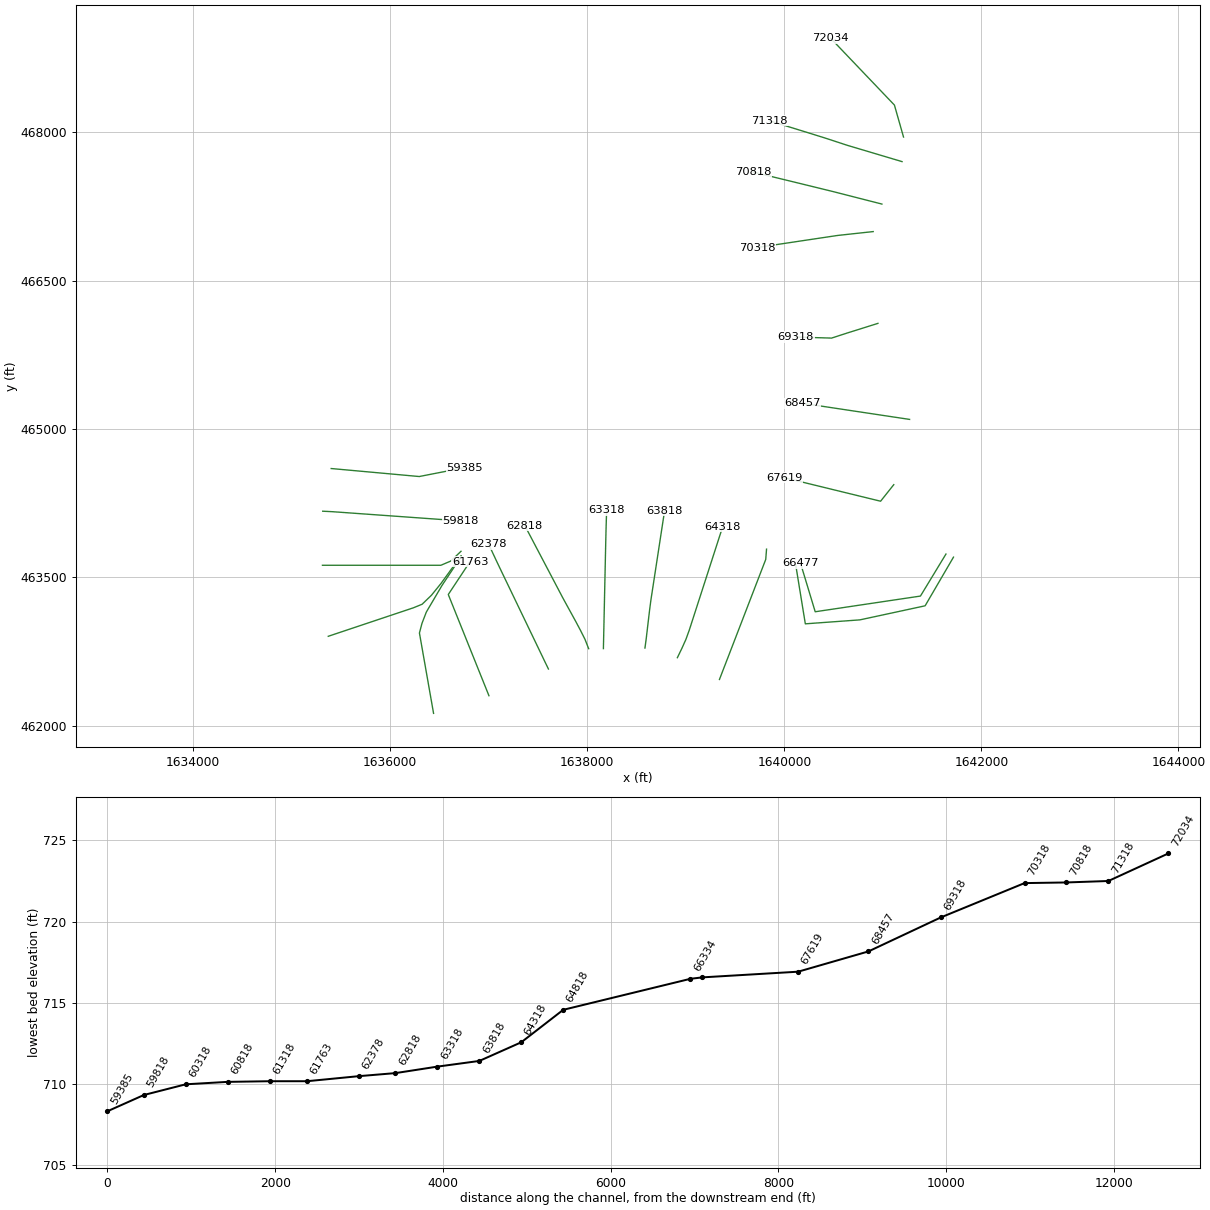
HEC-RAS study FshCrk.prj: FshCrk

--- FshCrk.g01 (geometry) --- (continued)

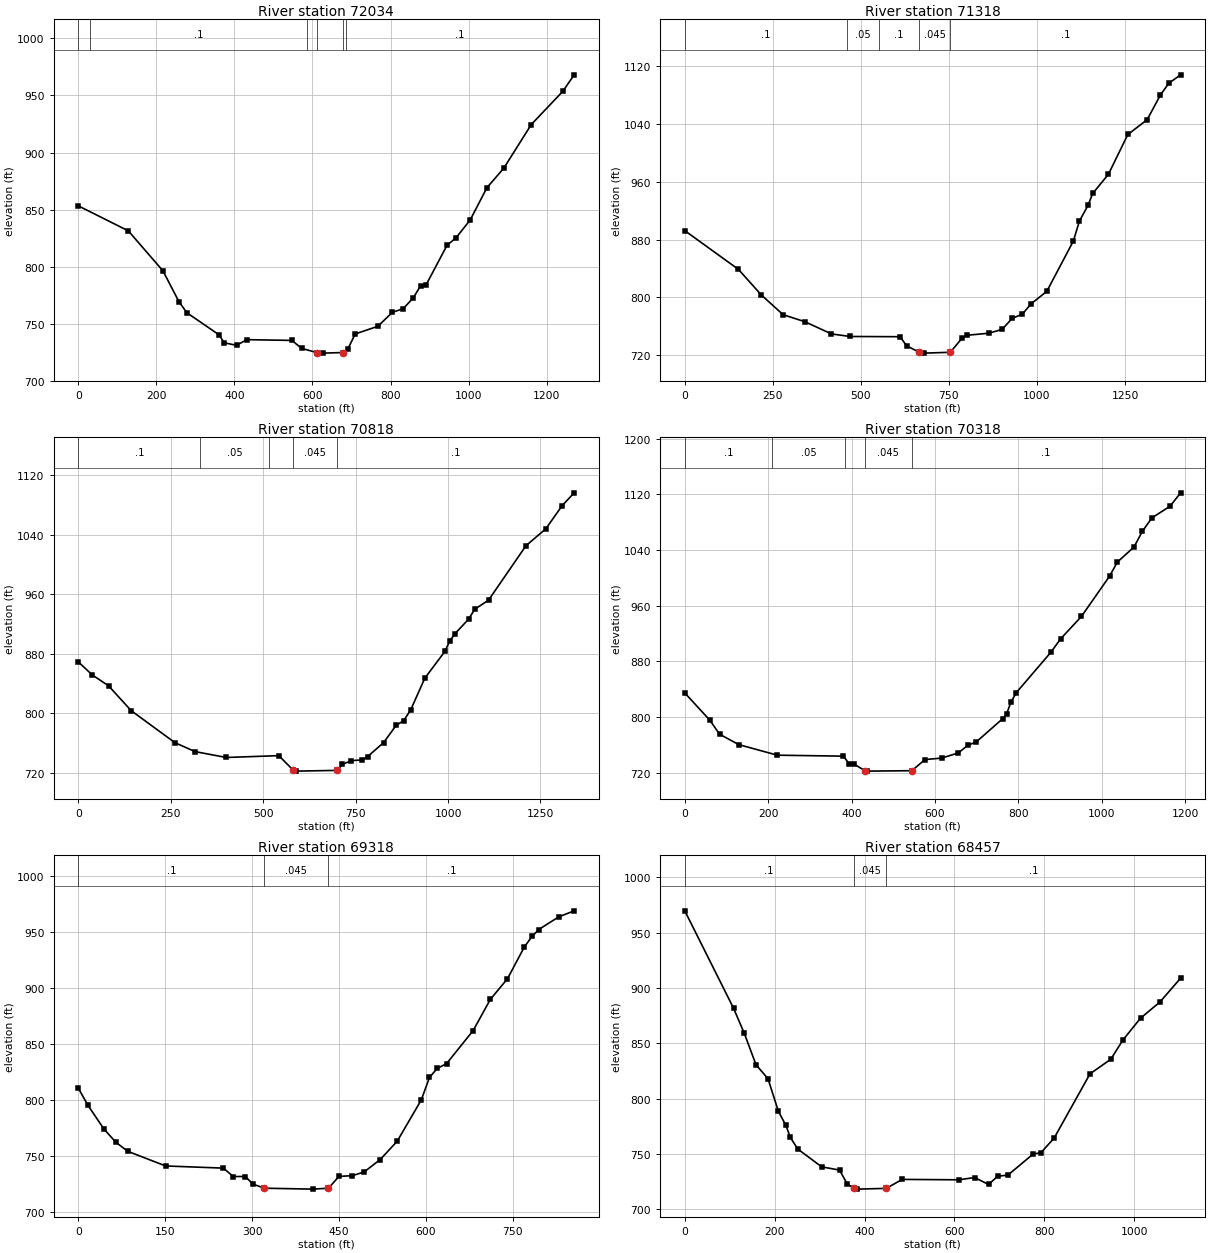
Type RM Length L Ch R = 1 ,72034   ,695.6,715.9,734.6
XS GIS Cut Line= 3
1641210.01767231467951.7235345551641117.67755259468274.913953577
1640471.29671455468949.707136152
#Sta/Elev= 30
       0  853.26   128.1  831.35   216.8  796.33   257.7  769.37   278.2  759.58
   361.4  740.05   373.4  733.29   405.5  731.04   431.6     736     547  735.35
   572.6   728.3   610.9724.7422   628.2   724.2   679.3  724.74   691.2  728.18
   709.5     741   767.5  747.72     805     760   832.4  763.09   858.7   772.8
   876.9  783.16   890.5  783.59     945   818.8   967.7  825.17  1004.2  840.91
  1046.9  869.08  1090.4  886.32  1160.7  924.52  1241.4  953.57  1270.6  968.08
#Mann= 6 ,-1,0
       0     .05       0      30      .1       0  586.12     .08       0
   610.9    .045       0   679.3     .08       0  686.12      .1       0
Bank Sta=610.9,679.3
XS Rating Curve= 0 ,0
Exp/Cntr(USF)=0,0
Exp/Cntr=0.3,0.1

Type RM Length L Ch R = 1 ,71318   ,495.9,500,504.5
XS GIS Cut Line= 6
 1641195.3014943467703.1606216711640636.99844955467868.734835893
1640470.69399214467923.2134014821640399.27549981 467946.11788322
1640226.17906122467999.9376574751639849.34615347468115.684145138
#Sta/Elev= 30
       0  892.32   152.4  838.57   217.4  803.08   279.3  775.75   340.6  766.13
   416.5  749.11   469.3  745.57   611.2  745.26   629.6  732.77   665.6723.6771
   680.2   722.5   753.8723.6694   787.2   743.2     801  747.26   862.9  750.08
     901  755.38   929.6  770.77   958.5  776.56   983.2  790.83  1027.8  808.18
  1103.3  877.99  1120.5  905.69  1144.8   927.3  1158.2  943.92  1202.9  970.58
  1257.9 1025.66  1312.7 1046.13  1350.4 1080.37  1374.4 1096.81  1407.8 1108.38
#Mann= 5 ,-1,0
       0      .1       0     460     .05       0     550      .1       0
   665.6    .045       0   753.8      .1       0
Bank Sta=665.6,753.8
XS Rating Curve= 0 ,0
Exp/Cntr(USF)=0,0
Exp/Cntr=0.3,0.1

Type RM Length L Ch R = 1 ,70818   ,476.2,500,522
XS GIS Cut Line= 6
1640990.78709223467273.9117446541640490.99217989467401.206571475
1640320.97578764467442.6720397321640248.11143206467460.442673475
1640163.10307188 467481.175571651639688.91209114467596.130066141
#Sta/Elev= 30
       0   869.2    37.9  851.65    81.9  837.03   142.8  803.76   261.3  760.66
   315.5  748.68     400  740.76   542.3  743.21   581.8723.4224   589.5  722.41
   700.1723.4118   714.4  731.52   738.1  736.46   768.5  737.58   782.3  741.84
   825.9  760.84   859.7  783.97     880  790.21   899.1  804.79   937.3   847.4
   991.4  883.21  1004.5  897.15  1018.6  907.04  1055.5  926.61  1072.4  940.09
  1109.5  952.15  1210.8 1025.34  1264.8 1048.25  1308.7 1079.25  1341.2 1096.48
#Mann= 5 ,-1,0
       0      .1       0     330     .05       0  515.75      .1       0
   581.8    .045       0   700.1      .1       0
Bank Sta=581.8,700.1
XS Rating Curve= 0 ,0
Exp/Cntr(USF)=0,0
Exp/Cntr=0.3,0.1

Type RM Length L Ch R = 1 ,70318   ,991.1,1000,1009.3
XS GIS Cut Line= 6
1640902.39276499466995.7182766891640540.99043947466956.585741565
1640466.81211014466945.5139133041640293.72945106466919.680303559
1640114.46537389466892.9237953871639724.64266272466834.740512803
#Sta/Elev= 30
       0  834.67    60.2  795.42    83.3  775.44   129.5  760.44   221.9  745.27
   380.4  743.88   393.7  733.19   406.9  732.11   431.8722.9814   437.4  722.37
   544.3722.9887   576.1  738.99   615.9   741.1   655.7  748.51   678.9  759.51
     699  764.37   761.9  797.52   771.8  804.69   781.8  821.32     795  835.22
     878  893.25   901.2  912.45     951  944.53  1018.4 1002.36  1037.2 1022.66
    1077 1044.24  1097.3    1067  1120.1 1086.23  1163.3 1102.81  1188.9 1122.17
#Mann= 5 ,-1,0
       0      .1       0     210     .05       0  383.51      .1       0
   431.8    .045       0   544.3      .1       0
Bank Sta=431.8,544.3
XS Rating Curve= 0 ,0
Exp/Cntr(USF)=0,0
Exp/Cntr=0.3,0.1

Type RM Length L Ch R = 1 ,69318   ,873.8,860.8,842.6
XS GIS Cut Line= 6
1640950.28011228466067.6836866081640717.87066314465994.783531308
1640646.20906106465972.6339693071640551.06489439465941.851878643
 1640479.7064413465918.7653106451640117.03804183465929.412514277
#Sta/Elev= 30
       0  810.35    16.7  794.98    44.2  773.91    64.8  762.09    85.4  753.99
   150.8  740.93   250.5     739   267.6   731.5   288.2  731.49     302  724.64
   321.4721.0733   405.3  720.25     432721.0753   450.2   731.6   473.3  732.27
   493.6  735.55   521.4  746.66   550.7  762.96   592.4  799.93   606.5  819.97
   619.8  827.94   636.1  832.31     682  861.84   711.6  889.61   741.2  908.03
   770.6  936.63   783.8  945.89   795.2  951.95   829.7  963.25   856.4  968.66
#Mann= 3 ,-1,0
       0      .1       0   321.4    .045       0     432      .1       0
Bank Sta=321.4,432
XS Rating Curve= 0 ,0
Exp/Cntr(USF)=0,0
Exp/Cntr=0.3,0.1

Type RM Length L Ch R = 1 ,68457   ,841.6,838.3,834.2
XS GIS Cut Line= 6
1641271.67233504465096.5414838651640662.85826395465187.863151611
1640474.34256488465216.1409821971640376.99400629465230.742987112
1640278.87313954465245.4617896991640180.36579062465260.237678782
#Sta/Elev= 30
       0  969.78   108.5   881.7   132.1  859.33   158.6  830.52   185.1  818.04
   208.4  788.39   224.9  775.87   234.9  764.88   251.5  754.39   304.6  738.31
   344.4  735.38     361  723.23   375.8718.8486   384.2  718.16   448.6718.8497
   483.7  726.95   609.8  726.59   645.1  728.65   676.1  722.35     696  729.76
   719.3  730.92   775.7  750.03   792.2  750.93   822.1  764.37   901.7  822.34
   948.2  835.61   974.7  852.79  1014.3  872.73  1057.6  887.39  1103.5  908.91
#Mann= 3 ,-1,0
       0      .1       0   375.8    .045       0   448.6      .1       0
Bank Sta=375.8,448.6
XS Rating Curve= 0 ,0
Exp/Cntr(USF)=0,0
Exp/Cntr=0.3,0.1

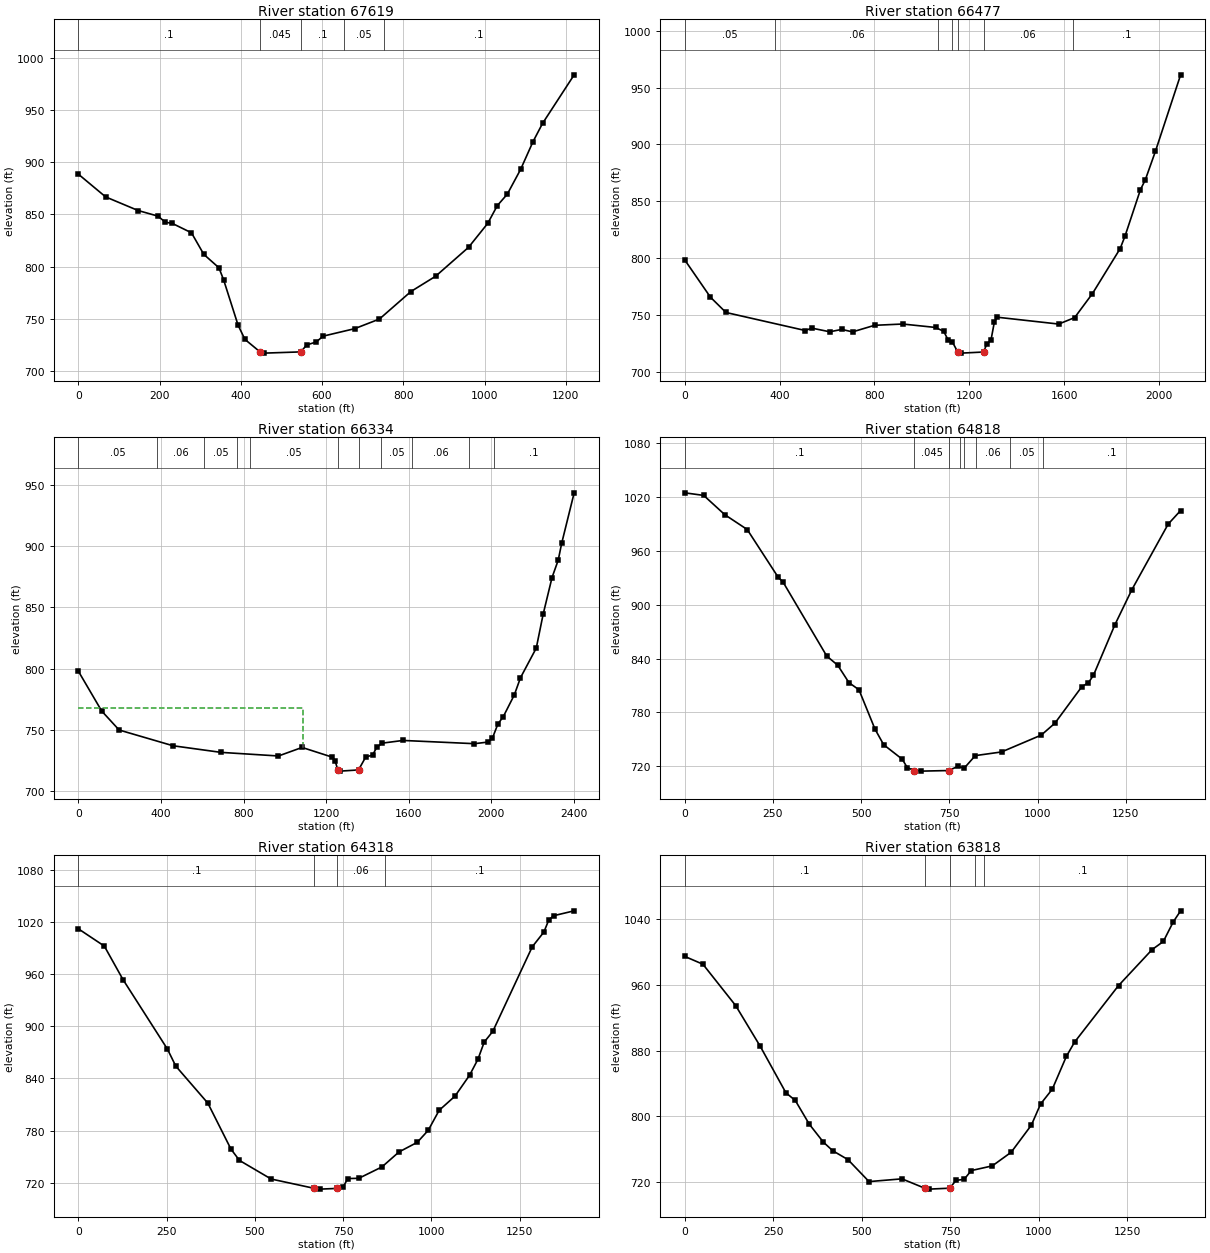
Type RM Length L Ch R = 1 ,67619   ,1119.9,1142.4,1160.1
XS GIS Cut Line= 6
1641110.98336072464436.5672080631640977.37393485464269.348013821
1640886.28028501464291.5064340711640382.22748735464414.113472316
1640192.44899551464460.2774219841639999.25417194464507.269782069
#Sta/Elev= 30
       0  888.75    67.3  866.88   147.1  853.83   195.8  848.46   214.4  842.59
   231.3  841.45   278.5  832.45   308.9  811.73   346.1  798.87   357.6  787.37
   393.3  743.74   410.2  730.08   447.4  718.09   457.5  716.91   547.7   718.1
   562.2  724.75   585.8  727.63   602.5   733.2   680.3  740.39   741.3  749.64
   818.8  776.05   879.6  790.72   960.6  818.46  1007.9  841.47  1031.6  858.59
  1056.1  869.52  1088.9  893.31  1119.3  919.86  1142.8   937.4  1220.7  984.09
#Mann= 5 ,-1,0
       0      .1       0   447.4    .045       0   547.7      .1       0
  655.29     .05       0  752.79      .1       0
Bank Sta=447.4,547.7
XS Rating Curve= 0 ,0
Exp/Cntr(USF)=0,0
Exp/Cntr=0.3,0.1

Type RM Length L Ch R = 1 ,66477   ,147.1,143.1,140
XS GIS Cut Line= 4
1641640.70915465463735.0146122041641381.85192916463310.270009823
1640313.61013949463151.6743857581640164.12920646463643.867701822
#Sta/Elev= 30
       0  798.42   108.3   765.7   173.7  752.28   508.7  736.41   535.2  738.57
   611.5  735.32   662.4   737.4   707.7  735.23   800.5  741.01   919.4  742.14
    1058  739.12  1092.4  735.68    1110  728.48  1128.9  726.39  1151.4717.5256
  1165.4  716.56  1260.4717.5276  1274.8  724.96  1291.4  727.66  1306.2  744.11
  1317.9  748.13  1577.4  742.11  1644.6  747.77    1720  768.96  1836.6  808.41
  1857.2  819.43  1922.3  860.25  1942.9  868.93  1985.2  893.79  2091.8  961.18
#Mann= 7 ,-1,0
       0     .05       0     380     .06       0 1067.41     .07       0
 1127.41     .08       0  1151.4    .045       0  1260.4     .06       0
 1637.36      .1       0
Bank Sta=1151.4,1260.4
XS Rating Curve= 0 ,0
Exp/Cntr(USF)=0,0
Exp/Cntr=0.3,0.1

Type RM Length L Ch R = 1 ,66334   ,1616.9,1515.5,1416.4
XS GIS Cut Line= 5
1641717.27255937463704.0246626741641429.24832256 463211.83134661
1640767.52175319463069.6421664141640213.34853807463029.537525846
1640116.73281306463620.169505123
#Sta/Elev= 30
       0  797.94   113.1  765.45   197.5  749.98   458.9  737.13   690.5  731.76
   969.1  728.81  1083.6  735.77  1230.8   727.8  1244.2  724.53  1256.5717.4182
  1267.3  716.47  1356.9717.4312  1391.6  727.92  1425.2  729.57  1444.9  735.82
  1471.2  739.26  1572.4  741.47  1918.5  738.83    1985  740.17    2005  743.19
  2031.7  754.79  2058.2  760.93  2111.5  778.61  2141.3  792.58  2217.7  816.72
    2251   844.3    2294   874.2  2324.1  888.44  2340.7  902.07  2401.2  943.23
#Mann= 11 ,-1,0
       0     .05       0     380     .06       0  610.27     .05       0
  770.27     .06       0  830.27     .05       0  1256.5    .045       0
  1356.9     .08       0  1467.1     .05       0  1617.1     .06       0
 1892.73     .05       0 2012.73      .1       0
#XS Ineff= 2 , 0
          1089.6  767.58
Permanent Ineff=
       F       F
Bank Sta=1256.5,1356.9
XS Rating Curve= 0 ,0
Exp/Cntr(USF)=0,0
Exp/Cntr=0.3,0.1

Type RM Length L Ch R = 1 ,64818   ,498.9,500,497.6
XS GIS Cut Line= 6
1639341.61947864462467.207909316 1639449.1573213462744.323496804
1639612.60056397463166.9446988111639739.97268455 463496.29804273
1639811.48468064463680.5791702271639819.63131788463784.653109059
#Sta/Elev= 30
       0  1024.6    53.6 1021.72   113.4 1000.24   176.9  983.74   264.8  930.51
   278.2   925.4   402.4  842.77   433.6   832.5   465.3  813.16   493.8  805.16
   539.1  761.41   563.8  743.97   616.5  727.82   630.7  718.46   651.1715.2138
   669.3  714.56   747.9715.2105   773.7  719.74   792.4  718.02   823.5  731.84
   897.9  735.92  1010.5   754.7  1049.2  767.96  1125.4  808.57  1144.2   813.1
  1158.3  821.17  1219.2  877.57  1267.3  916.65  1370.3  989.77  1405.6 1004.89
#Mann= 8 ,-1,0
       0      .1       0   651.1    .045       0   747.9     .07       0
  780.37     .06       0  790.37     .07       0  825.37     .06       0
  922.87     .05       0 1016.62      .1       0
Bank Sta=651.1,747.9
XS Rating Curve= 0 ,0
Exp/Cntr(USF)=0,0
Exp/Cntr=0.3,0.1

Type RM Length L Ch R = 1 ,64318   ,495.6,500,506.9
XS GIS Cut Line= 6
1638914.57144822462687.2107501481638958.92765872462778.753874138
1639000.38984613 462870.51779823 1639034.3648438462963.143925309
1639064.25028272463055.294003472 1639374.8031393464012.833426982
#Sta/Elev= 30
       0  1012.4    73.6  992.48   126.6  953.86   252.4  873.84     276  854.28
   366.9  811.58   432.4  758.63   456.5  745.62   546.2  724.19     669 713.402
   684.5  712.56   733.8713.3945   749.7   714.8   763.5  724.73   794.5  725.02
   860.1  738.13   908.4  755.38   960.1  766.44   991.1  780.24  1022.2  803.35
    1067  819.64  1108.4  843.79    1132  862.11  1149.8  881.92  1174.1  894.23
  1285.9  991.68  1318.8 1008.63  1332.6 1022.44  1346.4 1027.46  1404.6 1033.09
#Mann= 4 ,-1,0
       0      .1       0     669    .045       0   733.8     .06       0
   869.2      .1       0
Bank Sta=669,733.8
XS Rating Curve= 0 ,0
Exp/Cntr(USF)=0,0
Exp/Cntr=0.3,0.1

Type RM Length L Ch R = 1 ,63818   ,498.1,500,505.8
XS GIS Cut Line= 6
1638585.47138464 462784.681355731638598.75875963462883.650317892
 1638621.9227553463080.1781400591638633.42765355 463176.42269823
1638645.75702523463269.3792052271638784.57072397464171.653975472
#Sta/Elev= 30
       0   994.7    51.2  985.22   143.8  934.85   213.2  885.29   285.8  828.67
   312.3  819.36   351.9  790.42   391.6  768.64     418  758.18   461.1  747.34
   520.7  720.58   613.7  723.93   678.2712.5339     690  711.41   748.7712.5567
   766.4  722.03   789.6  723.37   809.5  733.98   869.1  739.73   922.4  756.31
   979.4  789.26  1005.4  814.96  1038.6  833.07  1078.4     873  1101.6  890.41
  1225.8  959.23  1320.7 1003.04  1352.4  1012.9  1380.5 1036.79  1401.3 1050.23
#Mann= 5 ,-1,0
       0      .1       0   678.2    .045       0   748.7     .07       0
  820.95     .06       0  845.95      .1       0
Bank Sta=678.2,748.7
XS Rating Curve= 0 ,0
Exp/Cntr(USF)=0,0
Exp/Cntr=0.3,0.1

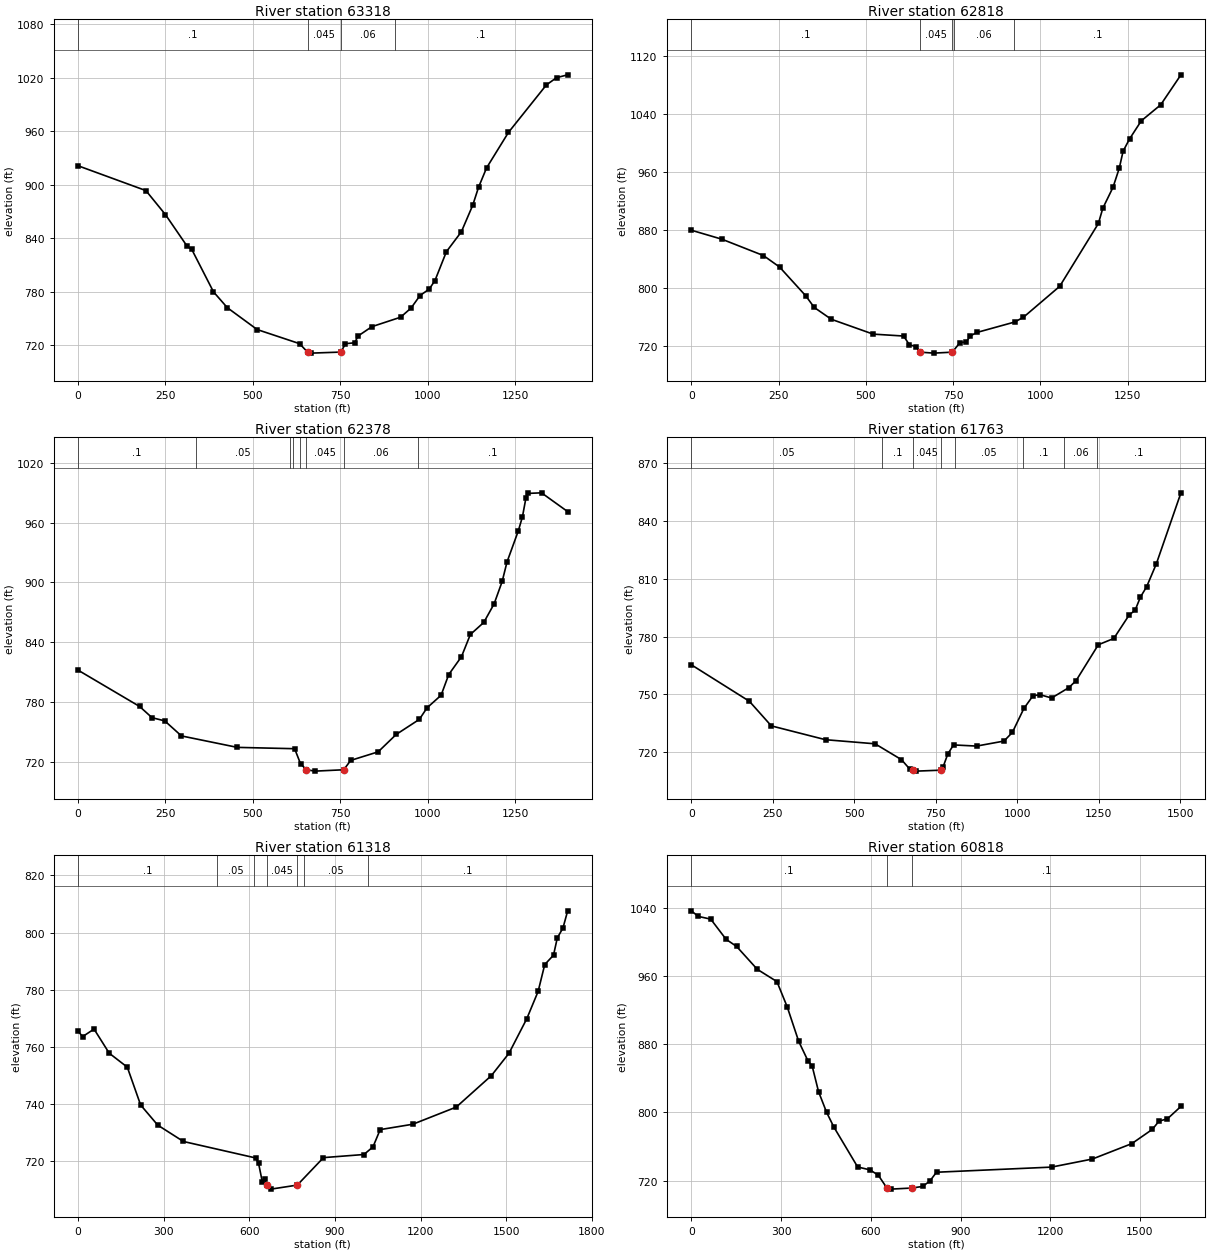
Type RM Length L Ch R = 1 ,63318   ,476.4,500,523.7
XS GIS Cut Line= 6
1638163.69073214462779.0993458931638185.80879813463785.496939391
1638187.93805897463882.348451734 1638190.4039333463980.755735233
 1638193.3389668 464079.933686481638196.50857989464179.497463733
#Sta/Elev= 30
       0  921.26   194.2  893.39     250   866.5   312.3  830.89   325.4  827.42
   387.5  779.82   427.2  762.01   512.5  737.51   633.9  721.67   656.5712.2388
   666.7  711.06   751.9712.2328   765.2  721.67   791.4  722.63   801.3  730.31
   840.6  740.73   922.7  751.33   952.7  761.59   978.5   775.7  1004.7  782.91
  1021.1  792.41  1053.9  824.89  1096.6  847.13  1129.2  876.96  1145.8  897.07
  1168.8  918.86  1231.5  958.72  1339.8 1011.89    1369 1020.08  1400.8 1023.26
#Mann= 4 ,-1,0
       0      .1       0   656.5    .045       0   751.9     .06       0
  905.39      .1       0
Bank Sta=656.5,751.9
XS Rating Curve= 0 ,0
Exp/Cntr(USF)=0,0
Exp/Cntr=0.3,0.1

Type RM Length L Ch R = 1 ,62818   ,441.9,440.5,438.6
XS GIS Cut Line= 6
1638013.91084798462778.3874050531637976.94307414462872.339644983
1637932.15838681 462961.170175971637885.79561864463048.136209399
1637751.74175289463291.8696458041637366.46299589464021.821597978
#Sta/Elev= 30
       0  879.77    88.1  867.33   206.7  844.89   252.8  829.14   327.8  789.55
   352.2  773.52     401  757.26   520.8  736.82   608.2  734.17   624.9   722.1
   643.5  719.74   655.7711.9887   694.7  710.66   747.6711.9826   769.6  725.13
   787.5  725.97   799.3  734.37   817.8  739.05   926.3  753.45   951.4  759.99
  1055.3  802.55  1166.1     889  1178.8  909.98    1208  938.76  1225.9  964.95
    1237  988.59  1255.6 1005.47    1289 1030.25  1344.6 1052.26  1402.6 1093.54
#Mann= 5 ,-1,0
       0      .1       0   655.7    .045       0   747.6      .1       0
  752.17     .06       0  924.67      .1       0
Bank Sta=655.7,747.6
XS Rating Curve= 0 ,0
Exp/Cntr(USF)=0,0
Exp/Cntr=0.3,0.1

Type RM Length L Ch R = 1 ,62378   ,617.6,614.8,610.7
XS GIS Cut Line= 6
1637605.51188666462572.6180992561637562.20652707462662.321331931
1637125.76317424463566.3926865141637083.18287883463655.144805594
1637040.90540432463744.9103740881636998.77983241463835.183159424
#Sta/Elev= 30
       0  811.87   176.2  775.38   211.7  764.14   248.1  760.91   295.9  745.81
   455.7  734.31   619.7  732.98   636.5  717.92   653.5711.8536     678  710.47
   760.1711.8381   780.1  721.24   858.6  729.83   910.2  747.28   976.5  762.44
   998.6  774.07  1038.7  786.65  1060.5  807.41    1097  825.38  1122.4  847.65
  1160.9  859.78  1190.4  878.43  1213.4  900.87  1227.3  920.48  1259.4  951.48
  1271.4  965.78  1281.5  984.95  1285.9  989.28    1326  989.87  1400.8  971.01
#Mann= 8 ,-1,0
       0      .1       0  337.27     .05       0  605.39     .08       0
  615.39     .05       0  635.39     .08       0   653.5    .045       0
   760.1     .06       0  972.89      .1       0
Bank Sta=653.5,760.1
XS Rating Curve= 0 ,0
Exp/Cntr(USF)=0,0
Exp/Cntr=0.3,0.1

Type RM Length L Ch R = 1 ,61763   ,452.1,444.7,430.6
XS GIS Cut Line= 6
1637001.75658333462302.669109098 1636819.3012396462755.159345842
1636693.08692509463068.1708589261636625.30490843463236.269604094
 1636589.0769625463326.115553014 1636809.5712933463657.928724824
#Sta/Elev= 30
       0  765.41   178.2  746.44   245.5  733.66   411.7  726.48   563.8  724.35
   644.6  716.13   669.9  711.27   680.6  710.84     690  710.16   765.5  710.65
   772.5   712.4   786.7  719.02   804.4  723.77   875.1  723.17   959.1  725.77
   984.8  730.26  1020.2  742.72  1048.5  749.39  1070.7  749.81  1105.2  748.15
  1157.7  753.48  1180.1  757.11  1248.5   775.8    1296  779.07  1343.4  791.32
  1361.3  793.71  1377.8   800.6  1396.7  805.93  1426.4  817.81  1501.9  854.71
#Mann= 8 ,-1,0
       0     .05       0  585.39      .1       0   680.6    .045       0
   765.5      .1       0  810.39     .05       0 1016.64      .1       0
 1143.52     .06       0 1243.52      .1       0
Bank Sta=680.6,765.5
XS Rating Curve= 0 ,0
Exp/Cntr(USF)=0,0
Exp/Cntr=0.3,0.1

Type RM Length L Ch R = 1 ,61318   ,553.4,500,408.3
XS GIS Cut Line= 6
1636439.68860272 462124.141010151636296.24728855462936.971733555
1636322.27446747463034.898374975 1636366.6024628463149.243290648
1636525.08213273463417.1397364741636721.16343348  463712.0325194
#Sta/Elev= 30
       0  765.51      16  763.55    56.1   766.2   109.3  757.75   172.6  752.86
   219.2  739.63   279.2  732.57   369.1  726.84   622.3  721.07   632.3   719.2
   645.7  712.57   653.6  713.69     662711.5756   675.6  710.16   767.9 711.575
   859.6  721.19  1001.3  722.28    1033  724.95  1058.2     731  1172.4  732.88
  1324.7  738.89  1447.6   749.9  1509.2  757.72  1571.7  769.84  1611.3  779.38
  1634.5  788.79  1665.2  792.07  1678.5  798.13  1698.3  801.57  1714.8   807.6
#Mann= 7 ,-1,0
       0      .1       0  487.89     .05       0  615.39      .1       0
     662    .045       0   767.9      .1       0  790.39     .05       0
 1016.72      .1       0
Bank Sta=662,767.9
XS Rating Curve= 0 ,0
Exp/Cntr(USF)=0,0
Exp/Cntr=0.3,0.1

Type RM Length L Ch R = 1 ,60818   ,514.5,500,487.9
XS GIS Cut Line= 6
1635370.82787955462903.5895824731636236.87339155463192.267154723
 1636323.9017608463227.927844554 1636417.3307078463317.703583643
 1636514.4072853463436.8106288911636718.49480364463716.950488567
#Sta/Elev= 30
       0 1036.45    23.5  1029.9      65 1026.71   116.4 1003.02   151.4  994.71
   220.6  967.87   286.3  953.46   320.9  923.61   358.9  883.54   390.1  860.46
   403.9  854.69   425.4  824.42   452.3   800.2   476.5  782.97   556.1  736.12
   597.6  732.67   625.1  726.45     654  711.39   666.7  710.12   736.5711.3931
   773.9   713.3   798.1   719.9   819.7  729.93  1204.2  735.94  1340.9  745.42
  1472.7   763.5  1541.3  780.21  1563.5  789.85  1591.7  792.57  1636.8  807.12
#Mann= 3 ,-1,0
       0      .1       0     654    .045       0   736.5      .1       0
Bank Sta=654,736.5
XS Rating Curve= 0 ,0
Exp/Cntr(USF)=0,0
Exp/Cntr=0.3,0.1

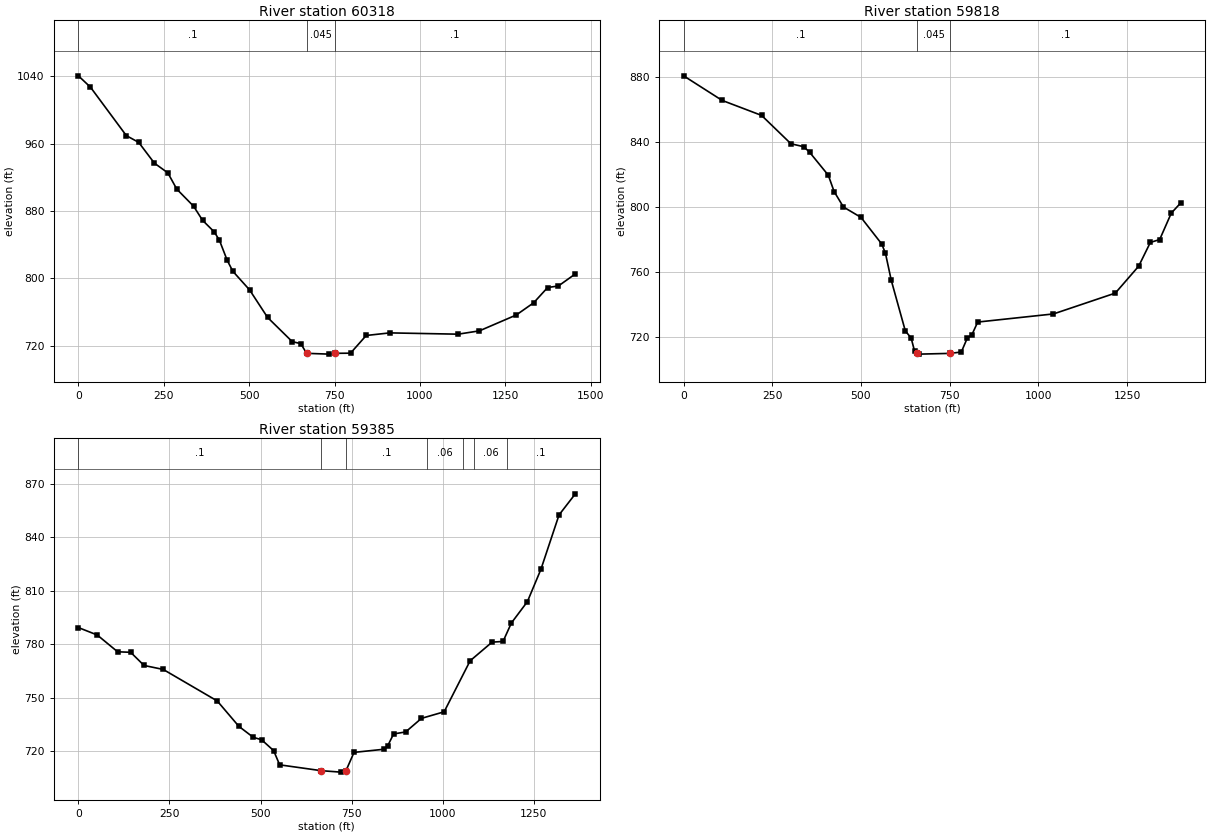
Type RM Length L Ch R = 1 ,60318   ,502.6,500,495.7
XS GIS Cut Line= 4
 1635311.7620528 463621.651138471636513.71535756 463621.65113847
1636614.55373855463664.3456068931636718.32157564463763.160369888
#Sta/Elev= 30
       0 1040.61    35.4  1027.1   140.4  969.55   176.5  961.57   222.4  936.89
   261.8  925.33     288  906.02   337.3  885.66   363.5  868.95   397.5  855.25
   412.7  845.38   435.7  821.31   452.1  808.41   501.3  786.19   553.8  753.56
     626  724.79     651  722.44     668710.9172   734.2  709.97     751710.9295
   796.6   711.1   842.5  732.11   911.4  735.21  1111.5  733.67  1173.9  737.62
  1281.9  756.49  1332.8     771  1373.5  789.08  1405.2  790.97  1454.7  805.28
#Mann= 3 ,-1,0
       0      .1       0     668    .045       0     751      .1       0
Bank Sta=668,751
XS Rating Curve= 0 ,0
Exp/Cntr(USF)=0,0
Exp/Cntr=0.3,0.1

Type RM Length L Ch R = 1 ,59818   ,434.1,433.4,431.6
XS GIS Cut Line= 6
1635314.31224455464168.3170398921635413.82385655464163.398742646
1635610.97798981464149.3160936391636415.17880923464091.873623222
1636612.33294247464077.7919584811636711.79435772464072.171234816
#Sta/Elev= 30
       0  880.79   108.5  865.65   219.8   856.4   302.5  838.93   338.7  837.11
   355.2  833.68   407.8  819.56   424.2  809.49   450.5  799.96   499.9  793.58
   558.5  777.16     569  771.38   585.4  754.72   624.9  723.63   641.3  719.26
   651.2  710.98  659.07709.7645   664.3  709.31  752.23709.7765   782.8  710.63
   799.2  718.99   812.4  721.16     829  729.07  1042.6  734.08  1216.9  746.92
  1282.7  763.49  1315.6  778.14  1341.9   779.9  1374.7  796.22  1400.8  802.38
#Mann= 3 ,-1,0
       0      .1       0  659.07    .045       0  752.23      .1       0
Bank Sta=659.07,752.23
XS Rating Curve= 0 ,0
Exp/Cntr(USF)=0,0
Exp/Cntr=0.3,0.1

Type RM Length L Ch R = 1 ,59385   ,684.2,715,745.8
XS GIS Cut Line= 3
 1635400.6415483464599.8676682541636293.82633046464518.942746629
1636752.72587424464608.229550177
#Sta/Elev= 30
       0  789.36    51.7   785.2   107.7  775.78   143.5  775.49   180.2  768.12
   232.9  765.88   381.2  748.21   440.5  733.99     480  727.84     503  726.45
     536  720.37   552.5   712.4   666.8709.1194   720.2  708.31   734.7  709.13
   756.7  719.38   839.1  721.14   848.9  722.96   865.4  729.72   898.4  730.84
   941.8  738.45  1004.1  742.13  1075.5  770.74  1135.7  781.19  1165.8  781.57
  1188.7  791.92  1232.6  803.87  1269.9  822.07  1319.5   852.5  1364.3  864.34
#Mann= 7 ,-1,0
       0      .1       0   666.8    .045       0   734.7      .1       0
  956.84     .06       0 1056.84      .1       0 1086.84     .06       0
 1176.84      .1       0
Bank Sta=666.8,734.7
XS Rating Curve= 0 ,0
Exp/Cntr(USF)=0,0
Exp/Cntr=0.3,0.1