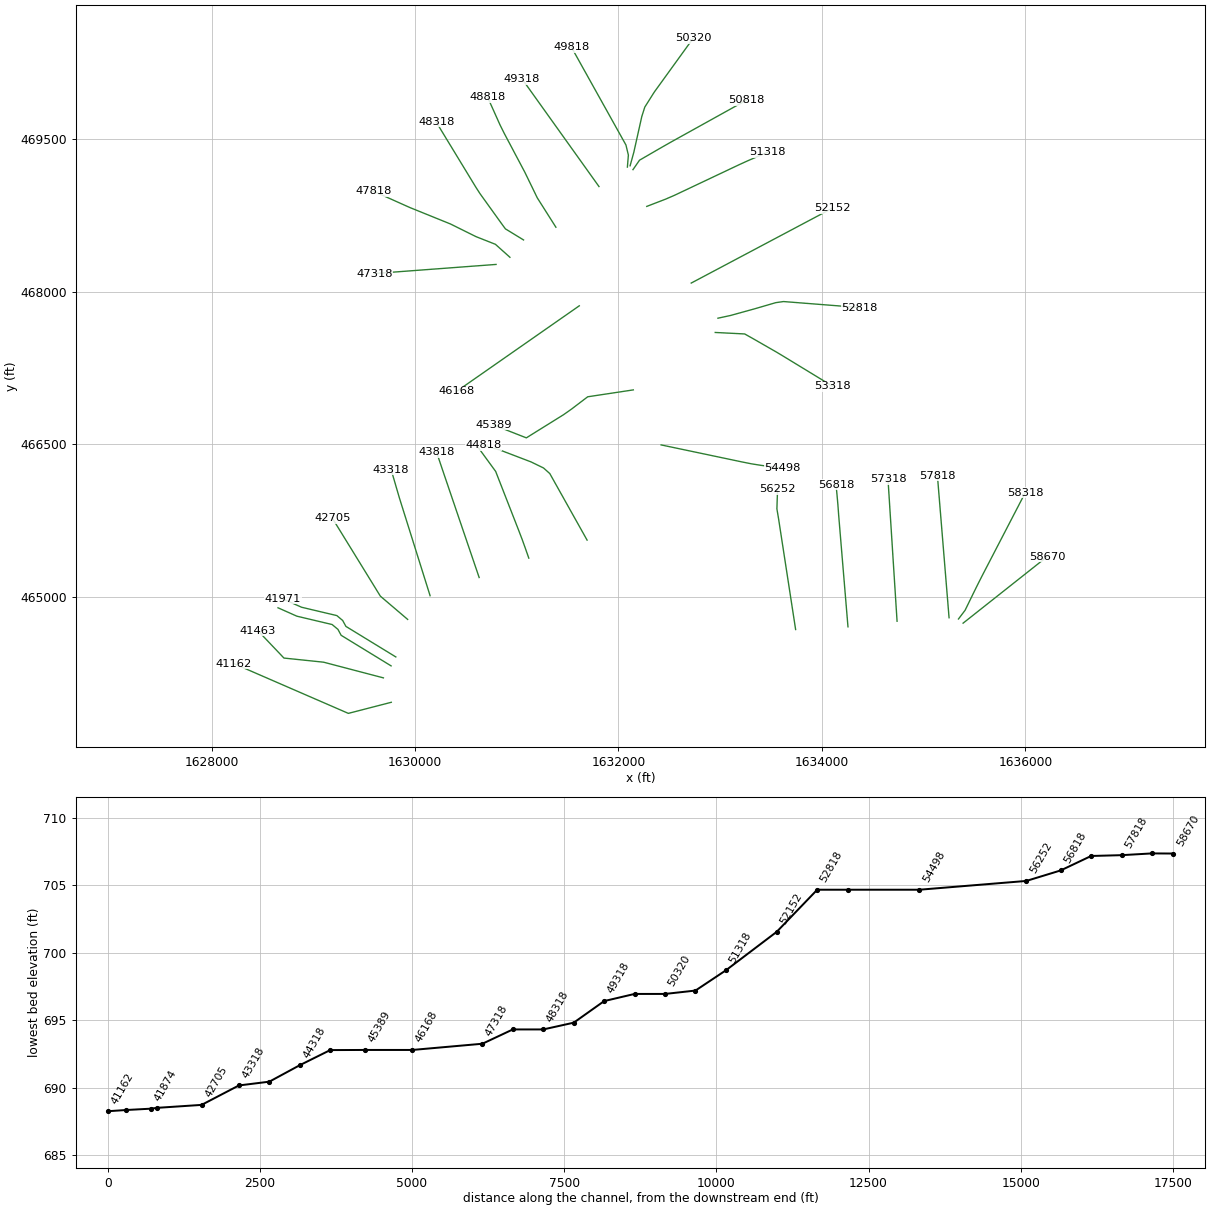
HEC-RAS study FshCrk.prj: FshCrk

--- FshCrk.g01 (geometry) --- (continued)

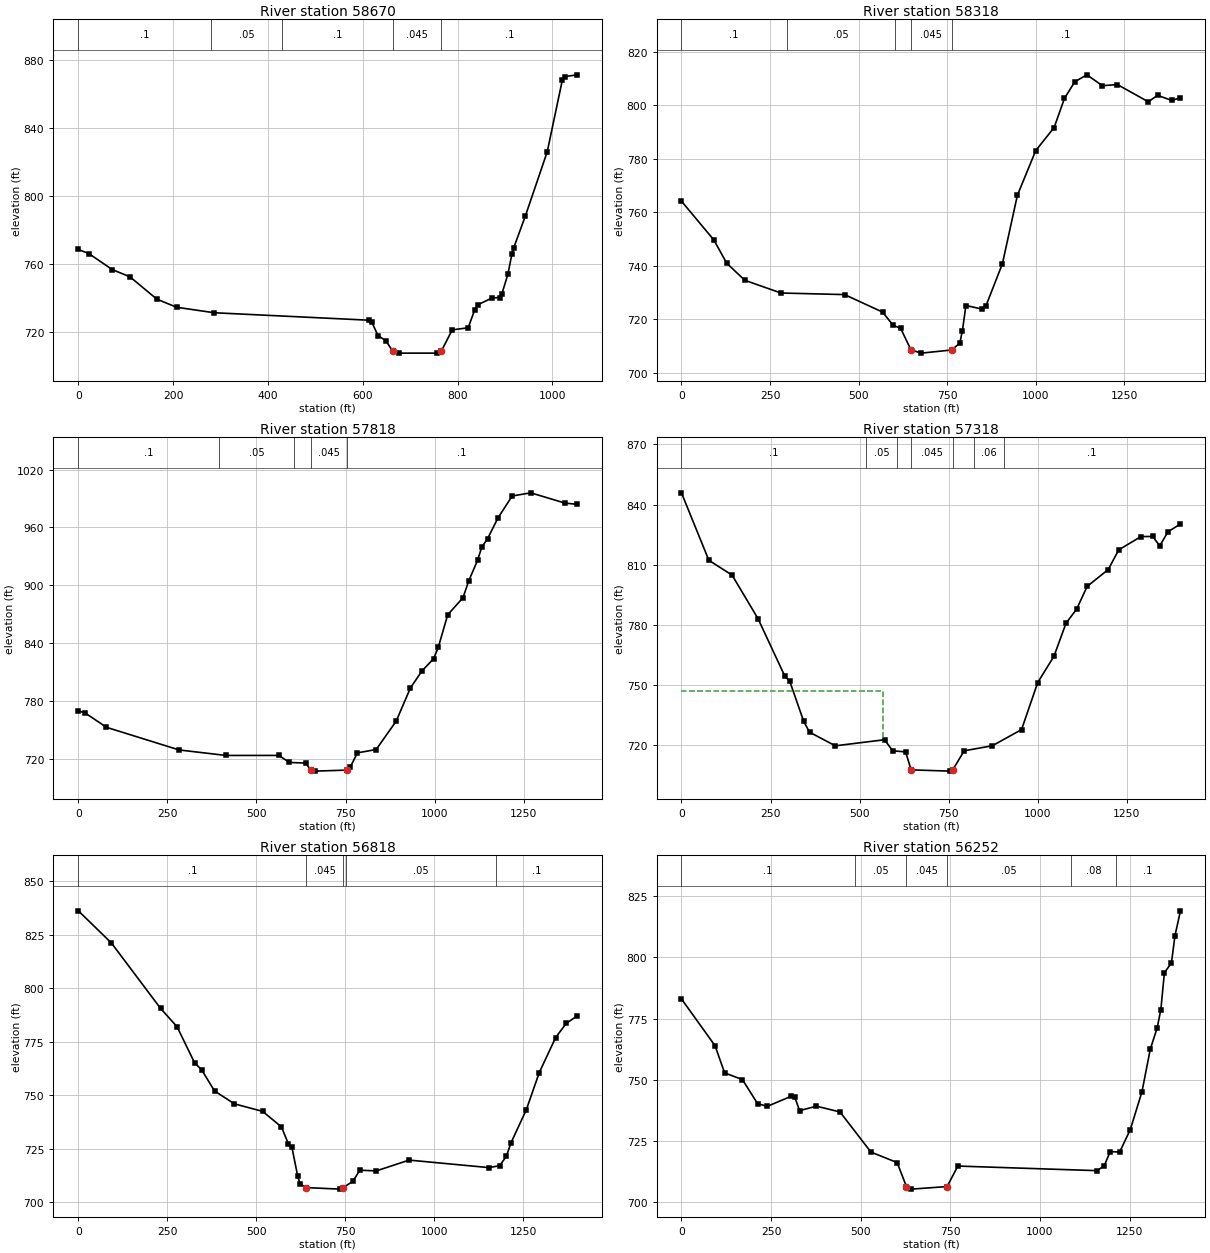
Type RM Length L Ch R = 1 ,58670   ,327,351.6,372.8
XS GIS Cut Line= 2
1635388.11459039 464741.099686981636213.44378866465394.560683713
#Sta/Elev= 30
       0  768.45    21.9  766.07    71.6   756.6     109  752.31   165.4  739.19
   207.2  734.39   286.7  731.15   613.8  726.74   619.1  725.59   632.1  717.66
   648.5   714.7   662.9708.6311   677.3  707.34   756.5  707.34     766708.6334
   788.6  721.05   822.4  722.29   835.8  732.67   842.3  735.83   872.8  739.85
   888.7  740.12   893.5  742.36   906.1  753.79   914.4  765.53   918.6  769.58
   942.8  788.07   989.1  826.07  1020.8  868.11  1026.8  870.44  1052.7  871.45
#Mann= 5 ,-1,0
       0      .1       0     280     .05       0     430      .1       0
   662.9    .045       0     766      .1       0
Bank Sta=662.9,766
XS Rating Curve= 0 ,0
Exp/Cntr(USF)=0,0
Exp/Cntr=0.3,0.1

Type RM Length L Ch R = 1 ,58318   ,468.9,500,529.4
XS GIS Cut Line= 6
1635342.73869689464782.0733583121635407.57977456464867.640116304
1635494.25282955465045.3457976431635537.26685114465132.166162059
1635579.76446955465215.7335802321635999.98836663466026.154203475
#Sta/Elev= 30
       0  764.13    91.4  749.64   127.7  740.95   178.9  734.56     281  729.81
   460.5  729.22   567.8  722.68   597.3  717.78   618.8   716.6   647.9708.5352
   677.2  707.35   762.5708.5218   785.7  711.06   793.1   715.8     803  725.14
   848.6  723.81   859.8   725.1     906  740.76   948.3  766.35  1000.1  783.03
    1052  791.65  1081.2  802.55  1110.4  808.75  1144.5  811.33  1188.3  807.27
  1230.6  807.69  1317.9  801.25  1343.8  803.68  1384.4  801.74  1408.6  802.81
#Mann= 5 ,-1,0
       0      .1       0  296.61     .05       0  603.22      .1       0
   647.9    .045       0   762.5      .1       0
Bank Sta=647.9,762.5
XS Rating Curve= 0 ,0
Exp/Cntr(USF)=0,0
Exp/Cntr=0.3,0.1

Type RM Length L Ch R = 1 ,57818   ,500.8,500,499
XS GIS Cut Line= 6
1635250.17490564464794.1779928951635225.89083347465090.450366229
1635210.31770189465280.4378471371635188.87384714465542.060683474
1635182.74754706465616.809877813 1635135.7427198466190.277562886
#Sta/Elev= 30
       0   769.8    19.6   767.4    78.9  752.66     283  729.17   414.3  723.48
   562.8  723.51   592.4  716.21   638.5  715.57   652.1708.2756   664.8  707.22
     753708.2788   763.6  711.62   783.3  726.16     836  729.64     892  758.97
   932.2  793.54   964.4  811.06   997.3  823.87  1010.5  835.78  1036.8  869.42
  1079.6  887.01  1096.1  904.76  1120.7  925.99  1132.3  939.46  1148.7  948.27
  1178.3  970.09  1217.9  992.58  1269.9  995.86    1366  985.22  1400.8  983.91
#Mann= 5 ,-1,0
       0      .1       0  394.14     .05       0  605.39      .1       0
   652.1    .045       0     753      .1       0
Bank Sta=652.1,753
XS Rating Curve= 0 ,0
Exp/Cntr(USF)=0,0
Exp/Cntr=0.3,0.1

Type RM Length L Ch R = 1 ,57318   ,498.8,500,501.9
XS GIS Cut Line= 6
1634738.94200422464759.948730648 1634707.8636543465246.848347396
1634691.14223105465508.8153431421634686.36500964465583.662962481
1634680.79087381465670.9852943871634649.71318005466157.885239229
#Sta/Elev= 30
       0  845.85    76.9  812.24   142.2  804.81     215  783.12   290.6  754.32
   303.8  752.03   343.2  731.94   359.6  726.55     432  719.78     570   722.8
   593.1  717.28   629.2  716.75   644.7 707.789   754.3  707.16   761.6707.7946
   793.6  717.29   872.5  719.79   954.7  727.86  1000.1  751.32  1045.7  764.41
  1079.6  780.92  1109.4  787.91  1138.8   799.2    1198  807.63  1227.5  817.43
    1290  824.05  1322.9  824.11  1342.6  819.44  1365.9  826.47  1400.8  830.32
#Mann= 7 ,-1,0
       0      .1       0  517.89     .05       0  605.39     .08       0
   644.7    .045       0   761.6      .1       0  820.39     .06       0
  905.39      .1       0
#XS Ineff= 2 , 0
           567.1  747.11
Permanent Ineff=
       F       F
Bank Sta=644.7,761.6
XS Rating Curve= 0 ,0
Exp/Cntr(USF)=0,0
Exp/Cntr=0.3,0.1

Type RM Length L Ch R = 1 ,56818   ,561,565.7,569.2
XS GIS Cut Line= 6
1634256.30878314464704.9701660571634180.49791114465614.707519814
1634164.66690606465804.6740033921634157.51206473465902.857862145
1634148.68990389466001.949527472 1634139.0380203466101.495588228
#Sta/Elev= 30
       0  836.15    92.7  821.14     231  790.52   277.1     782   326.4  765.13
   346.2  761.86   382.4  751.97   438.4  745.93   517.4  742.44   570.3  735.18
   589.8  727.28   599.7  725.66   616.1  712.14   622.7  708.48   640.2706.8073
   734.7  706.09   743.6 706.792   770.9  709.72   790.6  714.94   836.7   714.6
   928.9  719.66  1152.7  716.15    1183  717.02    1202  721.42  1215.3  727.82
  1258.1  743.18  1294.3   760.5  1340.4  776.92  1370.1  783.52  1401.5  787.13
#Mann= 5 ,-1,0
       0      .1       0   640.2    .045       0   743.6      .1       0
  750.39     .05       0 1173.52      .1       0
Bank Sta=640.2,743.6
XS Rating Curve= 0 ,0
Exp/Cntr(USF)=0,0
Exp/Cntr=0.3,0.1

Type RM Length L Ch R = 1 ,56252   ,1867.4,1754.2,1632.3
XS GIS Cut Line= 6
1633741.62425419464678.4124490191633642.72681419465321.240231605
1633602.81088353465580.6875473581633573.82373678465769.095635103
1633557.50355944465866.1807427721633564.01535745466056.111847356
#Sta/Elev= 30
       0  783.06    93.8  763.91   120.3  752.84   170.1  750.07   212.5  740.22
   239.8  739.17   306.2  743.28   316.2  742.88   329.5  737.39   376.5  739.22
   442.3  736.85   528.6  720.45   601.6  716.17   627.6706.3615   641.5  705.31
   741.1  706.36   770.9  714.74  1159.4  712.86  1179.4  714.87    1196  720.66
  1222.4  720.47    1252  729.63  1284.7  745.17  1307.7  762.44  1326.8  771.14
  1337.3  778.69  1347.2  793.81  1366.8  797.72  1376.7  808.93    1392  819.07
#Mann= 6 ,-1,0
       0      .1       0  484.14     .05       0   627.6    .045       0
   741.1     .05       0 1086.64     .08       0 1211.96      .1       0
Bank Sta=627.6,741.1
XS Rating Curve= 0 ,0
Exp/Cntr(USF)=0,0
Exp/Cntr=0.3,0.1

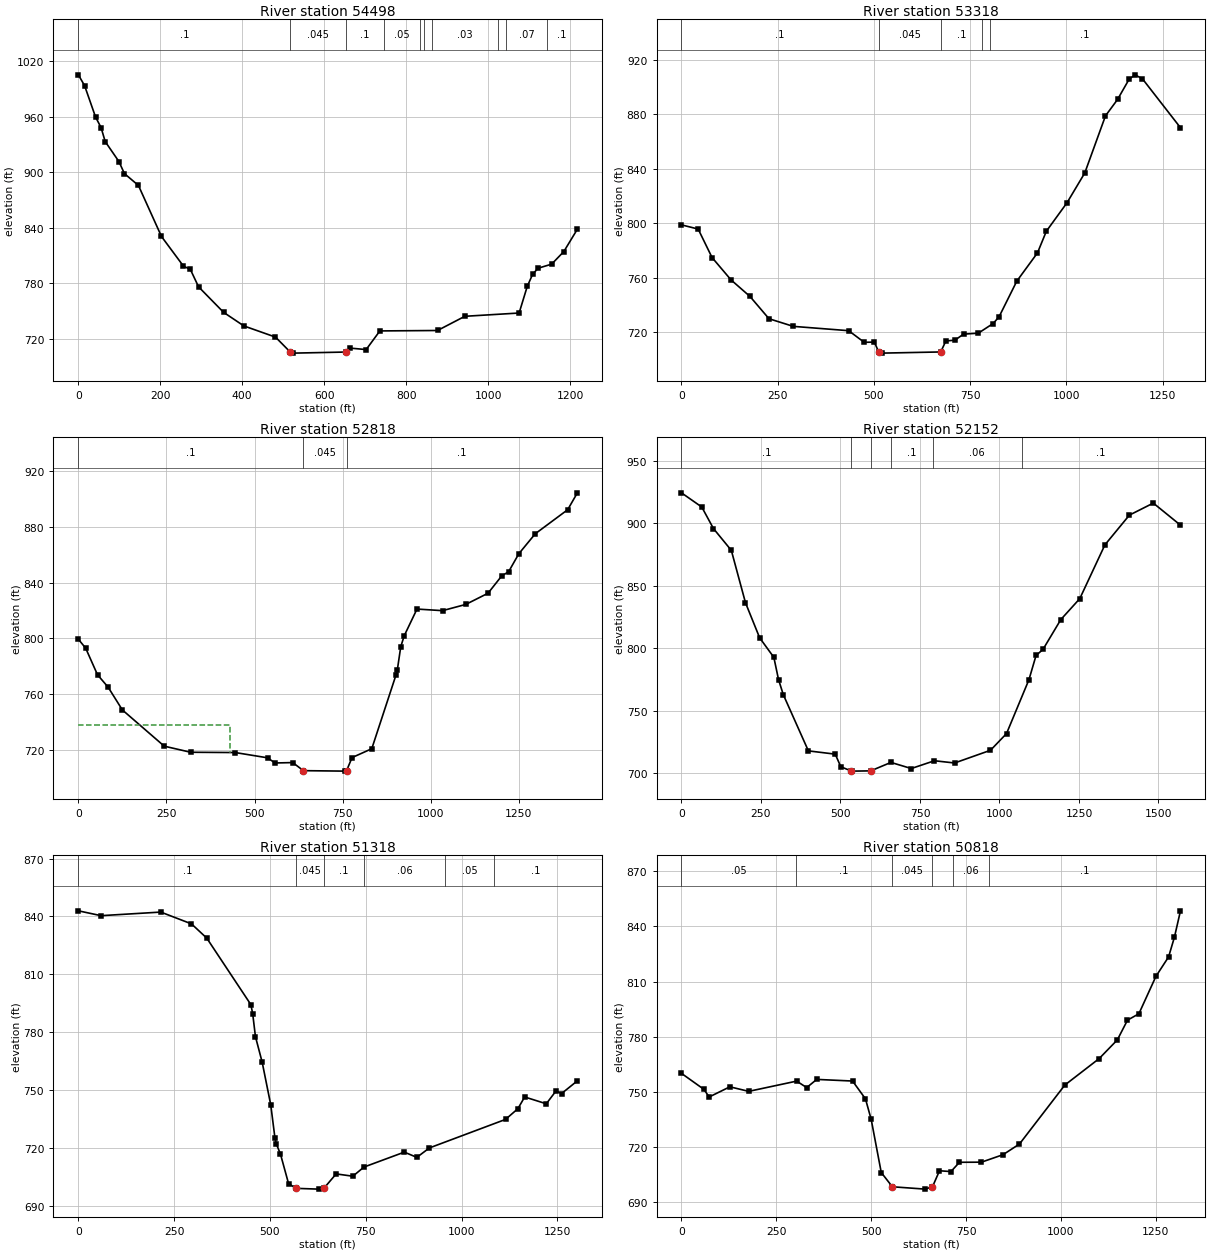
Type RM Length L Ch R = 1 ,54498   ,1202.9,1180.5,1158.4
XS GIS Cut Line= 6
1632418.96955551466494.826250748 1633055.7911165466360.756965087
1633214.80523417466327.2793417441633306.72532592466308.825310411
 1633402.5227065466293.6206164081633614.87467248466266.784411551
#Sta/Elev= 30
       0 1005.46    15.2  993.74      42  959.79    55.4  948.48    65.5  933.33
      99  911.74   112.4  898.71   146.6  885.92   202.9  830.72   256.6  798.64
   273.3  795.22   293.4  776.33   354.3  748.81     404  734.06   481.2  721.98
   517.2705.8517   524.8  704.66   653.5705.8394   662.3  710.12   702.5  708.51
     736  728.66   876.7  729.12   943.4  744.47  1075.9  748.01  1095.8  776.87
    1109  789.96  1122.2  796.42  1155.3  800.84  1185.1  814.49  1218.1  838.63
#Mann= 10 ,-1,0
       0      .1       0   517.2    .045       0   653.5      .1       0
  745.78     .05       0  833.28     .03       0  843.28     .07       0
  863.28     .03       0 1024.03     .08       0 1044.03     .07       0
 1144.03      .1       0
Bank Sta=517.2,653.5
XS Rating Curve= 0 ,0
Exp/Cntr(USF)=0,0
Exp/Cntr=0.3,0.1

Type RM Length L Ch R = 1 ,53318   ,456.8,499.5,524.8
XS GIS Cut Line= 6
1632951.50108005467601.0673929581633240.68876714467586.464731142
1633322.77718563467540.5123952331633550.51491913467409.559245065
1633614.83959363467371.0439021441634106.03939864467071.595025972
#Sta/Elev= 30
       0  798.88    43.4  795.79    79.5  774.87   128.8  758.45   178.1  746.28
   227.4  729.93   290.5  724.32   434.5  721.14   474.8  712.61   501.3  712.76
   512.4 705.555   520.3  704.66   673.7705.5242     687  713.59   710.5  714.18
   732.9   718.6   771.4  719.33   809.8   726.4   825.2  731.32   871.3  757.51
   925.1  778.31   948.1  794.19  1001.9  815.16    1048  837.02  1101.8  878.97
  1133.1  890.97  1163.3  905.92  1178.6  909.08  1197.9  906.12  1296.6  870.25
#Mann= 5 ,-1,0
       0      .1       0   512.4    .045       0   673.7      .1       0
  781.31     .07       0  801.31      .1       0
Bank Sta=512.4,673.7
XS Rating Curve= 0 ,0
Exp/Cntr(USF)=0,0
Exp/Cntr=0.3,0.1

Type RM Length L Ch R = 1 ,52818   ,607.1,665.7,696.3
XS GIS Cut Line= 6
1632977.84906971467741.4519539771633102.49481781467768.444354057
1633341.08423564 467834.463250891633546.16092522467894.335834563
1633622.47081198467905.2774137261634370.54313472467846.334618226
#Sta/Elev= 30
       0  799.41    20.8  792.96    54.3  773.88    84.5  764.95   124.8  748.63
   243.8  722.58   318.7  718.21   445.1  718.01   537.3  714.21   557.8  710.51
   608.5   710.8   638.6705.0009     757  704.66   761.2705.0064   776.7  714.39
   832.7  720.75   901.8  774.01   905.1  777.17     915  794.09   924.8   801.9
     961  821.08  1033.5  819.93  1099.3  824.39  1162.6  832.44  1201.3  844.82
  1221.1  847.92  1250.2  860.87  1296.7  875.17  1388.7  892.44  1416.2  904.57
#Mann= 3 ,-1,0
       0      .1       0   638.6    .045       0   761.2      .1       0
#XS Ineff= 2 , 0
          428.92  738.12
Permanent Ineff=
       F       F
Bank Sta=638.6,761.2
XS Rating Curve= 0 ,0
Exp/Cntr(USF)=0,0
Exp/Cntr=0.3,0.1

Type RM Length L Ch R = 1 ,52152   ,834.3,834.3,831.3
XS GIS Cut Line= 2
1632715.29712655468087.1081926221634101.28339219 468822.70494865
#Sta/Elev= 30
       0  924.24    63.9  912.88   100.6  895.65   156.8   878.2   201.3  836.31
   245.9   808.2   290.5   792.6   305.3  774.74   320.2  762.75   399.1  717.75
   483.6  715.12     501  705.03  533.44701.7196   537.4  701.54   595.1  701.75
   658.7  708.51   722.7  703.62   795.6  709.85   858.8  708.05   971.7  718.22
  1022.2  731.61  1092.8  774.82    1115   794.1  1136.7   798.9    1193  822.86
  1252.5  839.57  1331.5   882.6  1408.5   906.4  1483.7  916.03  1569.1  898.37
#Mann= 6 ,-1,0
       0      .1       0  533.44    .045       0   595.1     .05       0
     660      .1       0     790     .06       0    1070      .1       0
Bank Sta=533.44,595.1
XS Rating Curve= 0 ,0
Exp/Cntr(USF)=0,0
Exp/Cntr=0.3,0.1

Type RM Length L Ch R = 1 ,51318   ,494.6,500,503.3
XS GIS Cut Line= 6
1632278.12835631468841.4120243941632463.09944305468912.638259888
1632552.03955388 468951.172959731633193.12783864469254.848205388
1633282.79465406469295.4996988921633465.97998323469373.233467311
#Sta/Elev= 30
       0  842.92    59.2  840.41     215  842.27   295.1  836.16     335  828.78
     450  794.33   454.8  789.68     462  777.75   479.6  764.46     502  742.32
   512.9   725.2   516.5  722.12   527.4  716.79   548.5  701.49   568.7699.0889
   626.7  698.69   640.4699.0795   672.6  706.58   716.1  705.38   745.2  710.13
   850.5  717.87   883.1  715.15   915.8  720.03  1114.5  734.82  1146.7  740.35
  1164.5  746.45  1220.9  742.92  1246.5  749.64  1260.7  748.21    1302  754.82
#Mann= 6 ,-1,0
       0      .1       0   568.7    .045       0   640.4      .1       0
   746.4     .06       0  957.65     .05       0 1084.52      .1       0
Bank Sta=568.7,640.4
XS Rating Curve= 0 ,0
Exp/Cntr(USF)=0,0
Exp/Cntr=0.3,0.1

Type RM Length L Ch R = 1 ,50818   ,474.6,498.4,523.6
XS GIS Cut Line= 6
1632142.45900822469202.7990968971632206.77679297 469295.91045922
1632375.72100888469393.9834258111632456.99840538469440.727426812
1632533.16426356469483.8024718911633254.68611448469884.646486476
#Sta/Elev= 30
       0  760.14      59  751.46    73.1   747.3   127.6  752.82   177.3  750.35
   303.6  755.92   330.1   752.4   356.6  756.85     451  755.96     485  746.27
   500.1  735.05   526.6  706.22   555.8698.4728   642.4  697.19   661.6698.4529
   680.1  707.18   710.2  706.73   732.7  711.78   790.7  711.85   847.5  715.91
   890.9  721.72  1010.4  753.77  1100.9  768.17  1148.8  778.34  1175.6  789.07
  1205.6  792.54  1250.6   812.9  1283.9  823.46  1299.4  834.27  1315.2  848.51
#Mann= 6 ,-1,0
       0     .05       0  301.62      .1       0   555.8    .045       0
   661.6      .1       0  714.78     .06       0  809.78      .1       0
Bank Sta=555.8,661.6
XS Rating Curve= 0 ,0
Exp/Cntr(USF)=0,0
Exp/Cntr=0.3,0.1

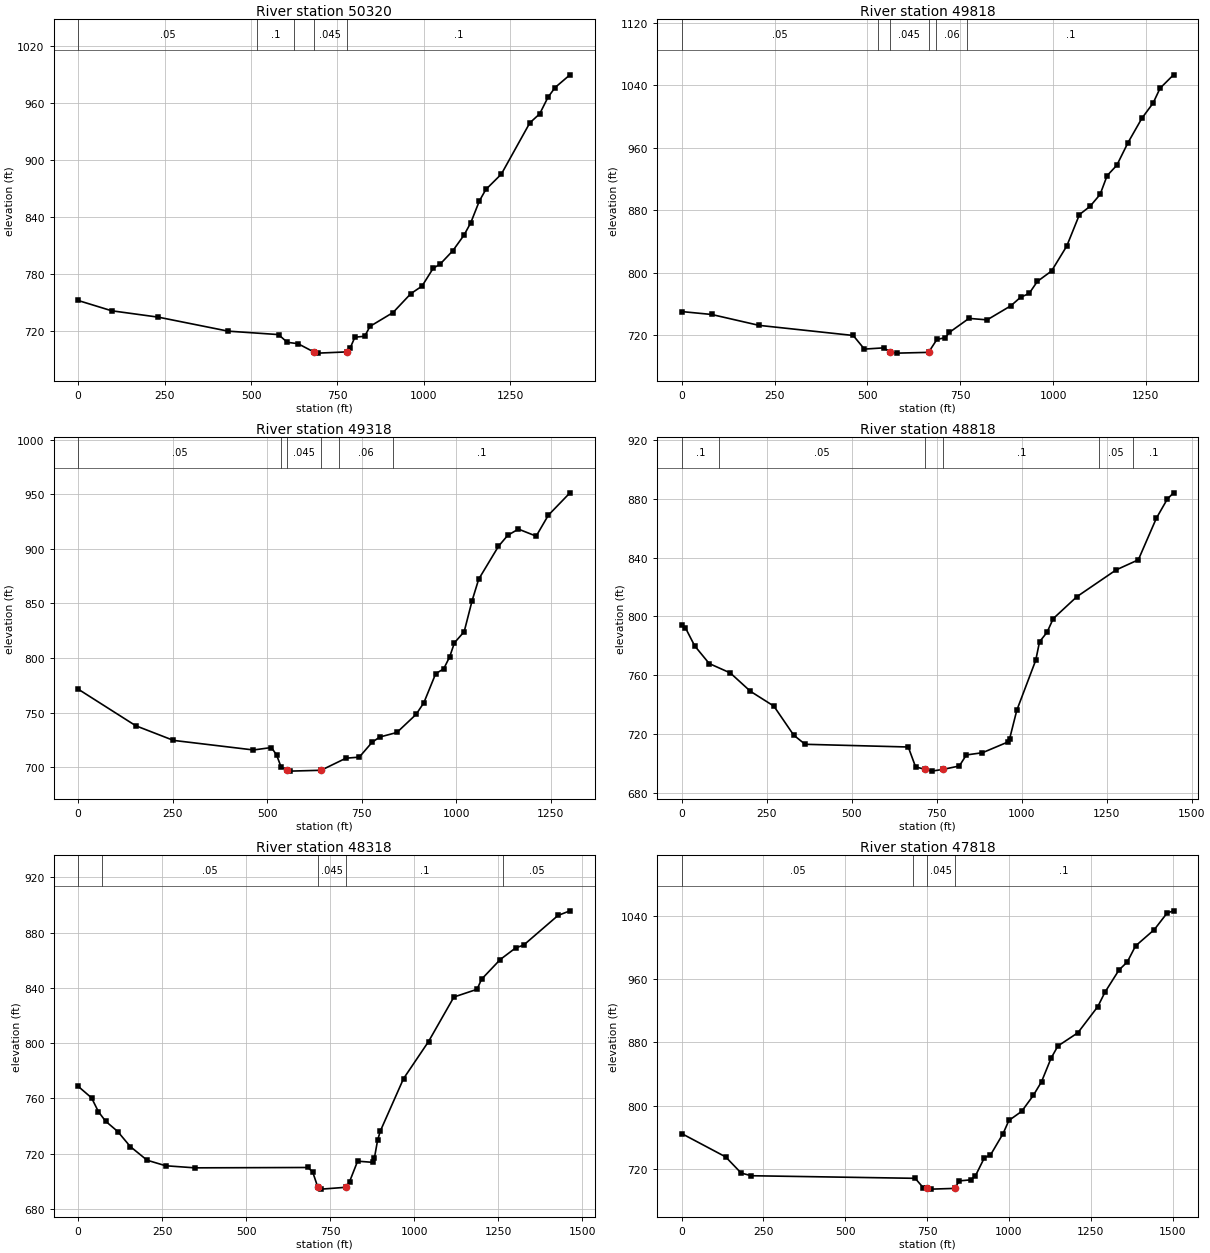
Type RM Length L Ch R = 1 ,50320   ,452.9,501.6,557.3
XS GIS Cut Line= 6
1632114.33832955469241.1041383891632150.53543563469372.519886062
1632229.25706297469725.6057940571632258.73633473469818.341829062
1632352.17085914469966.3904174721632734.11071205470494.910029724
#Sta/Elev= 30
       0  752.35    97.1   741.5   232.2  734.78   433.6  720.08   579.6  716.45
   604.8  708.32   635.7   706.9   681.3698.2452   694.5  696.94   777.6698.2481
   786.8  702.37   800.5   713.7   828.7  714.67   844.2  725.11   910.7  739.64
   962.2  759.52   994.6  767.47  1026.9  786.24  1047.2  790.68  1083.7  804.71
  1116.1  821.16  1135.6  834.17  1160.6  857.19  1179.2  869.16    1224  885.31
  1306.5  939.33  1334.9  948.74  1358.7  966.05  1379.4  976.44  1422.5  989.82
#Mann= 5 ,-1,0
       0     .05       0  518.09      .1       0   625.4    .025       0
   681.3    .045       0   777.6      .1       0
Bank Sta=681.3,777.6
XS Rating Curve= 0 ,0
Exp/Cntr(USF)=0,0
Exp/Cntr=0.3,0.1

Type RM Length L Ch R = 1 ,49818   ,493.4,500,504.4
XS GIS Cut Line= 6
1632087.74815963469227.9985215661632097.35476772469346.308652401
1632073.38795213469445.6401466431631901.52116989469754.118860394
1631816.34909613469906.9935546371631536.30470872470409.636250138
#Sta/Elev= 30
       0  750.15    80.7  746.42   208.1   732.5   461.9  719.53     492   702.1
   544.5   703.7   561.6697.9533     581  696.94   664.7  697.92   687.3  714.46
   709.8   716.7   720.9  723.52   773.6  741.41   822.5  739.53   886.3  757.53
   912.6  768.48   935.6  773.31   957.7  788.73   995.9  802.05  1036.9  833.99
  1071.1  874.35  1099.6  884.87  1126.7  900.12  1145.6  924.17  1171.7  937.48
  1201.8  966.41  1239.3  997.69  1269.4 1017.06  1288.2 1036.11  1324.4 1053.26
#Mann= 6 ,-1,0
       0     .05       0  529.01     .08       0   561.6    .045       0
   664.7      .1       0  684.01     .06       0  769.01      .1       0
Bank Sta=561.6,664.7
XS Rating Curve= 0 ,0
Exp/Cntr(USF)=0,0
Exp/Cntr=0.3,0.1

Type RM Length L Ch R = 1 ,49318   ,506.2,500,494.4
XS GIS Cut Line= 6
1631808.49773389469036.6567126361631637.30549097469276.326836973
1631531.95694838469423.8163713961631430.24127255 469566.22061415
1631281.29964131469774.7405383141631052.21086064470095.466274813
#Sta/Elev= 30
       0  771.52   152.6  737.95   252.2  724.56   463.9  715.79   511.4  718.01
     525  711.21   536.8  700.31   552.2697.1925   559.8  696.41   642.7697.1912
   708.5  708.25   743.8  709.23   777.5  722.75   797.8  727.62   843.3   731.8
   894.1  748.37   914.6  759.02     946  785.72     967  790.02   983.1  801.19
   995.4  813.89  1021.3  824.14  1042.4  852.67  1059.7  872.19  1112.1  902.35
  1136.5  912.35  1164.7  918.09  1211.8  911.63    1244  930.81  1301.2   951.3
#Mann= 6 ,-1,0
       0     .05       0  535.78     .08       0   552.2    .045       0
   642.7      .1       0  690.78     .06       0  833.28      .1       0
Bank Sta=552.2,642.7
XS Rating Curve= 0 ,0
Exp/Cntr(USF)=0,0
Exp/Cntr=0.3,0.1

Type RM Length L Ch R = 1 ,48818   ,496.1,500,502.5
XS GIS Cut Line= 6
1631384.82532478468636.4588043591631201.55734672468925.802275553
1631080.11106731469176.2040057331630878.33063097469557.335461304
 1630835.1076203469644.0662589821630713.33719455469915.737631649
#Sta/Elev= 30
       0  793.95      11  792.21    38.2  779.96    80.9  767.94     143  761.53
   202.3  749.05   271.2  738.98   329.4   719.3     363  713.05   666.5  711.21
     688  697.66     716696.0594   735.7  694.81   770.1696.0591   816.7  698.31
   837.3  705.81   884.6  707.31   959.9  714.64   964.7  716.87   985.7  736.16
  1041.4  770.15  1052.6  782.74  1074.6  789.13  1092.9  798.47  1162.3  813.35
  1277.9  831.57  1343.2  838.43  1396.2  866.67  1428.4  879.68  1446.7  883.96
#Mann= 6 ,-1,0
       0      .1       0     110     .05       0     716    .045       0
   770.1      .1       0 1228.96     .05       0 1327.51      .1       0
Bank Sta=716,770.1
XS Rating Curve= 0 ,0
Exp/Cntr(USF)=0,0
Exp/Cntr=0.3,0.1

Type RM Length L Ch R = 1 ,48318   ,465.5,500,520.6
XS GIS Cut Line= 6
1631066.94125893468511.2530070061630888.62378098 468620.28456827
1630858.05737755468661.5633027261630637.60473447468968.232964978
1630597.12712514 469031.397208721630207.36478131469672.623616561
#Sta/Elev= 30
       0  768.75    39.9  760.41    60.5  750.31    81.7  743.51   117.8  736.02
   155.2  725.13   205.2  715.25   260.4  711.23   347.5  709.72   683.7  709.97
   697.9  706.79   713.2695.6766   724.1  694.31   797.7695.6633   807.7  699.75
   831.6  714.55   876.9   713.7   881.7     717     891  729.62   899.1   736.3
   968.2  774.29  1042.6  801.15  1118.1  833.39    1187  838.99  1200.5  846.29
  1256.1  860.56  1302.2  869.01  1325.3  870.91  1427.9  892.45  1463.5   895.8
#Mann= 5 ,-1,0
       0      .1       0      70     .05       0   713.2    .045       0
   797.7      .1       0 1264.66     .05       0
Bank Sta=713.2,797.7
XS Rating Curve= 0 ,0
Exp/Cntr(USF)=0,0
Exp/Cntr=0.3,0.1

Type RM Length L Ch R = 1 ,47818   ,473.7,500,513.9
XS GIS Cut Line= 6
1630932.91117978468340.6468585121630790.24812996468468.487901479
1630598.89844705 468544.045821221630348.24081188468668.474706233
1629948.54738556468830.4163114731629588.57632072 468991.74538514
#Sta/Elev= 30
       0  764.54   134.4  735.06   181.8   714.6   212.8  711.24   713.5  707.97
   738.3  696.01   749.2695.2249   763.1  694.31   834.7695.2428   847.9   704.7
   883.2  706.05   897.4  710.95   925.1  734.08   943.3  737.21   982.2  764.54
   999.8  781.11  1038.9  792.61  1074.5  812.77  1099.5     830  1128.8  859.87
  1149.6  875.23  1210.6  891.93  1271.7  925.14  1293.2  943.07  1336.4  971.37
  1361.6  981.43  1386.8 1001.67  1444.2 1022.34  1483.3  1043.3  1502.9 1046.08
#Mann= 4 ,-1,0
       0     .05       0   707.2      .1       0   749.2    .045       0
   834.7      .1       0
Bank Sta=749.2,834.7
XS Rating Curve= 0 ,0
Exp/Cntr(USF)=0,0
Exp/Cntr=0.3,0.1

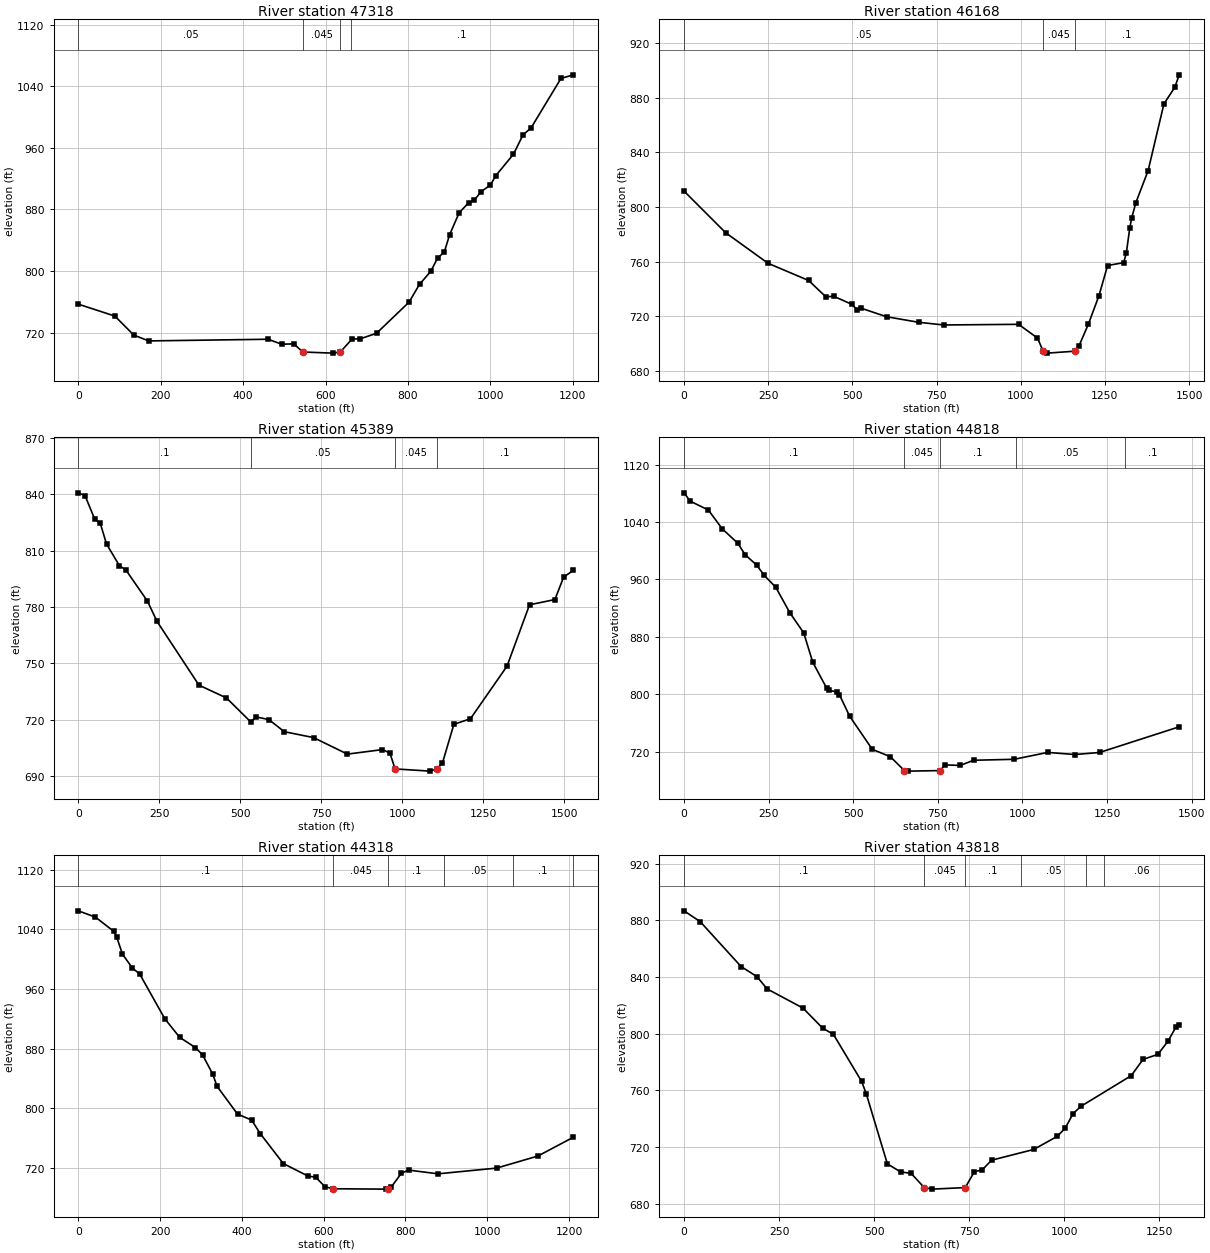
Type RM Length L Ch R = 1 ,47318   ,1119.7,1150.2,1169
XS GIS Cut Line= 6
1630796.56963964468270.5010927321630697.62889263468263.080831975
1630599.46701548468255.7179858091630502.86353414468248.472265393
1629892.07866646468202.6639580581629598.37256098468180.634802639
#Sta/Elev= 30
       0  756.86    88.7  741.39   134.7  716.67   170.9  709.11   460.5  711.27
   493.4  704.86     523  705.26   544.7694.7327     617  693.25   635.9694.7164
   664.4  711.63   684.2  711.85   723.7  719.02   802.6  759.44   828.1  782.69
   855.3  799.43   871.7  816.56   888.2  824.71   901.3  847.31   924.4  875.76
   947.4  888.55   960.5  891.52     977  902.79    1000  911.54  1013.2  923.84
    1056  951.56    1079  976.64  1098.7  985.77  1171.3 1050.06  1201.6 1054.74
#Mann= 4 ,-1,0
       0     .05       0   544.7    .045       0   635.9     .08       0
  660.78      .1       0
Bank Sta=544.7,635.9
XS Rating Curve= 0 ,0
Exp/Cntr(USF)=0,0
Exp/Cntr=0.3,0.1

Type RM Length L Ch R = 1 ,46168   ,784.3,778.5,772.9
XS GIS Cut Line= 2
1631614.79690154467863.4219801881630409.02610746467021.574734871
#Sta/Elev= 30
       0  811.65   123.5  781.15   249.6  758.68     370  746.08   421.5  734.06
   444.5  734.52   497.6  728.67   513.6  724.74   525.6  725.78   601.6  719.48
   696.6  715.42   771.1  713.44   993.7  713.92  1049.8  703.82  1066.6694.2571
  1078.9  692.79  1161.7694.2275  1173.2  698.17    1201  714.11  1232.1  734.71
    1258  757.06  1305.8  759.17  1313.8  766.56    1324  784.87  1329.9   792.2
  1341.9  803.14  1378.2  826.56  1425.3  875.63  1457.9  887.93  1470.6  896.94
#Mann= 3 ,-1,0
       0     .05       0  1066.6    .045       0  1161.7      .1       0
Bank Sta=1066.6,1161.7
XS Rating Curve= 0 ,0
Exp/Cntr(USF)=0,0
Exp/Cntr=0.3,0.1

Type RM Length L Ch R = 1 ,45389   ,648.2,571.3,473.7
XS GIS Cut Line= 6
 1632146.1277437467036.0911274591631697.41038537466968.247435908
1631539.61673771466848.0511539831631460.27798562466792.167407493
1631094.16782546466564.2288869871630769.72829695466691.625038291
#Sta/Elev= 30
       0  840.64    20.9  839.11    50.8   826.6    67.4   824.7    87.3  813.41
   127.1   801.9     147  799.64   213.4  783.14   243.2   772.3   372.6  738.47
   457.6  731.66   532.7  718.91   548.7   721.6   588.4  720.18   636.1  713.74
   726.4  710.61   830.9  701.83   939.1  704.22   962.2  702.46   978.2 693.965
  1086.2  692.79  1107.3693.9733  1124.3  696.98  1159.8  717.64  1211.1  720.64
  1323.9  748.54  1393.4  781.15  1471.9  783.94  1498.7  795.87  1529.1  799.48
#Mann= 4 ,-1,0
       0      .1       0  533.82     .05       0   978.2    .045       0
  1107.3      .1       0
Bank Sta=978.2,1107.3
XS Rating Curve= 0 ,0
Exp/Cntr(USF)=0,0
Exp/Cntr=0.3,0.1

Type RM Length L Ch R = 1 ,44818   ,503.1,500,488.9
XS GIS Cut Line= 6
1631691.49009389465558.1000214821631324.84384556466212.818856388
1631263.33642264 466267.788562731631140.12078981466327.707406148
1630836.90551697466443.4903110561630675.09875397466491.180832475
#Sta/Elev= 30
       0 1080.54    18.3  1068.9    71.9 1056.58   112.9 1030.42   158.7 1010.37
   180.9  994.17   214.8  979.73   237.3  965.41   271.2  948.93   312.5  913.59
   353.9  885.19   380.2  844.72   421.2  808.63   429.1   805.2   451.7  803.18
   459.2  799.24   489.3  769.36   556.4  723.12   609.5  712.94   651.2693.5479
   662.5  692.78   757.8693.5367   770.2  701.46   816.3  700.74   855.6  707.91
   975.5  709.27  1074.6  718.85  1154.8  715.91    1228  718.77  1463.2  754.51
#Mann= 5 ,-1,0
       0      .1       0   651.2    .045       0   757.8      .1       0
  979.89     .05       0 1304.48      .1       0
Bank Sta=651.2,757.8
XS Rating Curve= 0 ,0
Exp/Cntr(USF)=0,0
Exp/Cntr=0.3,0.1

Type RM Length L Ch R = 1 ,44318   ,502.9,500,498.5
XS GIS Cut Line= 6
1631118.26748705465381.068223313 1631085.3886158465475.163179472
1631051.71939181 465568.529790641631016.46814997 465660.44102414
1630792.66544797466233.9444703161630617.22518206466474.768463731
#Sta/Elev= 30
       0 1064.85      42 1056.36    87.2 1037.17    94.1 1029.47     108 1006.73
   132.5  987.99   149.9  980.34   211.5  920.17   247.9  895.23   286.6  881.39
   304.1  871.54   328.8   845.8   339.4  829.49   389.4  792.28   423.9  784.25
     445   766.1   501.4  725.94   561.2  709.33   580.8   707.5   603.6  694.74
   623.2692.1644   751.4  691.66   758.3692.1833   765.5  694.53   790.1  712.97
   807.8  717.17   879.8  712.19  1023.1  719.87  1124.1  736.08  1210.9  761.29
#Mann= 6 ,-1,0
       0      .1       0   623.2    .045       0   758.3      .1       0
  895.49     .05       0 1062.99      .1       0 1210.94     .06       0
Bank Sta=623.2,758.3
XS Rating Curve= 0 ,0
Exp/Cntr(USF)=0,0
Exp/Cntr=0.3,0.1

Type RM Length L Ch R = 1 ,43818   ,499.9,500,499
XS GIS Cut Line= 6
1630630.31898789465190.0978047251630420.95720188465805.870195225
1630364.62398122465971.555231303 1630306.2799378466143.157906473
1630275.09496081466234.8765550551630211.83907269466422.782346489
#Sta/Elev= 30
       0  886.67    42.6  879.02     150  847.39   191.6   840.3   218.7  831.58
   312.9  818.07   364.8  803.84   392.6  799.62     467  766.36   479.2  757.58
   534.6  708.25   569.3  702.59     597  701.57   631.5691.5323   652.5  690.44
   739.2691.5275   763.3  702.66   784.1  704.05   808.4  710.82   919.3   718.4
   981.7  727.73  1002.5  733.61  1022.9  743.69  1043.6  748.85  1175.7  770.45
  1206.8  781.92  1245.6  785.43  1272.6  794.81  1293.3  804.77  1301.8  806.12
#Mann= 6 ,-1,0
       0      .1       0   631.5    .045       0   739.2      .1       0
  885.39     .05       0 1056.64      .1       0 1103.52     .06       0
Bank Sta=631.5,739.2
XS Rating Curve= 0 ,0
Exp/Cntr(USF)=0,0
Exp/Cntr=0.3,0.1

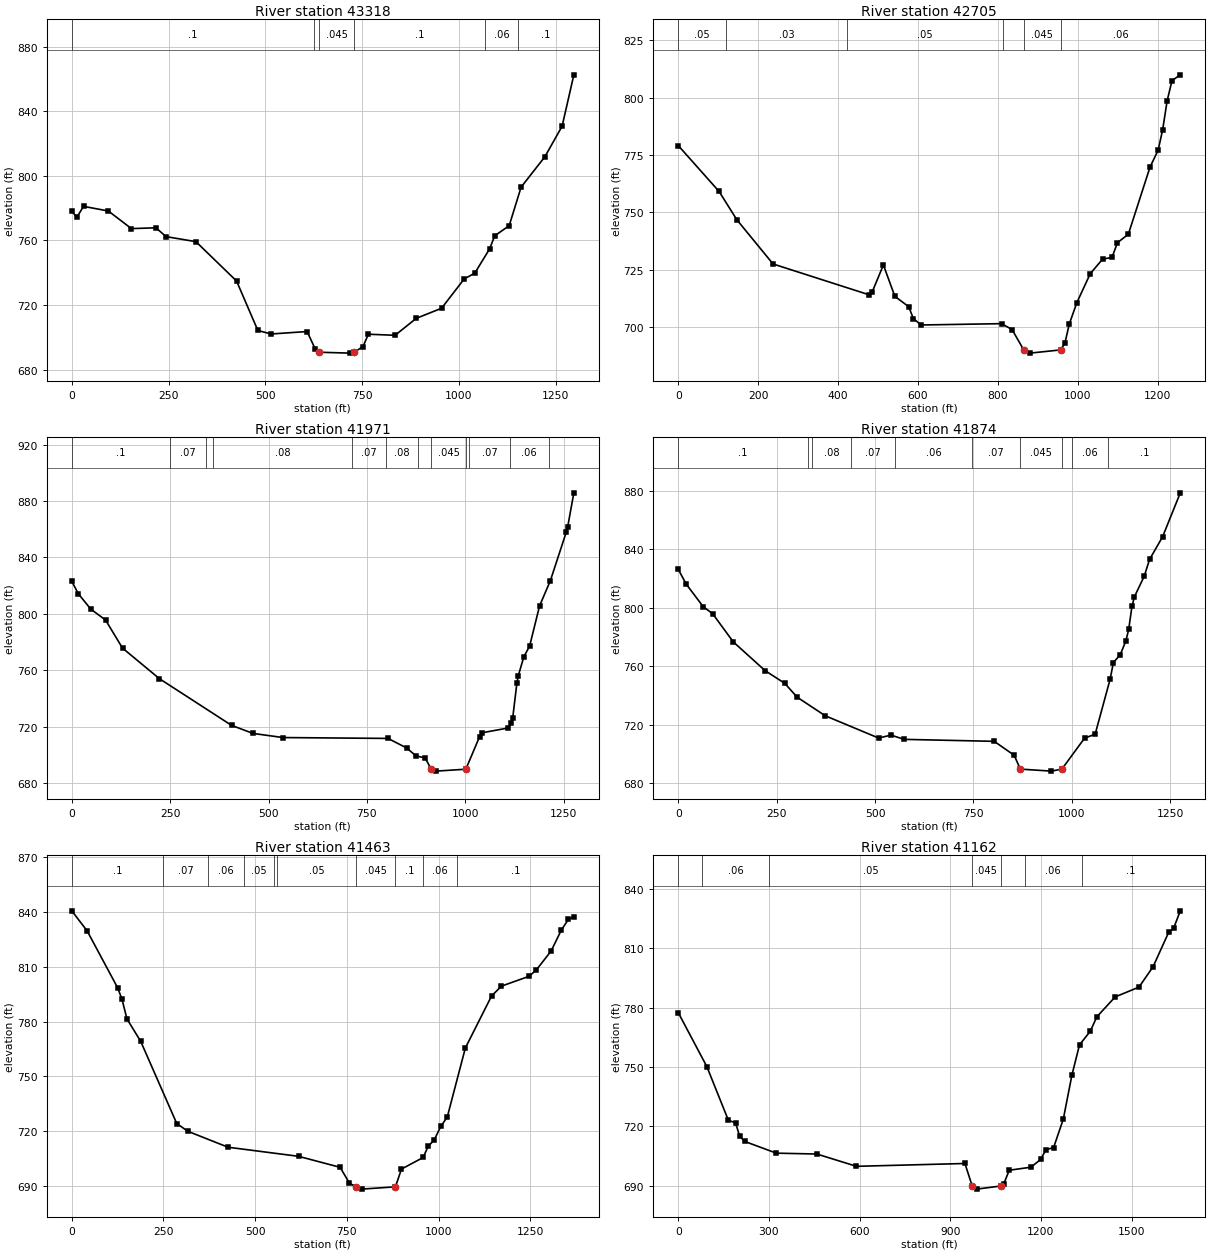
Type RM Length L Ch R = 1 ,43318   ,599.3,612.7,622.6
XS GIS Cut Line= 6
1630147.95906022465011.2146323171629975.72351231 465560.22206448
1629953.27375406465631.7832730561629846.63551588465971.698603719
1629819.46102956 466064.703667061629765.25693323466250.294529856
#Sta/Elev= 30
       0  778.09    13.1  774.24    30.3  781.06    94.4  778.19   154.1  767.27
   217.4  767.78   243.5  762.31   320.7  759.19   425.7   734.8   480.7  704.18
   515.1  702.02     608  703.53   628.3  692.95   639.3690.7065   719.2  690.16
   729.4690.6915   752.4  694.26   766.1  701.87   835.1   701.2   889.9  711.71
   955.2  717.95  1013.7  736.12    1041  739.68  1079.3  754.72  1092.5   762.8
  1129.9  769.11  1160.6  792.93  1222.2  811.83  1266.6  830.69  1296.9  862.51
#Mann= 6 ,-1,0
       0      .1       0  625.39     .05       0   639.3    .045       0
   729.4      .1       0 1066.64     .06       0 1153.53      .1       0
Bank Sta=639.3,729.4
XS Rating Curve= 0 ,0
Exp/Cntr(USF)=0,0
Exp/Cntr=0.3,0.1

Type RM Length L Ch R = 1 ,42705   ,693.6,734.8,764.7
XS GIS Cut Line= 3
1629927.35396049464777.9672003661629659.01515104465006.844420187
1629185.47607555 465776.34541786
#Sta/Elev= 30
       0  779.08   102.2   759.1   146.7  746.76   237.2  727.53   476.5  714.17
   485.6  715.49   513.3  727.11     542  713.43   576.7  708.93   588.2  703.79
   607.5  700.97   809.1  701.55   835.3  698.96   864.4690.1338   879.9  688.72
   957.2690.1329   967.6  693.15   978.4   701.4   997.4  710.71  1030.8  723.29
  1061.8  729.65  1085.2  730.37    1099   736.8  1126.2  740.49  1180.4   769.7
  1200.7  777.08  1212.1  786.03  1223.2  798.53  1235.4  807.35  1256.2  809.87
#Mann= 6 ,-1,0
       0     .05       0     120     .03       0  422.69     .05       0
  812.69      .1       0   864.4    .045       0   957.2     .06       0
Bank Sta=864.4,957.2
XS Rating Curve= 0 ,0
Exp/Cntr(USF)=0,0
Exp/Cntr=0.3,0.1

Type RM Length L Ch R = 1 ,41971   ,98.2,96.7,96.4
XS GIS Cut Line= 6
1629811.05308428464408.7416108621629320.36914004464709.200195551
1629288.47501316464767.6727614991629231.33136916464815.513951821
1628884.87222248464897.5374325331628699.32153745464980.163129358
#Sta/Elev= 30
       0  823.16    16.7  814.26    48.3  803.38    85.9  795.64   128.9  775.75
   222.7  754.06   406.1  720.94   460.5  715.24   536.8  712.31   803.6  711.69
   850.8  704.92   874.4  699.36     898  697.78   913.4689.8685   924.8   688.5
  1001.3689.8569  1036.3  713.03  1043.1  715.74  1109.4  719.11  1116.6  722.44
  1120.2  725.86  1130.9  750.72  1134.5  756.14  1148.8   769.7  1163.3  777.14
  1188.6  805.67    1216  823.55  1256.6  858.11  1260.2  861.94  1275.7  885.86
#Mann= 12 ,-1,0
       0      .1       0     250     .07       0     340     .03       0
     360     .08       0  711.97     .07       0  799.67     .08       0
  879.67     .06       0   913.4    .045       0  1001.3     .08       0
 1009.67     .07       0 1112.54     .06       0 1212.54      .1       0
Bank Sta=913.4,1001.3
XS Rating Curve= 0 ,0
Exp/Cntr(USF)=0,0
Exp/Cntr=0.3,0.1

Type RM Length L Ch R = 1 ,41874   ,401.5,410.9,416
XS GIS Cut Line= 6
1629764.47616246464320.9030779861629273.79221821464621.361662675
1629241.89809133464679.8342286231629184.75444734464727.675418944
1628838.29530065464809.6988996561628652.74461562464892.324596482
#Sta/Elev= 30
       0  826.47    20.2  816.33    63.4  800.92    87.3  796.12   139.9  776.79
   220.9  757.12   270.7  748.47     302  739.03   373.6  726.28   509.2  711.05
   540.6  713.07     574  710.16   802.9  708.81   853.5  699.31   869.2  689.82
   948.1  688.44   974.8689.8136  1032.5  711.02  1059.3  713.67  1097.4  751.33
  1105.6  762.61  1123.1  768.09  1137.4  777.48  1144.6  785.44  1152.8  801.03
    1159  807.58  1184.1  821.78  1197.5  833.15  1230.8  848.77  1275.7  878.74
#Mann= 10 ,-1,0
       0      .1       0     330     .07       0     340     .08       0
     440     .07       0     550     .06       0   746.5     .07       0
   869.2    .045       0   974.8     .05       0  999.67     .06       0
 1092.54      .1       0
Bank Sta=869.2,974.8
XS Rating Curve= 0 ,0
Exp/Cntr(USF)=0,0
Exp/Cntr=0.3,0.1

Type RM Length L Ch R = 1 ,41463   ,318.8,300.9,288.2
XS GIS Cut Line= 4
1629688.91275728464202.7999382261629100.91706502464357.090915196
1628711.17087881464397.6767182711628457.20261972464664.869655158
#Sta/Elev= 30
       0   840.6    41.8  829.66   125.1  798.46   136.8  792.28   150.4  781.46
   187.7  769.26   286.1  724.24   316.6  719.96     426  711.26   618.2  706.29
   731.3  700.27   756.7  691.66   773.5 689.595   789.7  688.34   882.1   689.6
   898.6  699.32   957.9  705.67   971.1  711.73   987.6  715.18    1006  722.76
  1023.3  727.71  1072.7  765.56  1144.1  793.99  1170.9  799.38  1246.1  804.76
    1266  808.23  1306.4   818.6  1334.2  830.04  1353.7  835.96  1368.4  837.24
#Mann= 10 ,-1,0
       0      .1       0     250     .07       0     370     .06       0
     470     .05       0     550     .06       0     560     .05       0
   773.5    .045       0   882.1      .1       0   957.9     .06       0
 1049.76      .1       0
Bank Sta=773.5,882.1
XS Rating Curve= 0 ,0
Exp/Cntr(USF)=0,0
Exp/Cntr=0.3,0.1

Type RM Length L Ch R = 1 ,41162   ,471.4,458.6,446.7
XS GIS Cut Line= 3
1629766.47572874463962.559820944 1629344.4087384 463853.48632906
1628220.47753943 464341.94587967
#Sta/Elev= 30
       0   777.5    94.8  750.15     166  723.03   189.7  721.77   203.2  714.99
   220.2  712.35   324.6  706.43   458.6     706   589.8  699.78   948.7  701.21
  972.79689.8118   987.1  688.25  1066.9  689.82  1077.4  690.98  1095.3   697.8
  1166.9  699.33  1199.1  703.23    1217  708.24    1242  709.21  1274.2  723.64
  1302.8  745.97  1327.9  761.22  1363.6   768.1  1385.1  775.34  1445.8  785.43
  1524.6  790.38  1571.1  800.64  1622.9  818.08  1639.1  820.08  1661.4  828.95
#Mann= 7 ,-1,0
       0     .05       0      80     .06       0     300     .05       0
  972.79    .045       0  1066.9      .1       0 1145.93     .06       0
 1335.93      .1       0
Bank Sta=972.79,1066.9
XS Rating Curve= 0 ,0
Exp/Cntr(USF)=0,0
Exp/Cntr=0.3,0.1