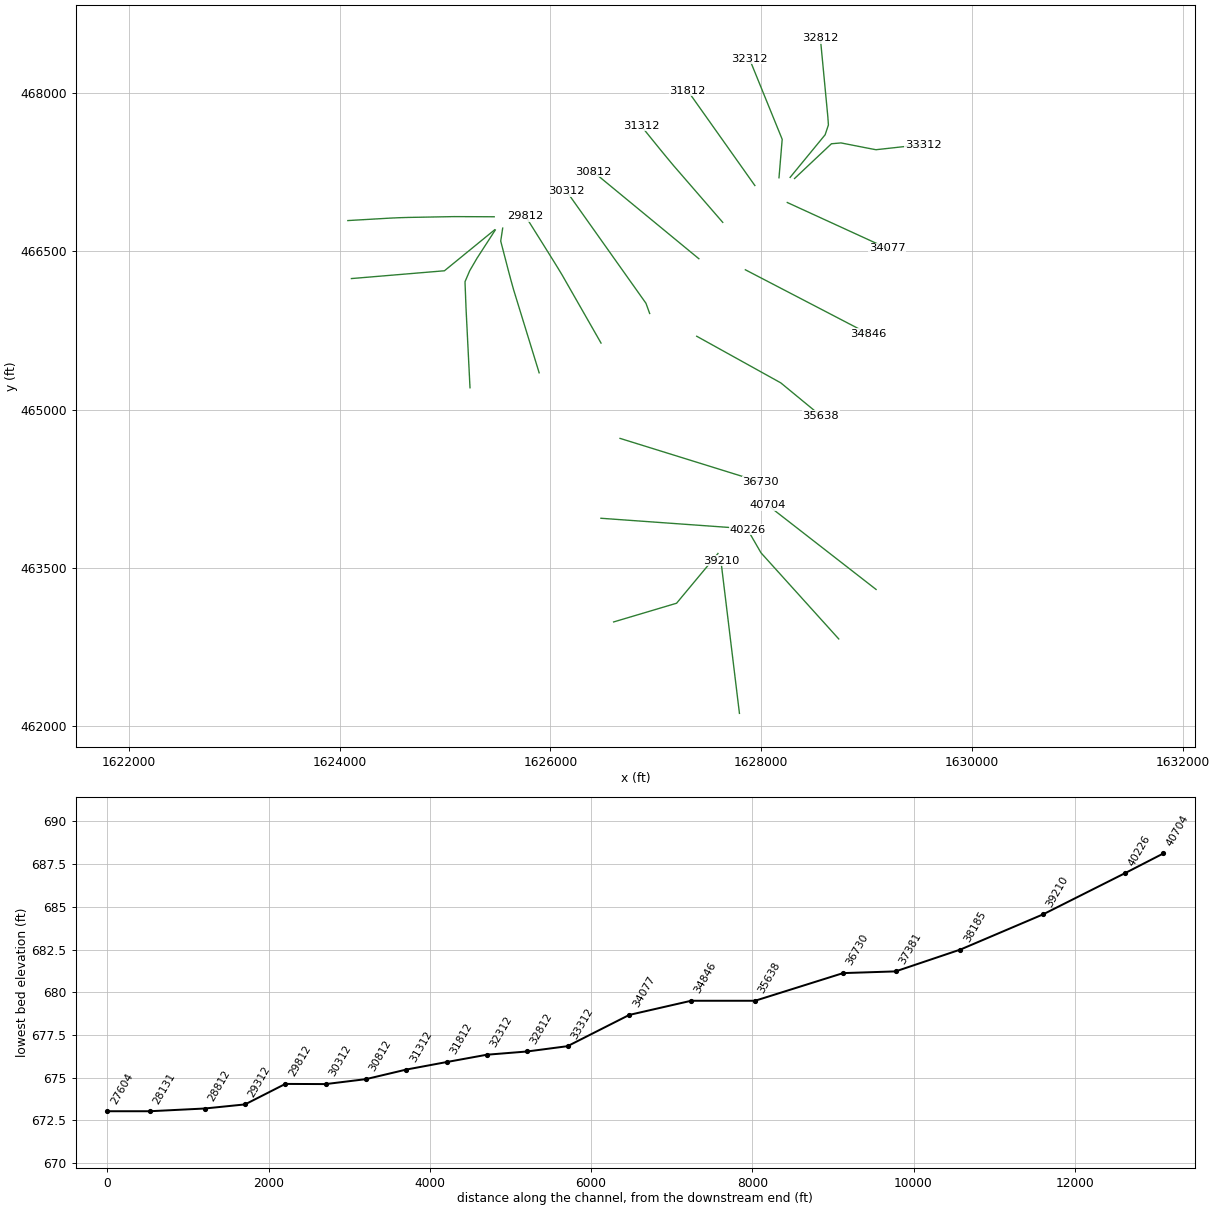
HEC-RAS study FshCrk.prj: FshCrk

--- FshCrk.g01 (geometry) --- (continued)

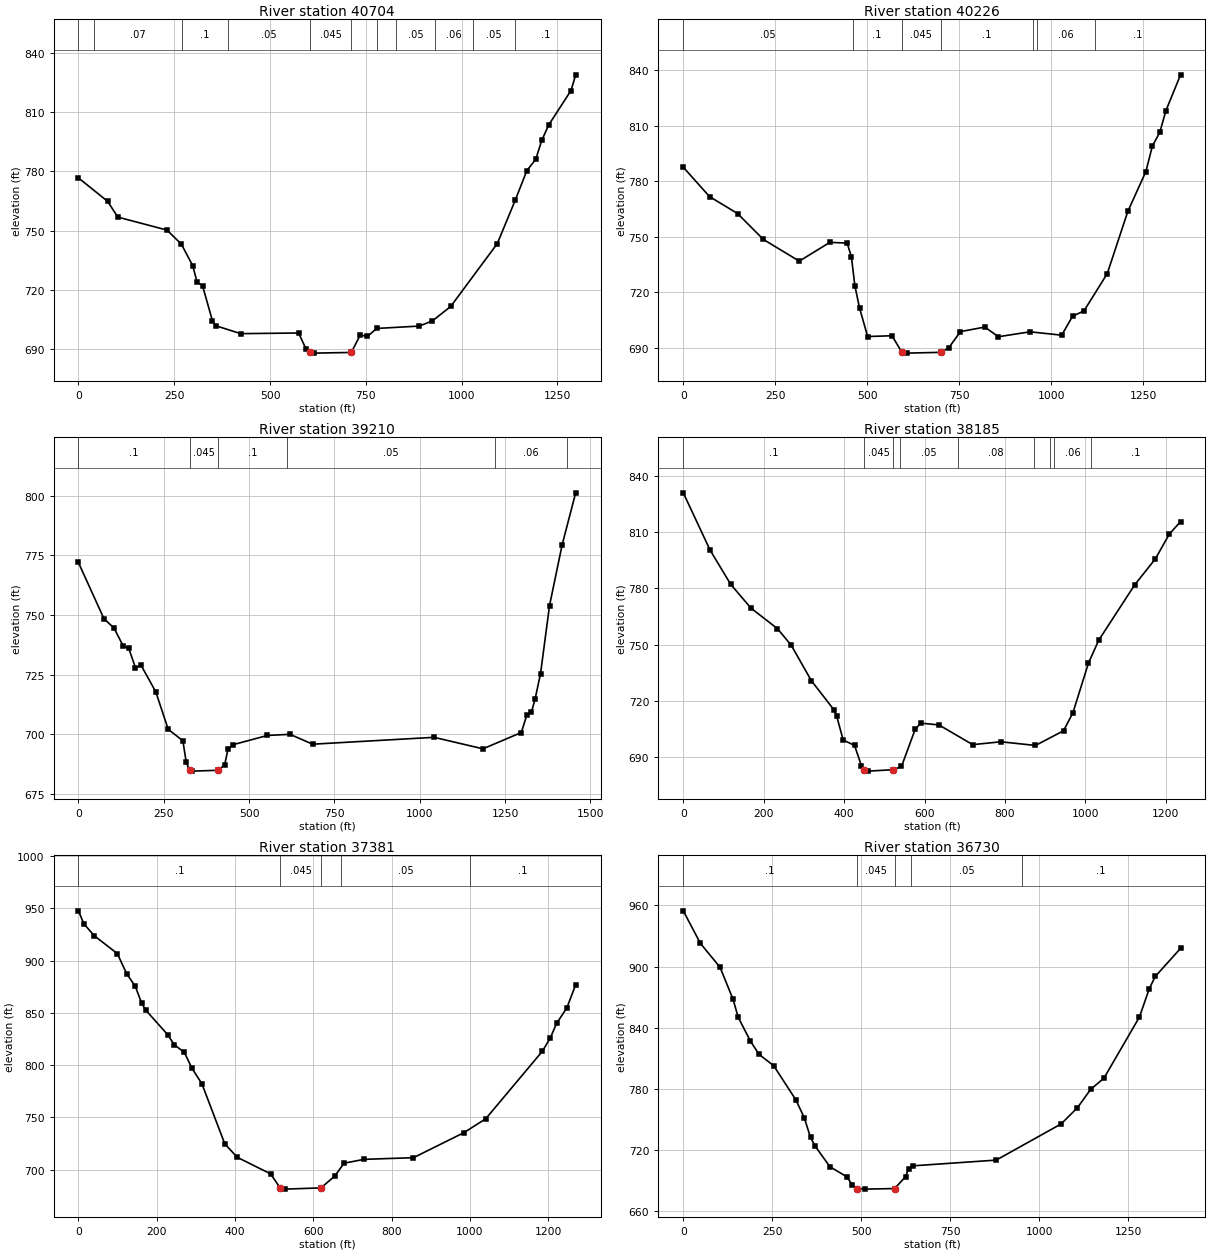
Type RM Length L Ch R = 1 ,40704   ,485.3,477.7,467
XS GIS Cut Line= 2
1629088.32314876463293.891892439 1628063.9807902464090.602615764
#Sta/Elev= 30
       0  776.75    76.2  764.89   102.9  756.91   231.2  750.34   268.6  743.27
   298.2   732.4   309.9  723.96   323.9  722.25   349.6  704.59     359  701.95
   423.5  697.98   574.7  698.31   594.5  689.99   604.2688.5468   613.8  688.13
   712.3688.4745   735.4  697.31   754.1  696.55   778.4  700.61   889.7  701.81
   923.9  704.45   971.5  711.71  1093.1  743.51    1140  765.45  1170.2  780.39
  1193.6  786.18  1209.1  795.67  1227.3   803.5  1285.5  820.92  1297.7  828.85
#Mann= 11 ,-1,0
       0     .06       0      40     .07       0     270      .1       0
     390     .05       0   604.2    .045       0   712.3      .1       0
     780     .06       0     830     .05       0     930     .06       0
    1030     .05       0    1140      .1       0
Bank Sta=604.2,712.3
XS Rating Curve= 0 ,0
Exp/Cntr(USF)=0,0
Exp/Cntr=0.3,0.1

Type RM Length L Ch R = 1 ,40226   ,1047.8,1015.4,1005.8
XS GIS Cut Line= 3
 1628734.3262084462824.3457903721627997.28522494463640.679413347
 1627871.2205819463858.540046713
#Sta/Elev= 30
       0  787.62    71.4   771.7   147.5  762.54   217.8  748.49   315.3  736.77
   398.4  746.94   445.4  746.53   456.9  739.15   466.3  723.53     479  711.42
   501.1  695.95   567.4  696.38   594.2  687.38     608  686.97   700.1   687.4
   721.5  689.82   753.1   698.6   819.4  701.09   856.6  695.85   942.5  698.51
  1028.5  696.68  1058.1  706.98  1088.9   709.8  1152.3  730.02  1208.1  763.65
  1257.3  785.29  1274.9  799.05  1295.3  806.63  1311.8   818.3  1351.5  837.63
#Mann= 7 ,-1,0
       0     .05       0     460      .1       0   594.2    .045       0
   700.1      .1       0     950     .05       0     960     .06       0
 1119.83      .1       0
Bank Sta=594.2,700.1
XS Rating Curve= 0 ,0
Exp/Cntr(USF)=0,0
Exp/Cntr=0.3,0.1

Type RM Length L Ch R = 1 ,39210   ,1094.7,1025.1,985.5
XS GIS Cut Line= 2
1627792.43873151462118.2634882391627616.79703765463564.380100975
#Sta/Elev= 30
       0  771.97    74.7  748.45   104.4  744.48   130.9  737.06   147.4  736.04
   167.2  727.82   183.7  728.85   226.6   717.8     263  702.09     306  697.28
   315.9  688.26   325.8  684.91   332.5  684.56  408.53684.9016   428.3  687.13
   438.2  693.74   451.4  695.57   553.9  699.51     620  699.97   686.1  695.84
  1041.8  698.72  1185.1   693.9  1297.5  700.74    1314  708.22  1327.2  709.34
  1337.6  714.65  1353.7  725.37  1380.1  753.92  1417.1  779.41  1456.7  801.14
#Mann= 6 ,-1,0
       0      .1       0   325.8    .045       0  408.53      .1       0
     610     .05       0    1220     .06       0    1430      .1       0
Bank Sta=325.8,408.53
XS Rating Curve= 0 ,0
Exp/Cntr(USF)=0,0
Exp/Cntr=0.3,0.1

Type RM Length L Ch R = 1 ,38185   ,821.2,804.3,792.6
XS GIS Cut Line= 3
1626599.04567341462985.511601648 1627195.9873723463163.019066987
1627588.80440898463634.792172756
#Sta/Elev= 30
       0  831.04    66.6  800.49     118  782.19   168.1  769.55   234.3  758.52
   268.6  749.66   318.5  730.78   374.7  715.21   381.5  711.89   397.6  699.11
     426  696.21   443.1  685.31     450  683.26   460.2   682.5     522 683.268
   542.7  684.99   576.6  704.74   590.2  708.12   635.7  707.17   719.8  696.64
   789.9  698.16   875.9  696.21   945.8  704.05   969.1  713.72  1007.6  740.13
  1033.2  752.37  1122.9     782    1174  795.78    1209  809.08  1236.7  815.67
#Mann= 9 ,-1,0
       0      .1       0     450    .045       0     522      .1       0
     540     .05       0  682.77     .08       0  872.77     .06       0
  912.77     .05       0  922.77     .06       0 1012.77      .1       0
Bank Sta=450,522
XS Rating Curve= 0 ,0
Exp/Cntr(USF)=0,0
Exp/Cntr=0.3,0.1

Type RM Length L Ch R = 1 ,37381   ,665,650.9,641
XS GIS Cut Line= 2
1626478.41102733463969.0046130691627745.12805427463878.242956934
#Sta/Elev= 30
       0  947.69    13.9  935.32    40.2  923.93    99.4  906.74     123  887.66
   145.5  875.26   161.5  859.29   171.8  852.67   227.7  829.24   244.8  819.49
   270.5  812.18   290.2  796.79   315.4  782.09   373.7  724.71   405.3  711.78
   490.9  695.81   515.2682.4227   526.9  681.22   619.6682.4086   655.3  693.96
   678.3  706.02   729.7  709.74   855.6  711.32     984  735.17  1040.2  748.55
  1184.9  813.22  1205.5   826.2  1221.1  839.82  1247.4  854.73    1270  876.85
#Mann= 5 ,-1,0
       0      .1       0   515.2    .045       0   619.6      .1       0
     670     .05       0    1000      .1       0
Bank Sta=515.2,619.6
XS Rating Curve= 0 ,0
Exp/Cntr(USF)=0,0
Exp/Cntr=0.3,0.1

Type RM Length L Ch R = 1 ,36730   ,1105.1,1092.4,1084
XS GIS Cut Line= 2
 1626659.9343396464726.667133855 1627993.7360689  464312.3204428
#Sta/Elev= 30
       0  954.74    48.1  922.74   103.2   899.3   139.9  867.63   154.3  850.03
   188.6  826.68   212.7  813.62   253.9   802.5   316.2   768.9   339.8  751.36
   357.4   731.9   370.5  723.34   411.9  703.15     460  693.09   473.8  685.64
   488.2681.6994   511.6  681.12   593.7681.6982   624.4  693.38   632.7  701.19
   645.5  704.03     879  709.66  1061.2   745.2  1107.1  761.15  1144.1  779.18
  1181.5  790.19  1281.1  850.25  1308.9  878.22  1325.8  890.26  1396.7  917.85
#Mann= 5 ,-1,0
       0      .1       0   488.2    .045       0   593.7     .08       0
     640     .05       0     950      .1       0
Bank Sta=488.2,593.7
XS Rating Curve= 0 ,0
Exp/Cntr(USF)=0,0
Exp/Cntr=0.3,0.1

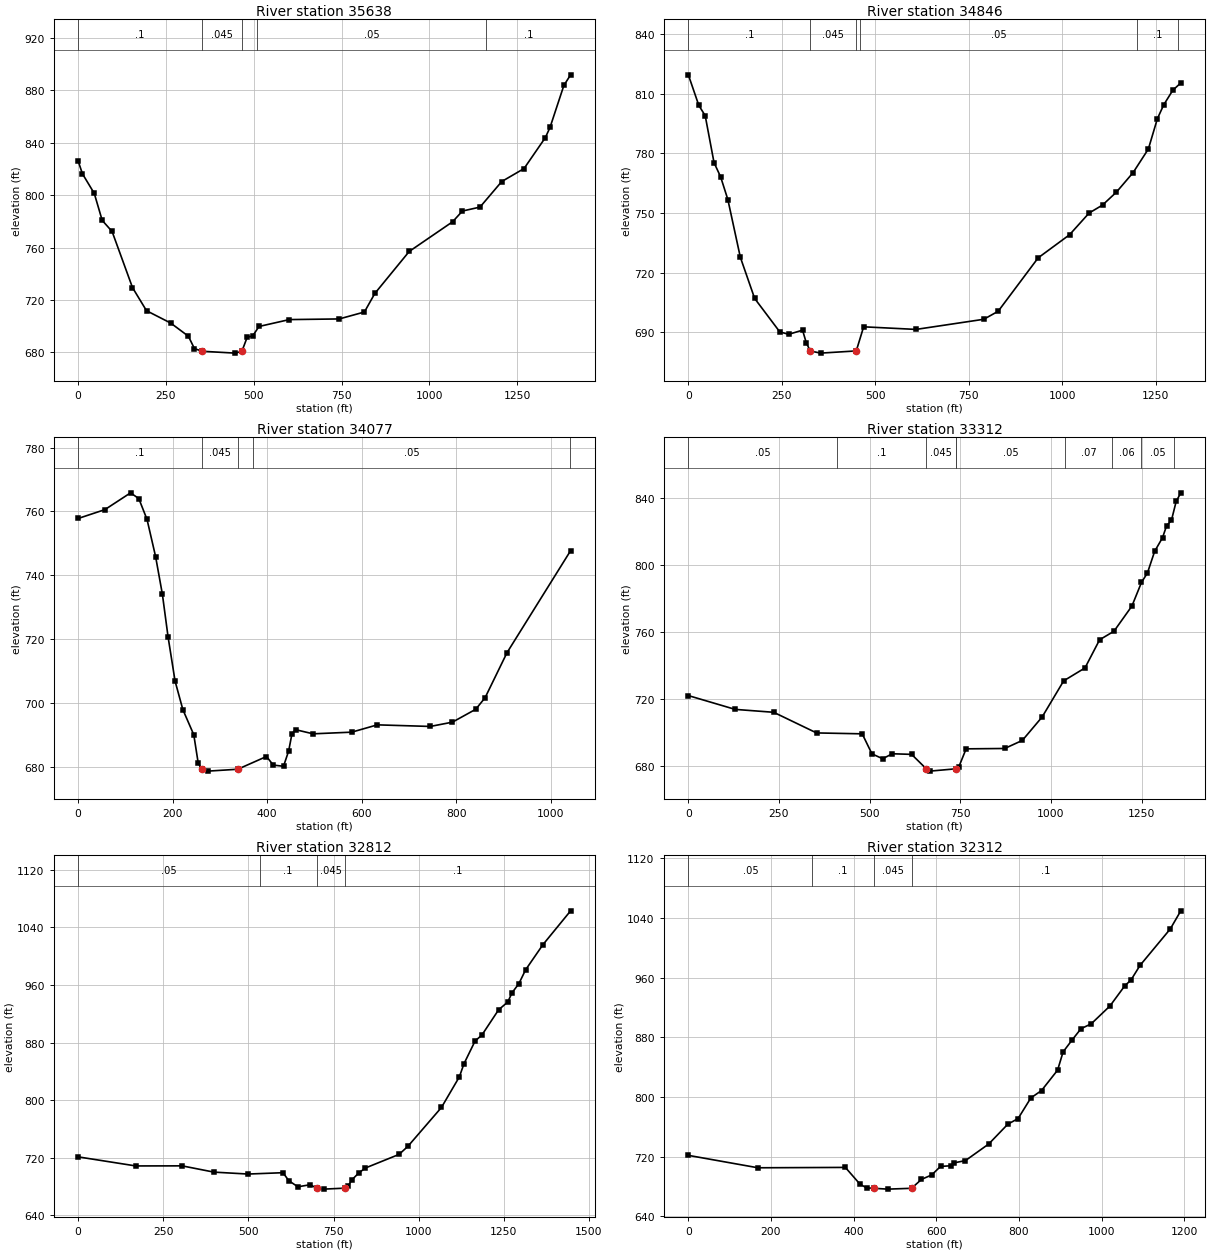
Type RM Length L Ch R = 1 ,35638   ,788.5,792.3,792.7
XS GIS Cut Line= 3
1627387.16390861465695.5260483611628184.28801902465253.556244569
1628563.11927942464941.809686537
#Sta/Elev= 30
       0  826.12    12.1  816.44    45.9  801.39    68.4  780.84    96.6  772.35
   154.7  729.52   194.6  711.88   263.5  702.45   313.8  692.41     331  682.97
   353.2680.9152   447.3   679.5   466.2680.8981   481.1  691.54   497.2  692.72
   514.8  699.84   601.1   705.1   743.3   705.6     815  710.89   844.7  725.07
   942.5   757.1  1066.1  779.77    1094  787.96  1144.1  790.97    1206  810.49
  1269.5  820.39    1330  843.96  1343.4  851.74    1383  883.92  1402.1  891.94
#Mann= 5 ,-1,0
       0      .1       0   353.2    .045       0   466.2     .08       0
     510     .05       0 1161.45      .1       0
Bank Sta=353.2,466.2
XS Rating Curve= 0 ,0
Exp/Cntr(USF)=0,0
Exp/Cntr=0.3,0.1

Type RM Length L Ch R = 1 ,34846   ,764.9,768.3,771.5
XS GIS Cut Line= 2
1627848.64183607466325.9978335631629016.70488895465718.289353349
#Sta/Elev= 30
       0  819.52      28  804.14    45.1  798.96    68.7  775.34    86.4  768.15
   105.7  756.73     139  727.76   177.3  707.01   244.5  690.19   268.4  688.97
   305.4  691.06   315.1  684.84   325.9680.5971   353.5   679.5     449  680.61
   468.7  692.74   608.7  691.43   789.9  696.53   828.4  700.56   935.4  727.45
  1019.2  739.05  1071.6  749.99  1107.4  753.99  1144.6  760.51  1189.3  770.35
    1230  782.21  1254.1  797.44  1271.1  804.44  1295.4  811.78  1316.7  815.44
#Mann= 6 ,-1,0
       0      .1       0   325.9    .045       0     449      .1       0
     460     .05       0    1200      .1       0    1310     .06       0
Bank Sta=325.9,449
XS Rating Curve= 0 ,0
Exp/Cntr(USF)=0,0
Exp/Cntr=0.3,0.1

Type RM Length L Ch R = 1 ,34077   ,754.9,765.5,774.5
XS GIS Cut Line= 2
1628246.29024249 466964.139265551629193.36839348466530.061779683
#Sta/Elev= 30
       0  757.78    56.5  760.55   110.9  765.81   128.3     764   145.7  757.47
   163.8  745.86   178.2  734.02   190.1  720.81     205  706.86   221.5  697.92
   244.6  690.06     254  681.15   261.8679.2625   274.3  678.67   337.6679.2606
   398.4  683.25   412.8  680.56   434.4  680.19   445.3  684.98   452.4  690.45
   459.9  691.65     497  690.35   578.7  690.87   632.9  693.16   744.8  692.66
   791.7     694     841  698.03   860.8  701.64   907.2  715.75  1041.8   747.7
#Mann= 5 ,-1,0
       0      .1       0   261.8    .045       0   337.6      .1       0
     370     .05       0    1040     .06       0
Bank Sta=261.8,337.6
XS Rating Curve= 0 ,0
Exp/Cntr(USF)=0,0
Exp/Cntr=0.3,0.1

Type RM Length L Ch R = 1 ,33312   ,416.3,500,568.2
XS GIS Cut Line= 6
1628314.98287763467191.6181091061628664.92823364467521.386449233
1628755.86637197467529.3139268161629001.19494955467481.211332724
1629087.14458081467464.8068379761629533.05956151467514.140673331
#Sta/Elev= 30
       0  722.01   129.2  713.75   235.4  712.02   353.6  699.68   479.6  699.14
   506.4  687.16   536.1  684.25   562.4  687.22   615.8  686.86   656.4678.2073
   665.9  676.84     737678.2071   746.2  679.45   766.2  690.16   872.6  690.38
   921.3  695.21   975.9  709.23  1035.3  730.82    1094  738.53  1134.4  755.38
    1174  760.48  1223.5  775.55  1249.9  789.68  1266.4  795.37  1286.2  808.26
    1308  816.44  1319.2  823.61  1332.4  826.69  1345.6  838.12  1358.3  843.23
#Mann= 9 ,-1,0
       0     .05       0     410      .1       0   656.4    .045       0
     737      .1       0  737.12     .05       0 1039.63     .07       0
 1169.63     .06       0 1249.63     .05       0 1339.63      .1       0
Bank Sta=656.4,737
XS Rating Curve= 0 ,0
Exp/Cntr(USF)=0,0
Exp/Cntr=0.3,0.1

Type RM Length L Ch R = 1 ,32812   ,486.4,500,511.2
XS GIS Cut Line= 6
1628273.25207208467202.5959964081628605.14324822467606.480111063
1628636.29640114467699.5019066481628631.14582089467774.350510225
1628569.44482881468422.2002643941628560.00095005468521.361155316
#Sta/Elev= 30
       0  721.34   169.3  708.74   305.2  708.86   398.7  700.15   498.9  697.48
   601.5  699.35   618.8  688.19   645.3  679.75   681.4  682.66   700.7677.8787
   720.9  676.53   782.8677.8737   793.4  680.97   803.3  689.17   823.8   698.8
   842.9  705.75   942.4  724.77   968.3  735.92    1067  790.03  1119.7  832.64
  1132.9  850.52  1165.8  882.39  1185.6  890.49    1235  925.79  1261.4  936.31
  1274.6  949.52  1294.4  962.06  1314.1  981.21  1364.9 1016.12  1446.3 1063.16
#Mann= 4 ,-1,0
       0     .05       0  532.76      .1       0   700.7    .045       0
   782.8      .1       0
Bank Sta=700.7,782.8
XS Rating Curve= 0 ,0
Exp/Cntr(USF)=0,0
Exp/Cntr=0.3,0.1

Type RM Length L Ch R = 1 ,32312   ,486.9,500,511.3
XS GIS Cut Line= 6
1628167.57853466467198.417991272 1628197.9121073467563.606509149
1628169.64182264467633.0745460541628103.67738764467795.166085392
1628035.35764238467963.0469832271627886.79002614468328.114822641
#Sta/Elev= 30
       0   721.6   168.4  704.96     380  705.45   415.4     683   431.2  678.05
   448.9677.4332   482.7  676.34   540.2  677.45   564.2  689.39     589  695.38
   610.3  706.77   635.1  707.66   642.6  711.51   670.5  714.56   727.1   736.9
   773.2  763.42     798  770.92   828.9  798.58   854.7   808.5   893.6  835.83
     907  860.35   929.6  876.92   950.3  891.42     975  897.94  1020.3  921.83
  1056.6  949.18    1071  956.48  1093.3   976.4  1166.4 1025.17  1191.8 1049.44
#Mann= 4 ,-1,0
       0     .05       0     300      .1       0   448.9    .045       0
   540.2      .1       0
Bank Sta=448.9,540.2
XS Rating Curve= 0 ,0
Exp/Cntr(USF)=0,0
Exp/Cntr=0.3,0.1

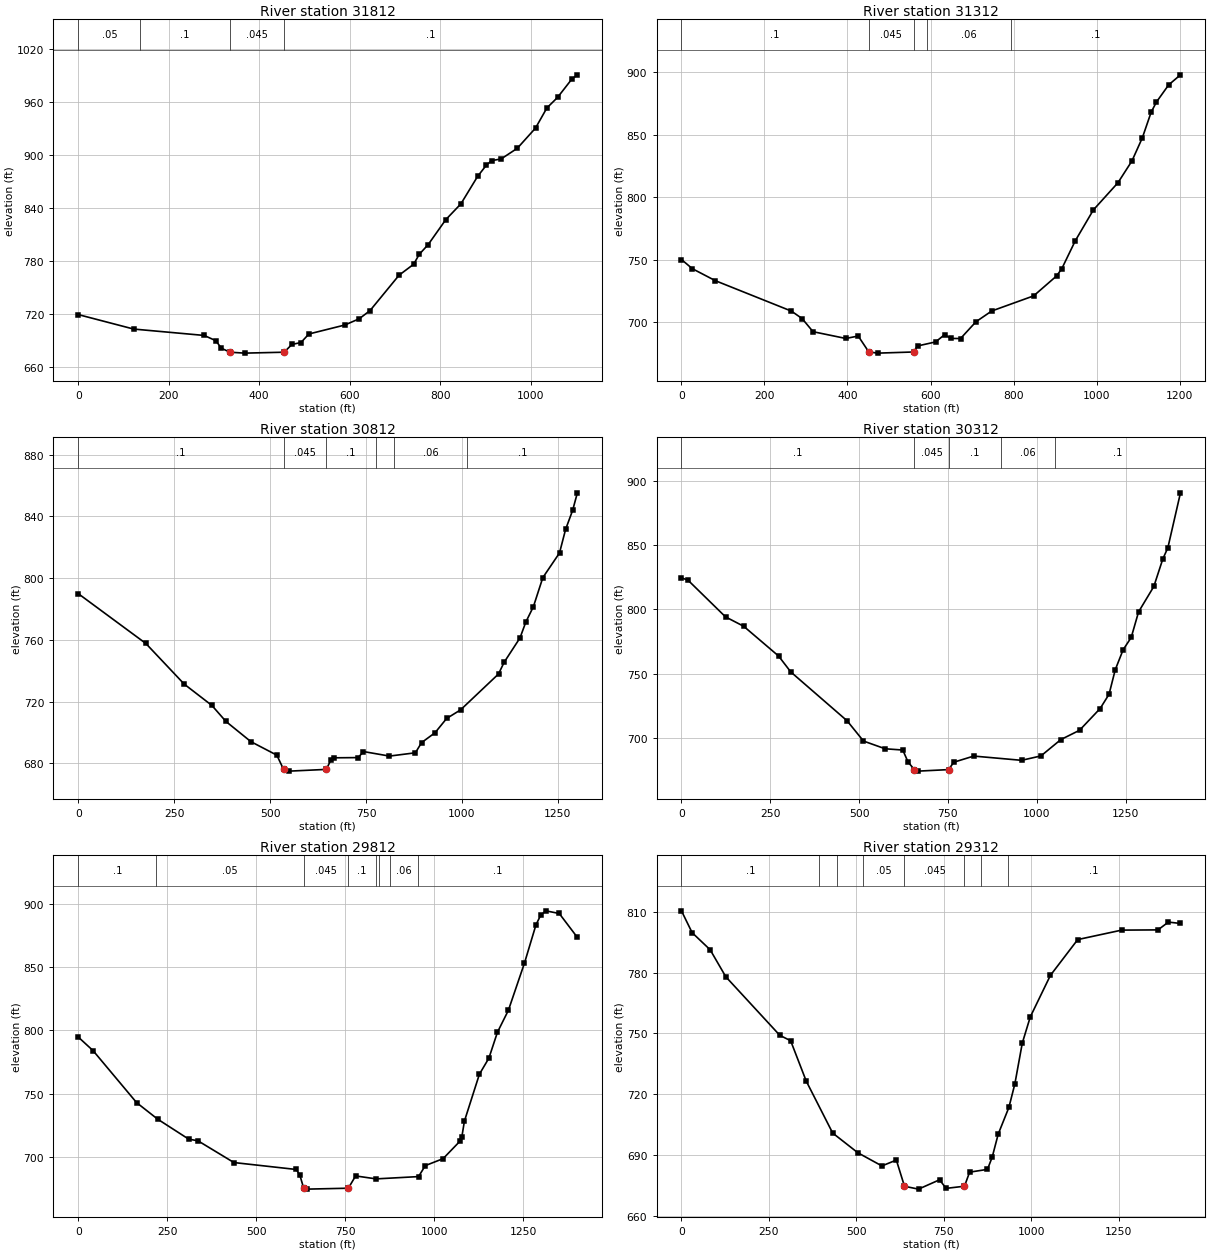
Type RM Length L Ch R = 1 ,31812   ,494.8,500,505.3
XS GIS Cut Line= 6
1627938.56354463467125.2957059741627828.37905373467280.850512981
1627676.65002647 467495.057433651627633.29873522467556.259082899
1627472.53822997 467783.216306151627300.71377046468025.792592645
#Sta/Elev= 30
       0  719.42   122.3   703.1   278.3  695.89   304.2  689.89     316  681.51
   335.2676.9385   367.7  675.91   455.1 676.945   472.1   685.7   492.2  687.87
   509.8  697.54     589  707.65   620.9  714.67     645  723.98   709.3  764.02
   741.5  776.35   753.7  787.45   773.7  798.63   812.5  826.72     846  844.61
   883.1  875.77   902.3  888.29   913.7   893.4   934.9  895.31   970.7  907.37
  1010.9  930.16  1036.1  952.94  1059.7  964.84  1091.3  985.56  1103.5  990.35
#Mann= 4 ,-1,0
       0     .05       0  136.87      .1       0   335.2    .045       0
   455.1      .1       0
Bank Sta=335.2,455.1
XS Rating Curve= 0 ,0
Exp/Cntr(USF)=0,0
Exp/Cntr=0.3,0.1

Type RM Length L Ch R = 1 ,31312   ,489.2,500,507.7
XS GIS Cut Line= 6
1627634.17635813466775.6077570621627166.56147972467315.256940231
1627106.51960506467387.2800901381627045.08665705467462.232039973
1626982.95751622467538.6488818971626857.82948564467693.312942639
#Sta/Elev= 30
       0  750.27    26.1  742.96    81.6  733.36   264.9  709.04   290.8  703.05
     317  692.59     396  687.18   425.8  689.14   451.4  676.38   473.3  675.47
   559.1676.3833   568.8  681.19   612.2  684.42   633.9  690.19     649  687.21
   672.3  687.12   709.5  700.53   747.4  709.12   848.5  721.22   903.6   737.1
   916.3  742.93   948.9   765.3   992.4   789.9  1051.5  811.58  1085.3  829.03
  1110.4  847.53  1131.5  867.93  1144.4  876.15  1173.9  889.84  1202.2  897.83
#Mann= 5 ,-1,0
       0      .1       0   451.4    .045       0   559.1      .1       0
  591.56     .06       0  794.06      .1       0
Bank Sta=451.4,559.1
XS Rating Curve= 0 ,0
Exp/Cntr(USF)=0,0
Exp/Cntr=0.3,0.1

Type RM Length L Ch R = 1 ,30812   ,516.7,500,487.6
XS GIS Cut Line= 6
1627407.47503988 466430.842370481627254.89758913466556.493693978
 1627107.7489333466677.6755382271626632.52908322467069.032695144
1626556.54203047 467131.609669731626403.06038205 467258.00607048
#Sta/Elev= 30
       0  789.88     176  757.63     276   731.3   348.3  717.45   384.7  707.13
   449.9  694.01   517.5  685.26     535676.0636   550.2  674.91   646.5676.0313
   658.5  682.16   666.7  683.54   729.6  683.68   743.5  687.59   811.2  684.66
   878.8  686.79   895.1  693.42   930.1   699.8   960.3  709.04   996.6   714.6
  1095.6  737.88  1110.1   745.4  1151.6  761.26  1166.9   771.6  1186.5  781.47
  1211.1  800.32  1254.6   816.3  1270.4  831.51    1289  844.04  1301.2  855.27
#Mann= 6 ,-1,0
       0      .1       0     535    .045       0   646.5      .1       0
  775.78     .05       0  823.28     .06       0 1013.91      .1       0
Bank Sta=535,646.5
XS Rating Curve= 0 ,0
Exp/Cntr(USF)=0,0
Exp/Cntr=0.3,0.1

Type RM Length L Ch R = 1 ,30312   ,504.9,500,494.8
XS GIS Cut Line= 6
1626940.95956872465911.3903253971626905.57151614466008.407519817
1626680.97911756466325.1417944731626485.75936364 466600.45161131
1626267.94582289  466907.62652191626152.93883505467069.818126649
#Sta/Elev= 30
       0  824.56    18.4  822.72     124  794.26   175.1  786.98   273.2  763.93
   307.8  751.52   466.1  713.68   512.3  697.95   573.3  691.95   622.9  690.98
   637.6  681.77   655.5675.7833   665.8  674.62   751.8675.7975   766.3  681.52
   822.6   686.3   957.1     683  1011.7   686.4  1067.7  699.08  1120.3  706.29
  1178.3  723.16  1203.4  734.23  1220.8  753.21  1243.1  768.81  1265.8   778.3
  1286.5  798.14  1329.4  817.82  1354.8  839.24  1368.9  847.83  1404.4  890.47
#Mann= 5 ,-1,0
       0      .1       0   655.5    .045       0   751.8      .1       0
  899.05     .06       0  1050.3      .1       0
Bank Sta=655.5,751.8
XS Rating Curve= 0 ,0
Exp/Cntr(USF)=0,0
Exp/Cntr=0.3,0.1

Type RM Length L Ch R = 1 ,29812   ,513.2,500,479.8
XS GIS Cut Line= 6
1626479.38470447465630.909259066 1626107.0855803466282.430265725
1626068.09582889466346.5315154791626021.98765339466420.962140888
1625920.87433855466582.7357674841625762.75457606466834.757573143
#Sta/Elev= 30
       0  794.69    41.3  784.04   163.5  742.98   222.7   729.9   309.6  714.16
     336  712.79   436.8  695.63   611.9  690.15     622  685.66   632.7675.3542
   641.8  674.63   758.1675.3545   778.6  685.06   836.1  682.72   955.3  684.53
   974.3  693.21  1024.3  698.71  1071.8  712.57  1076.7  715.61  1084.1  728.36
  1126.2  765.43  1152.9  778.15  1176.8  798.56  1207.6  815.93  1252.8  853.27
    1285   883.4    1298  890.89  1312.6  894.49  1350.4  892.39  1401.3  873.49
#Mann= 8 ,-1,0
       0      .1       0  218.83     .05       0   632.7    .045       0
   758.1      .1       0  835.42     .06       0  845.42      .1       0
  875.42     .06       0  952.97      .1       0
Bank Sta=632.7,758.1
XS Rating Curve= 0 ,0
Exp/Cntr(USF)=0,0
Exp/Cntr=0.3,0.1

Type RM Length L Ch R = 1 ,29312   ,513.2,500,488
XS GIS Cut Line= 6
1625892.57485448465348.8514242321625649.88045797 466137.75503014
1625626.39526872466222.0770399721625602.17484473466312.712357387
1625527.95058373466598.0323248061625546.78781639466721.186934143
#Sta/Elev= 30
       0  810.34    30.5  799.59      82  791.19   126.7  777.91   281.1  749.09
     312  746.44   356.6  726.57   432.2  701.01   504.2  691.31   572.9  684.84
   614.1  687.73   637.4674.8335   677.5  673.43   737.7  678.03   756.2   673.8
   808.8  674.86   823.5  681.78   874.6  683.15   888.2  689.25   905.2  700.47
   935.8  713.65   952.8  725.19     974  745.24   996.9  758.16  1054.4  778.59
  1132.5   796.2    1258  800.85  1361.8  800.96  1391.6   804.8  1426.1  804.13
#Mann= 8 ,-1,0
       0      .1       0  394.14     .05       0  444.14      .1       0
  517.89     .05       0   637.4    .045       0   808.8      .1       0
  855.39     .06       0  932.92      .1       0
Bank Sta=637.4,808.8
XS Rating Curve= 0 ,0
Exp/Cntr(USF)=0,0
Exp/Cntr=0.3,0.1

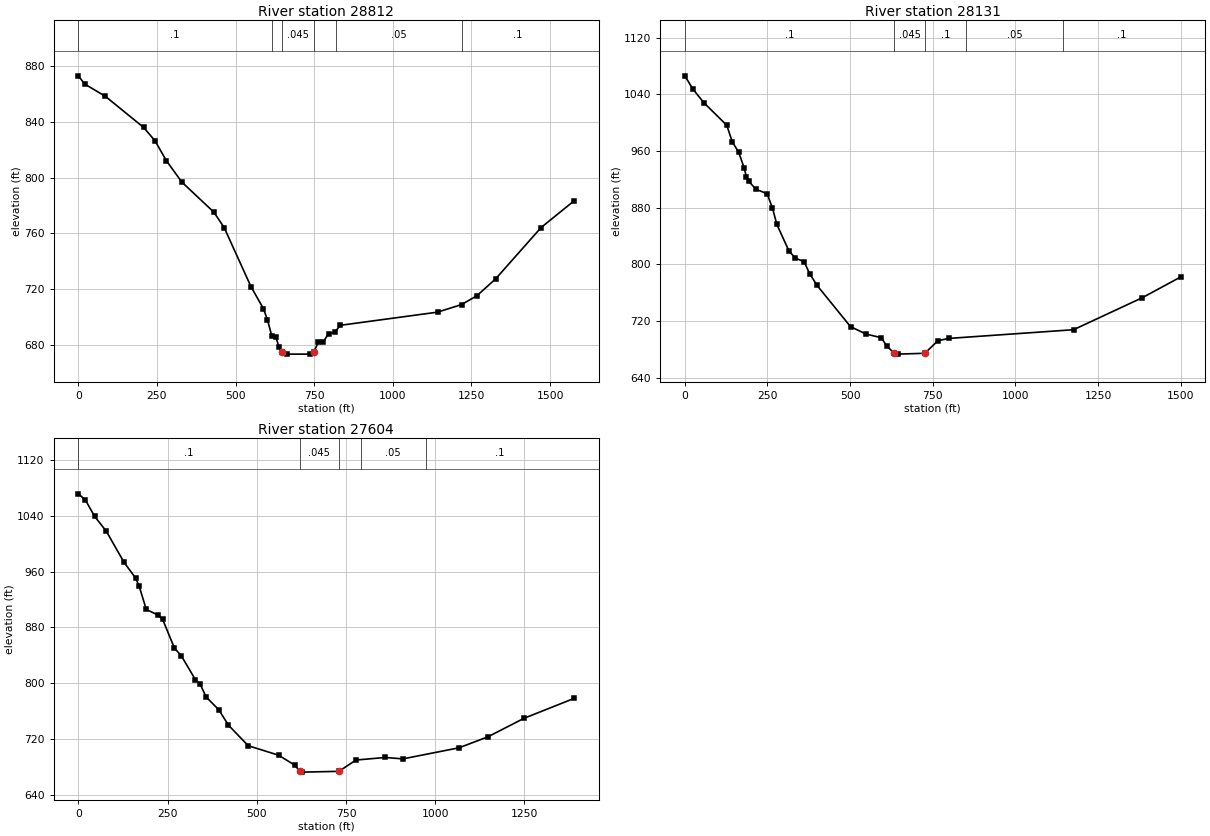
Type RM Length L Ch R = 1 ,28812   ,751.2,680.7,602.2
XS GIS Cut Line= 6
 1625236.6562188465206.834647894 1625199.1818843465956.288857639
1625189.24916139466212.3624924721625233.68115914466316.645420387
1625303.82570389466436.7678835541625476.26696005466703.100356147
#Sta/Elev= 30
       0  873.24    20.3  867.34      86  858.49   207.6  836.15   243.7  826.58
   279.8  812.28   329.1  796.84   430.9  775.24   463.8  764.09   548.9   721.7
   588.6  705.84   601.4  697.73   614.9  686.42     628  685.33   637.9  678.47
   647.4674.6685   664.2  673.19   736.4  673.19   748.5674.6767   762.7  681.62
   779.1  682.03   795.5  687.98   815.3  688.81   832.7   693.9  1142.5  703.38
  1218.5  708.84  1267.5   715.2  1326.7  727.28  1471.3   764.2  1576.4  783.41
#Mann= 6 ,-1,0
       0      .1       0  615.39    .025       0   647.4    .045       0
   748.5      .1       0  820.39     .05       0 1220.02      .1       0
Bank Sta=647.4,748.5
XS Rating Curve= 0 ,0
Exp/Cntr(USF)=0,0
Exp/Cntr=0.3,0.1

Type RM Length L Ch R = 1 ,28131   ,530.4,527.2,523.5
XS GIS Cut Line= 3
 1624111.8871761466242.6280465781624994.27058522466316.568574566
1625470.27320564466705.083947971
#Sta/Elev= 30
       0 1066.01    24.9 1047.02    57.8    1028     127  996.15   143.4   973.1
   163.2  957.81   179.6  935.95   186.2  923.58   192.8  917.27   215.8  905.66
   248.8  899.64   265.2  879.36   278.4  856.28   314.6  819.14   334.2  808.51
   360.7  803.72   377.6  786.72   400.2  769.98   501.3  711.87   548.4  701.29
   594.5  696.24   610.9   684.4     634  674.26   643.8  673.03   726.2  674.22
   765.7  691.98   798.6  695.21  1175.9   707.5  1383.5   752.6  1499.9  781.94
#Mann= 5 ,-1,0
       0      .1       0     634    .045       0   726.2      .1       0
     850     .05       0 1145.48      .1       0
Bank Sta=634,726.2
XS Rating Curve= 0 ,0
Exp/Cntr(USF)=0,0
Exp/Cntr=0.3,0.1

Type RM Length L Ch R = 1 ,27604   ,341.8,333.9,333.6
XS GIS Cut Line= 6
 1624077.8986406466792.8214203091624471.69017584466815.617306468
1624565.37666825466819.9548962231624652.84466917466822.513946217
1625084.02359685  466830.3528413 1625466.3518029466828.832406205
#Sta/Elev= 30
       0 1071.16    19.5 1062.56    45.8 1038.83    78.6 1017.48   127.9   973.3
   160.8  950.36   170.6  938.77   190.4  905.74   223.2  897.75   236.4  891.39
   269.2  850.51     289  839.08   328.1  805.23   341.5  798.88     358  780.61
   394.1  761.92   420.4   740.3   476.2  710.76   561.1  697.26   607.5  682.67
   620.1 674.176   627.2  673.03   730.1674.1627   778.1  690.32   860.2  694.01
   909.4  691.97  1066.9  707.86  1147.3  723.47  1248.5  749.96  1389.3  778.56
#Mann= 5 ,-1,0
       0      .1       0   620.1    .045       0   730.1      .1       0
  790.74     .05       0  973.24      .1       0
Bank Sta=620.1,730.1
XS Rating Curve= 0 ,0
Exp/Cntr(USF)=0,0
Exp/Cntr=0.3,0.1