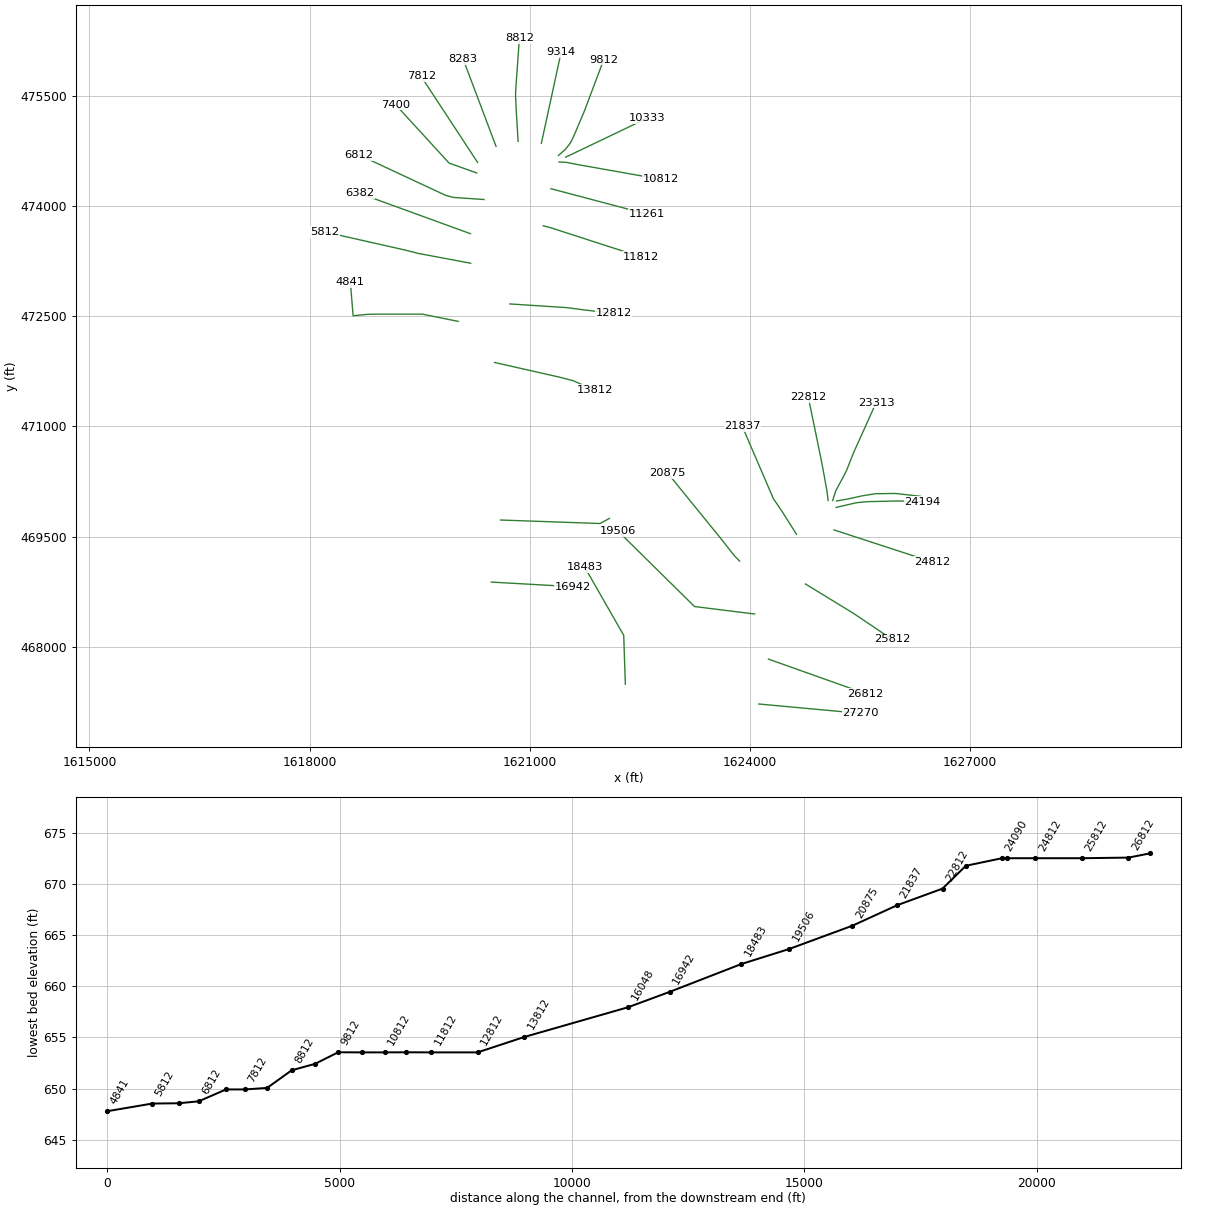
HEC-RAS study FshCrk.prj: FshCrk

--- FshCrk.g01 (geometry) --- (continued)

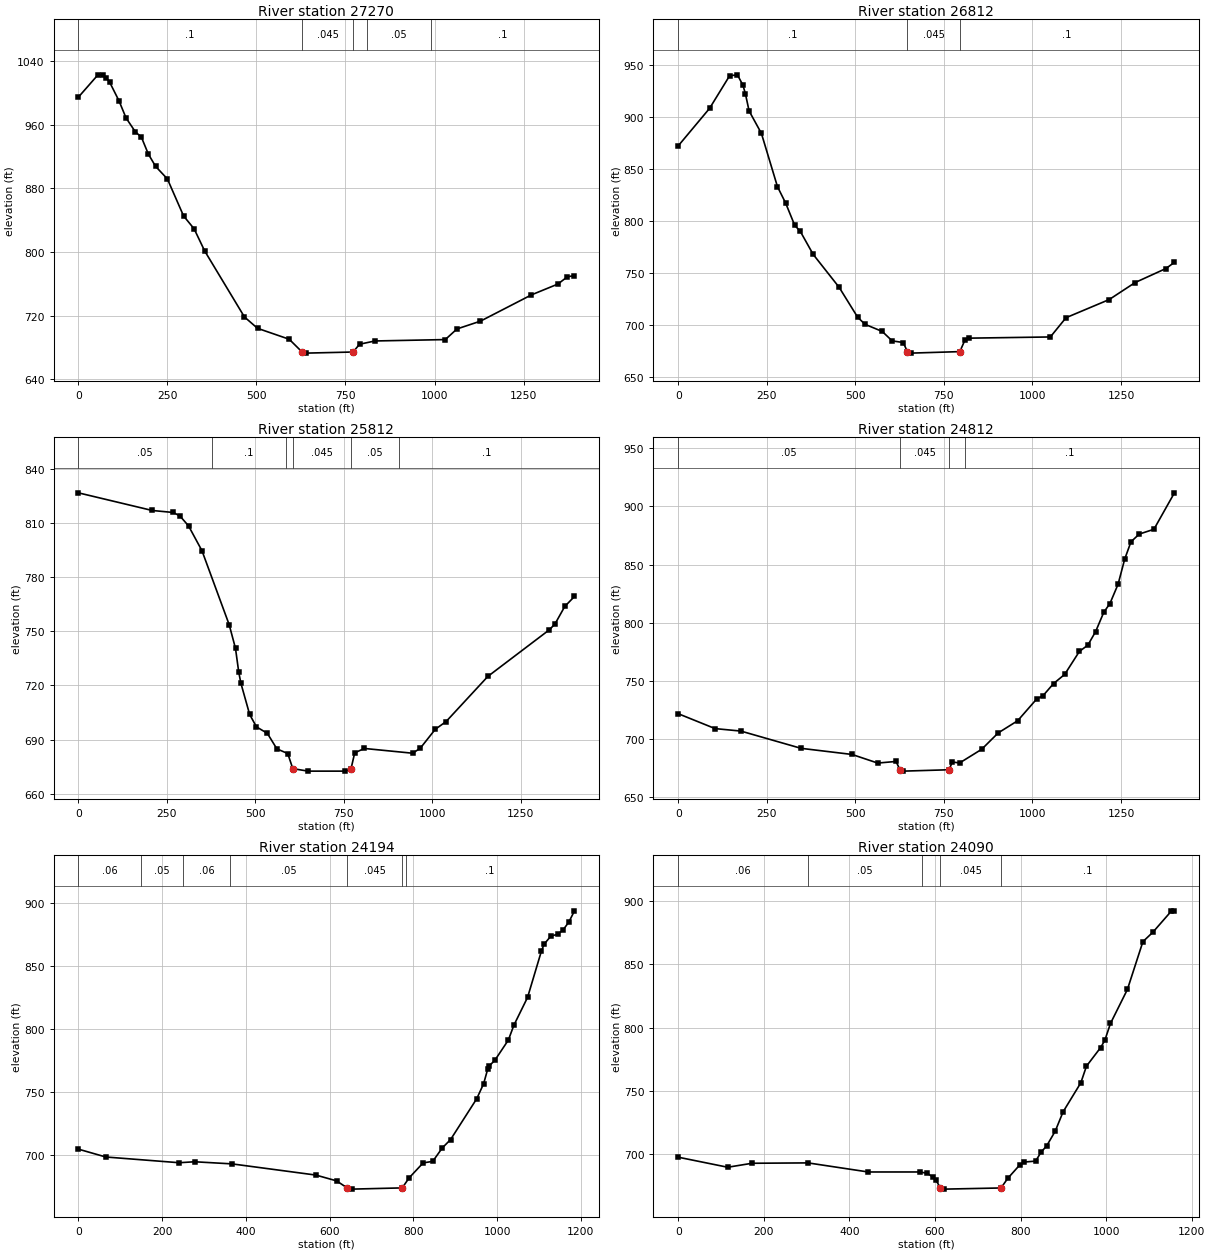
Type RM Length L Ch R = 1 ,27270   ,468.5,458.2,432
XS GIS Cut Line= 2
 1624118.0921432467219.1961474351625505.24410793467091.325074221
#Sta/Elev= 30
       0  994.33    54.9 1022.33      69 1022.43      78 1018.97    87.9 1013.17
   114.2   989.7     134  968.22   160.3  950.69   176.8  944.35   196.6  922.86
   216.8  907.52     250   891.7   295.4  845.27   325.1     829   354.7  801.27
   466.3  718.42     503  704.13     592  690.42   628.2  674.38   638.1  672.97
  771.27674.3661   789.6  684.16   832.8  688.24  1030.2  689.98  1063.1  703.34
    1129  713.13    1272  746.09  1346.4  759.71  1372.8  768.75    1393  770.43
#Mann= 5 ,-1,0
       0      .1       0   628.2    .045       0  771.27      .1       0
     810     .05       0     990      .1       0
Bank Sta=628.2,771.27
XS Rating Curve= 0 ,0
Exp/Cntr(USF)=0,0
Exp/Cntr=0.3,0.1

Type RM Length L Ch R = 1 ,26812   ,1015,1000,981.4
XS GIS Cut Line= 6
1624250.20117073467830.6988227221624530.28886513467731.111423478
1624792.34247489467637.9373972271624957.22994038467579.310217887
1625027.89613764467554.1846119761625570.03744181467361.422530308
#Sta/Elev= 30
       0  872.19    88.4  908.26   144.9  939.62   166.9  940.52   182.5  930.59
   189.4   922.4   199.9  905.78   234.7  884.11     280  832.83   303.1  817.04
   328.8  795.54   344.2  789.94   380.9   767.6   454.1  735.94   506.3   707.2
   527.2  700.31   575.9  693.42   603.8  684.36   635.1  682.77   646.8674.0054
     656  672.56   794.9674.0125   809.2  685.04   819.7  686.97  1050.5  688.13
  1094.7  706.66  1216.6  724.14  1289.7  740.49  1376.8  754.03  1400.8  759.96
#Mann= 3 ,-1,0
       0      .1       0   646.8    .045       0   794.9      .1       0
Bank Sta=646.8,794.9
XS Rating Curve= 0 ,0
Exp/Cntr(USF)=0,0
Exp/Cntr=0.3,0.1

Type RM Length L Ch R = 1 ,25812   ,980.1,1000,1015
XS GIS Cut Line= 6
1624754.24150123 468854.526499481625394.21233414468462.705760807
1625457.01470198 468421.647443981625529.82951698468373.003184304
1625687.97322956468266.2301038951625934.26079471468099.193364471
#Sta/Elev= 30
       0  826.86   208.6  817.07   268.2  815.96   286.8  814.04   311.2  808.54
   349.2  794.73   426.1  753.68   443.9  740.54     453  727.47   459.1  721.27
   483.8  703.97     503  697.05   533.8  693.48   560.7  684.86   591.5  682.25
   605.7673.8738   649.2   672.5   753.1   672.5   770.3673.8733   780.6  682.65
     808  685.07   944.3  682.43   965.9  685.22  1008.1  695.69  1038.8  700.01
  1156.9  725.07  1330.4  750.89  1346.3  754.13    1374  763.84  1401.4  769.38
#Mann= 6 ,-1,0
       0     .05       0  377.27      .1       0  585.39     .05       0
   605.7    .045       0   770.3     .05       0  905.42      .1       0
Bank Sta=605.7,770.3
XS Rating Curve= 0 ,0
Exp/Cntr(USF)=0,0
Exp/Cntr=0.3,0.1

Type RM Length L Ch R = 1 ,24812   ,592.3,617.5,638.5
XS GIS Cut Line= 6
 1625143.4162478469590.6510114821625332.44835006469529.011042893
1625607.26833847469439.3950803881625856.83509655469358.014993817
1626192.56145921469248.5385067311626475.18097273469156.380226478
#Sta/Elev= 30
       0  721.83     104  709.04   176.5  706.93   346.5   692.1   490.5  686.83
     563  679.43   614.7  680.81     626673.6718   635.4   672.5   764.7673.6806
   773.5  680.35   794.2  679.51   856.6  691.27   903.4  705.38   958.1  715.78
  1011.6   734.4  1029.9  737.36  1059.5  747.75    1091  755.65  1132.4  775.35
  1156.5  780.84  1178.4  792.49  1201.4  809.07  1218.6  816.48  1241.7  833.13
  1260.3  854.62  1278.1   869.6  1301.5  876.24  1342.9  880.34  1400.8  911.68
#Mann= 4 ,-1,0
       0     .05       0     626    .045       0   764.7    .025       0
  810.39      .1       0
Bank Sta=626,764.7
XS Rating Curve= 0 ,0
Exp/Cntr(USF)=0,0
Exp/Cntr=0.3,0.1

Type RM Length L Ch R = 1 ,24194   ,107.1,104.1,103.8
XS GIS Cut Line= 5
1625171.99429858 469896.879007271625445.98191118469960.864138358
1625595.28055039 469975.629937841626015.28551343469985.473804162
1626348.33632397 469975.62993784
#Sta/Elev= 30
       0  704.35    65.5  698.09   240.7  693.53   277.7  694.29   366.8  692.61
   567.3  683.69   616.5  679.09     642673.4687   652.6   672.5   773.3673.4852
   790.2  681.61   823.3  693.39   846.2  694.61   869.2  705.38   888.9  712.01
   951.3  744.52   967.7  756.42   977.5  768.14   980.8   770.6   994.2  774.94
  1026.8  791.23  1039.9  802.98  1072.7  825.24  1105.5  861.86  1112.1  867.57
  1128.5  874.09  1144.9  875.45  1158.1  879.25  1171.2  885.19  1184.7  894.14
#Mann= 7 ,-1,0
       0     .06       0     150     .05       0     250     .06       0
  361.36     .05       0     642    .045       0   773.3    .025       0
  781.39      .1       0
Bank Sta=642,773.3
XS Rating Curve= 0 ,0
Exp/Cntr(USF)=0,0
Exp/Cntr=0.3,0.1

Type RM Length L Ch R = 1 ,24090   ,672.1,777,845
XS GIS Cut Line= 6
1625177.80286271469985.1093580941625347.54324797470015.005403125
1625523.09219737 470054.380868411625708.48501309470083.912467374
1625984.11327008470087.1937561481626325.83997271470048.286458701
#Sta/Elev= 30
       0  697.69   115.5  689.77   172.4  692.91   303.2   693.2   444.1  686.03
   565.9  686.04   582.4  684.86   595.5  681.94     602  679.64   612.8673.4225
   621.7   672.5   754.3673.4187     770  680.99   797.9  691.49   808.7  693.87
   835.1  694.61   848.3  701.85   860.9  706.58     881  718.25   899.4  733.52
   940.8  756.41     954  769.55     987  784.17   996.9  789.93  1010.1  803.24
  1049.7  830.08  1085.9   867.8  1109.2  875.24  1152.1   891.8  1159.6  892.13
#Mann= 5 ,-1,0
       0     .06       0  302.35     .05       0  569.99    .025       0
   612.8    .045       0   754.3      .1       0
Bank Sta=612.8,754.3
XS Rating Curve= 0 ,0
Exp/Cntr(USF)=0,0
Exp/Cntr=0.3,0.1

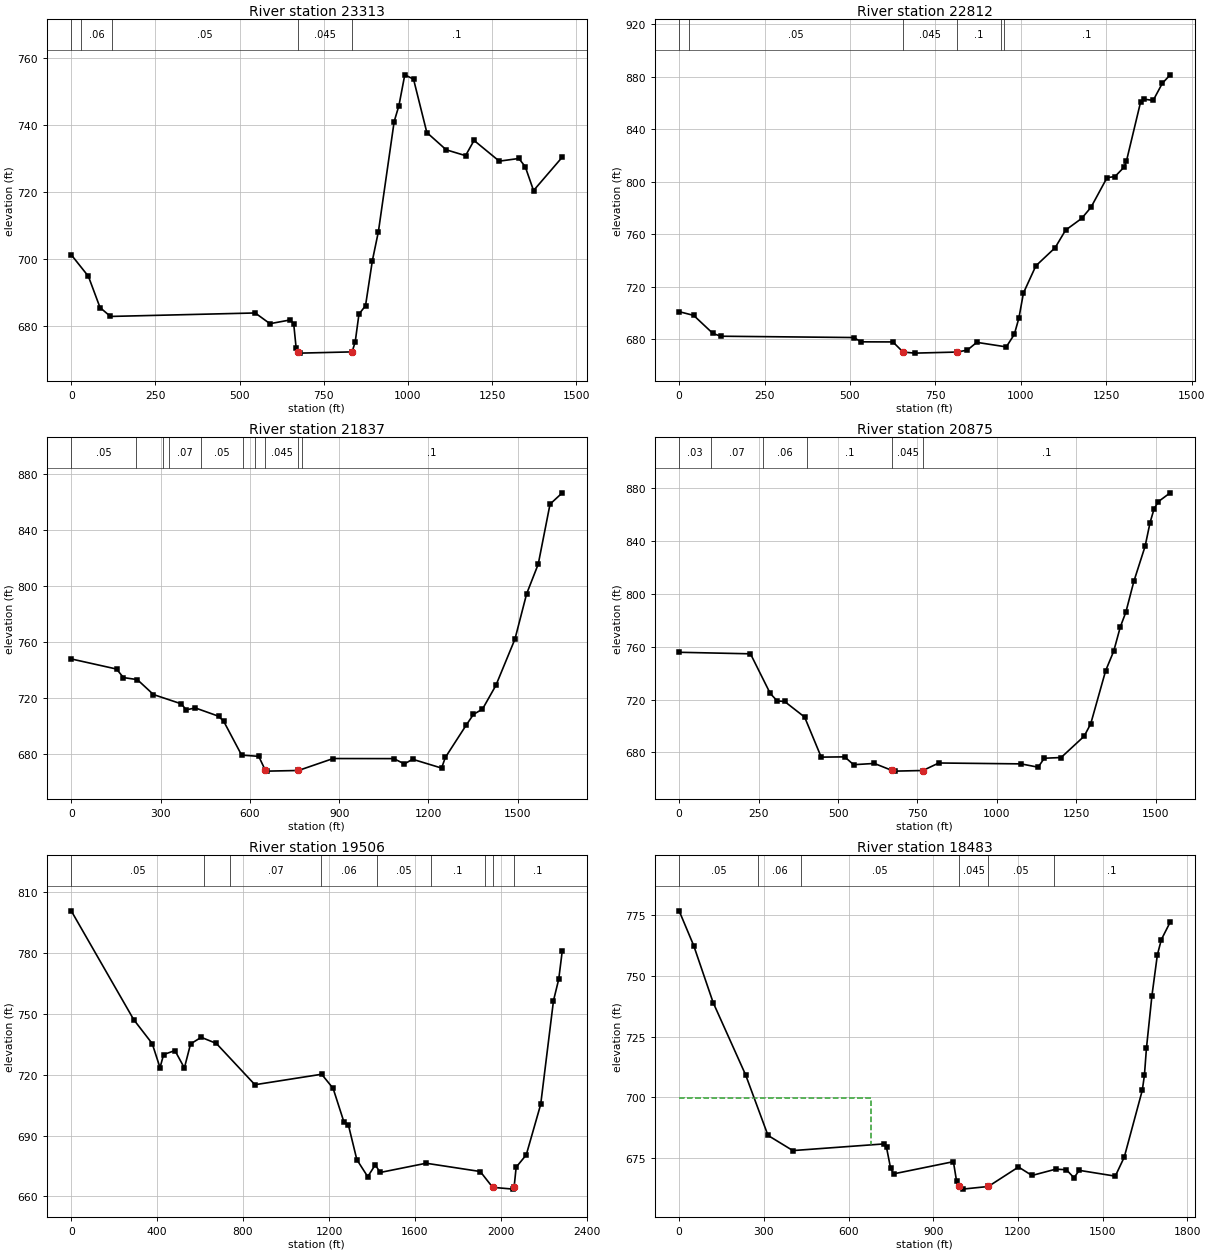
Type RM Length L Ch R = 1 ,23313   ,449.8,501.5,548.9
XS GIS Cut Line= 6
1625124.98386997469991.5383330581625168.61436014470126.643377811
1625269.40582523470311.7365115581625314.10357048470399.426296815
1625408.05056106 470638.598062561625716.26451156471322.598334983
#Sta/Elev= 30
       0  701.21      51  694.75    85.5  685.41   116.5  682.74   546.4  683.78
   590.2  680.57   650.1  681.69   660.7  680.58   667.8  673.44   672.3672.1362
   679.3  671.76   834.3672.1333   843.5  675.21   854.5  683.43     874  685.95
   894.4  699.48   912.3  708.16   959.1  741.09   973.2  745.84   990.6  755.06
  1016.6  753.76  1056.1  737.79  1113.6  732.62  1171.1  730.87  1196.3  735.42
  1271.2  729.22  1329.3  730.02  1348.2   727.6    1373  720.42  1458.4  730.43
#Mann= 5 ,-1,0
       0     .05       0      30     .06       0     120     .05       0
   672.3    .045       0   834.3      .1       0
Bank Sta=672.3,834.3
XS Rating Curve= 0 ,0
Exp/Cntr(USF)=0,0
Exp/Cntr=0.3,0.1

Type RM Length L Ch R = 1 ,22812   ,935.4,974.4,985
XS GIS Cut Line= 6
1625063.84750931469991.243386149 1625046.3416388470126.053483978
1625011.34400539470320.6521761421624976.55995423470508.115711972
1624959.40513289 470593.919018061624792.60297306471402.279606059
#Sta/Elev= 30
       0  701.13    42.6  698.28    98.9  684.51     122  682.41   511.2  681.41
   532.1  678.13   625.6  678.06   655.4670.3588   689.4  669.53   814.1 670.354
   843.6  671.86   871.1  677.74   957.5  674.28   980.9  683.79   994.3  696.16
  1007.7  715.36  1044.1  736.05  1100.4  749.83    1131  763.21  1178.2  772.19
  1205.4  780.64  1252.3   803.2  1275.7  804.09  1302.5  811.31  1309.2  815.93
  1350.3  860.59  1359.5  863.09  1387.3  862.04  1414.2  875.11  1437.2  881.56
#Mann= 6 ,-1,0
       0     .06       0      30     .05       0   655.4    .045       0
   814.1      .1       0  941.83     .05       0  949.33      .1       0
Bank Sta=655.4,814.1
XS Rating Curve= 0 ,0
Exp/Cntr(USF)=0,0
Exp/Cntr=0.3,0.1

Type RM Length L Ch R = 1 ,21837   ,947.3,962.1,974.4
XS GIS Cut Line= 6
1624632.58984163469530.6206197291624474.08687781469782.491835147
1624421.66277005469864.0369476381624368.92271805469941.552212566
1624318.89132206470013.3375020621623894.45070325470999.852694522
#Sta/Elev= 30
       0  748.08   152.2  740.86   175.4  734.76     222  733.31   276.3  722.63
   369.8  715.99   386.3  711.72     417  713.06   494.9  707.15   512.4  703.44
   572.4  679.36   629.9  678.47   652.4  668.37   658.5  667.91  763.41668.3741
   879.9  676.91  1083.5  676.85  1119.2  673.07  1146.9  676.39  1244.2  670.09
  1256.7  677.65  1326.3   700.6  1351.3  708.47  1381.6  712.23  1426.5  729.14
  1490.6  762.23  1529.9  794.64  1568.9  815.85  1608.5   858.7  1649.7  866.79
#Mann= 10 ,-1,0
       0     .05       0  219.05     .07       0  307.59     .06       0
  327.59     .07       0  434.54     .05       0  575.79      .1       0
  615.79     .05       0   652.4    .045       0  763.41     .05       0
  775.79      .1       0
Bank Sta=652.4,763.41
XS Rating Curve= 0 ,0
Exp/Cntr(USF)=0,0
Exp/Cntr=0.3,0.1

Type RM Length L Ch R = 1 ,20875   ,1340.1,1369.2,1357
XS GIS Cut Line= 4
1623857.61173281469165.8962835671623785.02263914469240.031962067
1623597.04596051469479.3502136261622879.53244291470361.614310034
#Sta/Elev= 30
       0  755.68   224.5  754.52   286.7  724.59   308.6  718.94     332  718.51
   394.9  706.74   447.1  676.49     521  676.68     549  670.77   614.3  671.71
   669.9  666.42   678.3  665.91   767.1  666.38   817.2  672.06    1076  671.38
  1129.7  668.88  1149.1  675.65    1202  676.18  1274.6   692.3  1295.3  701.75
  1342.2  741.79  1367.6  756.56  1388.3  774.85  1405.7  785.93    1431  809.32
  1466.3  835.74  1481.8  853.53  1494.5  863.99  1507.9  869.46  1545.3  876.12
#Mann= 6 ,-1,0
       0     .03       0     100     .07       0  263.76     .06       0
  403.76      .1       0   669.9    .045       0   767.1      .1       0
Bank Sta=669.9,767.1
XS Rating Curve= 0 ,0
Exp/Cntr(USF)=0,0
Exp/Cntr=0.3,0.1

Type RM Length L Ch R = 1 ,19506   ,1025.8,1023.1,995.5
XS GIS Cut Line= 3
1624061.41321681468445.1092216031623243.29966545468546.955822503
1622202.31392854469573.407043426
#Sta/Elev= 30
       0  800.59   291.1  747.02   377.1  735.24   413.4  723.39   430.1  729.84
   482.8  731.82   526.9  723.25   555.6  735.08   605.2  738.34   675.6  735.33
   855.3     715    1166  720.16  1219.3  713.22  1269.9  696.59  1290.3  695.28
  1329.8  678.13  1380.5  669.75  1415.5  675.54  1438.7  671.82  1652.4  676.36
  1904.3  672.29  1962.1 664.507  2057.8  663.62  2061.9664.4782  2071.6  674.42
  2118.5  680.46  2185.8  705.33  2245.4  756.39  2269.8  766.94  2286.4  781.01
#Mann= 9 ,-1,0
       0     .05       0     620     .06       0     740     .07       0
 1164.43     .06       0 1424.43     .05       0 1674.43      .1       0
 1924.43     .08       0  1962.1    .045       0  2061.9      .1       0
Bank Sta=1962.1,2061.9
XS Rating Curve= 0 ,0
Exp/Cntr(USF)=0,0
Exp/Cntr=0.3,0.1

Type RM Length L Ch R = 1 ,18483   ,1604.6,1541.1,1429.3
XS GIS Cut Line= 3
1622300.64831418467488.5239251211622278.27650974468155.203697262
1621745.82756421469085.870761727
#Sta/Elev= 30
       0  776.89    51.6  762.57   120.5  739.07   235.4  709.29   314.7  684.31
   402.8  678.05   725.7   680.8   734.5  679.38   748.9  670.82   759.7  668.45
   971.4  673.48   982.7  665.43   991.3663.2575  1003.8  662.16    1095663.2462
  1201.9  671.28  1249.7  667.79  1334.2   670.4  1371.7  670.14  1398.5  666.84
  1417.2   669.9  1544.8  667.51  1576.6  675.36  1640.4  702.89    1648  709.13
  1655.1   720.2  1674.4  741.73  1693.8  758.73  1707.9  765.03  1739.3  772.25
#Mann= 6 ,-1,0
       0     .05       0     280     .06       0     430     .05       0
   991.3    .045       0    1095     .05       0 1327.06      .1       0
#XS Ineff= 2 , 0
          678.69  699.75
Permanent Ineff=
       F       F
Bank Sta=991.3,1095
XS Rating Curve= 0 ,0
Exp/Cntr(USF)=0,0
Exp/Cntr=0.3,0.1

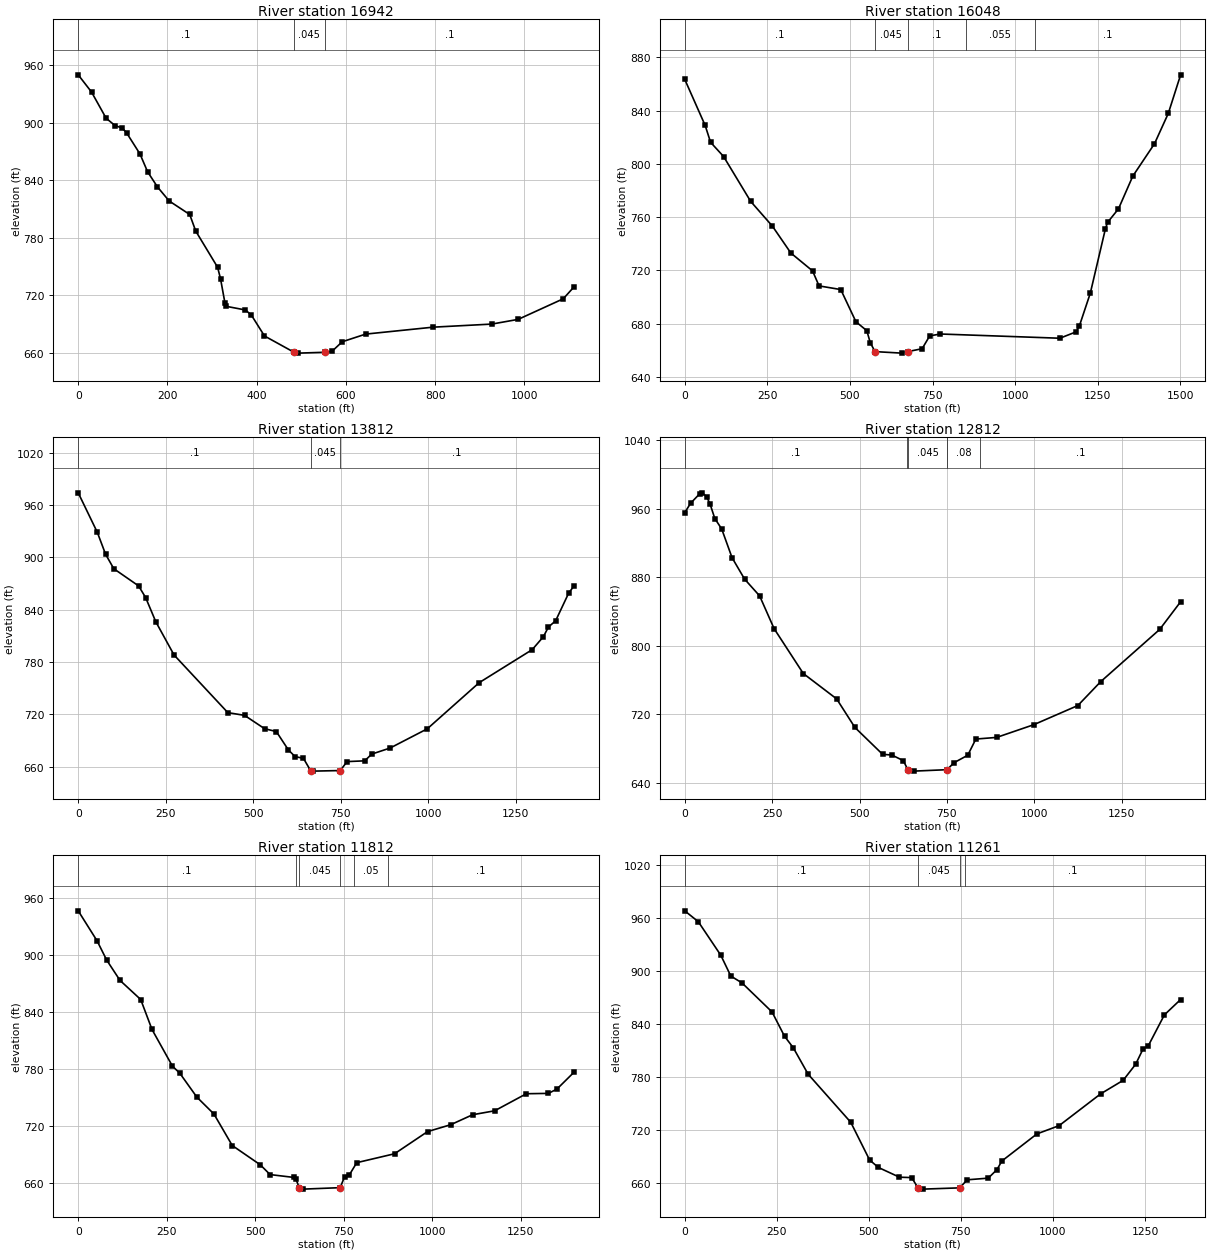
Type RM Length L Ch R = 1 ,16942   ,881.5,893.7,890.3
XS GIS Cut Line= 2
1620475.10907234468880.0501609321621584.75057228468817.409108516
#Sta/Elev= 30
       0   949.9    29.8  931.99    62.6  904.58    82.4     897    98.8  894.31
   108.6  889.23   138.4  867.34   155.5  848.74   177.7  832.85   203.9  818.23
   249.9  804.14   263.4  786.83   312.4  749.07     319  736.99   328.8  711.93
   332.1  708.26   374.8  704.47     388  699.21   417.5  677.34   483.8660.3176
   493.1  659.44   552.5660.3256   568.7  661.26   591.7   671.3   644.3   679.3
   795.4  686.53   926.9  689.75     986  694.66  1087.1  716.15  1111.4  728.67
#Mann= 3 ,-1,0
       0      .1       0   483.8    .045       0   552.5      .1       0
Bank Sta=483.8,552.5
XS Rating Curve= 0 ,0
Exp/Cntr(USF)=0,0
Exp/Cntr=0.3,0.1

Type RM Length L Ch R = 1 ,16048   ,2234.5,2236.2,2219.1
XS GIS Cut Line= 3
1620600.53334725469725.5949486061621955.68967194469678.081572708
1622082.86830519469747.082182055
#Sta/Elev= 30
       0  863.42    61.8   828.8    78.2  816.17   117.6  805.48   199.6   771.8
   265.4   753.2   321.2  733.05   386.8  719.66   406.5  708.39   472.2  705.65
   518.1  681.49     551  674.77   561.3  665.91   575.7659.0818   656.5  657.94
   675.2659.0737   718.4  661.26   741.4   670.9   773.8  672.29  1135.3  669.12
  1184.5  673.92  1194.4  678.41  1227.4  702.96  1273.2  751.37  1279.8   756.1
  1312.6  766.21    1356  790.78  1421.6  815.07  1463.4  837.85  1500.7  866.79
#Mann= 5 ,-1,0
       0      .1       0   575.7    .045       0   675.2      .1       0
     850    .055       0    1060      .1       0
Bank Sta=575.7,675.2
XS Rating Curve= 0 ,0
Exp/Cntr(USF)=0,0
Exp/Cntr=0.3,0.1

Type RM Length L Ch R = 1 ,13812   ,984.2,1000,1002.9
XS GIS Cut Line= 6
1620517.27162872471872.6848332291621407.62614723471671.095341399
1621592.15694614471622.8684037331621683.94350797471582.489547476
1621778.08242731471538.8321544831621880.12224947471502.164248809
#Sta/Elev= 30
       0  974.05    54.5  928.81    78.1  903.71   101.6  887.06   172.3   867.4
   192.5  854.04   221.6  826.23   273.7  788.17   427.3  722.08     475  718.96
   532.2  703.68   565.8  700.39   600.1  679.39   619.3  671.68   643.2  669.69
   663.5655.6935   670.1  655.03   748.5655.6964   767.7  665.95   818.1  666.83
   838.3  674.56   890.9  681.54   996.9  703.54  1145.1  756.44  1296.5  794.29
  1328.3  809.07  1342.9  820.23  1363.4  827.37  1400.6  859.08  1416.1  867.47
#Mann= 3 ,-1,0
       0      .1       0   663.5    .045       0   748.5      .1       0
Bank Sta=663.5,748.5
XS Rating Curve= 0 ,0
Exp/Cntr(USF)=0,0
Exp/Cntr=0.3,0.1

Type RM Length L Ch R = 1 ,12812   ,1012.1,1000,985.3
XS GIS Cut Line= 6
1620727.43196955472669.4430822281621476.26577371472621.130514815
1621550.92310472472613.4048084771621730.97720656472589.025592148
1622034.25776798472553.4111620631622139.15486789472539.807842806
#Sta/Elev= 30
       0  955.69    16.9  966.71    43.2  977.89    49.8  978.83      63  974.16
    72.8  965.25      86  948.82   105.7  936.62   135.3  903.03   171.2  877.97
   214.2  858.35   255.5  820.15   339.1  767.62   434.5  737.95   486.7  704.59
     566  673.15   592.3  672.37   625.2  665.77   638.1655.2369   654.7  653.53
   750.3655.2224   769.9   663.3   809.5  672.12   832.6  691.02   892.1  692.94
   998.1  707.77  1124.4  730.22  1189.7  758.11  1358.3   819.1  1418.3  851.51
#Mann= 6 ,-1,0
       0      .1       0  635.39     .08       0   638.1    .045       0
   750.3      .1       0  750.39     .08       0  845.45      .1       0
Bank Sta=638.1,750.3
XS Rating Curve= 0 ,0
Exp/Cntr(USF)=0,0
Exp/Cntr=0.3,0.1

Type RM Length L Ch R = 1 ,11812   ,544.8,551,551.5
XS GIS Cut Line= 6
1621181.54064138473734.2624748951621278.15199672473709.288115397
1621372.61571856473678.9400789741621647.66503721473590.030151814
 1621730.9230728 473563.116491721622516.30043906473309.242983729
#Sta/Elev= 30
       0   946.4    53.2  914.87    80.4  894.61     118  873.22   176.6  853.05
   208.5  821.53   266.2  782.96   286.9  775.57   335.2  750.36   383.5  732.57
   435.2  699.43   514.5  679.11   542.1  668.84     611  665.77   614.5  664.68
   624.5 655.049   635.2  653.53   740.1  655.07   752.4  666.42   766.2   668.6
   786.9  681.37   893.8  690.75   986.9  714.05  1052.4  721.32  1114.4  731.83
  1176.5  735.95  1266.1  753.92  1328.2  754.28  1352.4  758.77    1401  776.65
#Mann= 6 ,-1,0
       0      .1       0  615.57     .08       0   624.5    .045       0
   740.1     .07       0  780.57     .05       0  875.57      .1       0
Bank Sta=624.5,740.1
XS Rating Curve= 0 ,0
Exp/Cntr(USF)=0,0
Exp/Cntr=0.3,0.1

Type RM Length L Ch R = 1 ,11261   ,443.7,449,452.9
XS GIS Cut Line= 2
1621286.15212952474239.6617845211622588.19114759473895.135996233
#Sta/Elev= 30
       0  968.42    36.8  956.12    97.9  918.21   125.1  894.64   155.6  886.83
   237.1     854     271  826.52   294.8   813.5   335.2  783.53   450.9  729.18
   502.1  686.53   525.7   678.1   583.2  667.04   616.3  666.59   633.6654.9511
   646.5  653.54   746.6654.9767   767.3  664.09   824.2  665.96   847.8  675.52
   861.5  685.42   956.5  716.03  1016.8  725.37  1129.6  761.34  1190.7  776.63
  1224.6  794.79    1245  812.34  1258.6  815.41  1302.7  850.69  1346.8  868.09
#Mann= 4 ,-1,0
       0      .1       0   633.6    .045       0   746.6    .025       0
     760      .1       0
Bank Sta=633.6,746.6
XS Rating Curve= 0 ,0
Exp/Cntr(USF)=0,0
Exp/Cntr=0.3,0.1

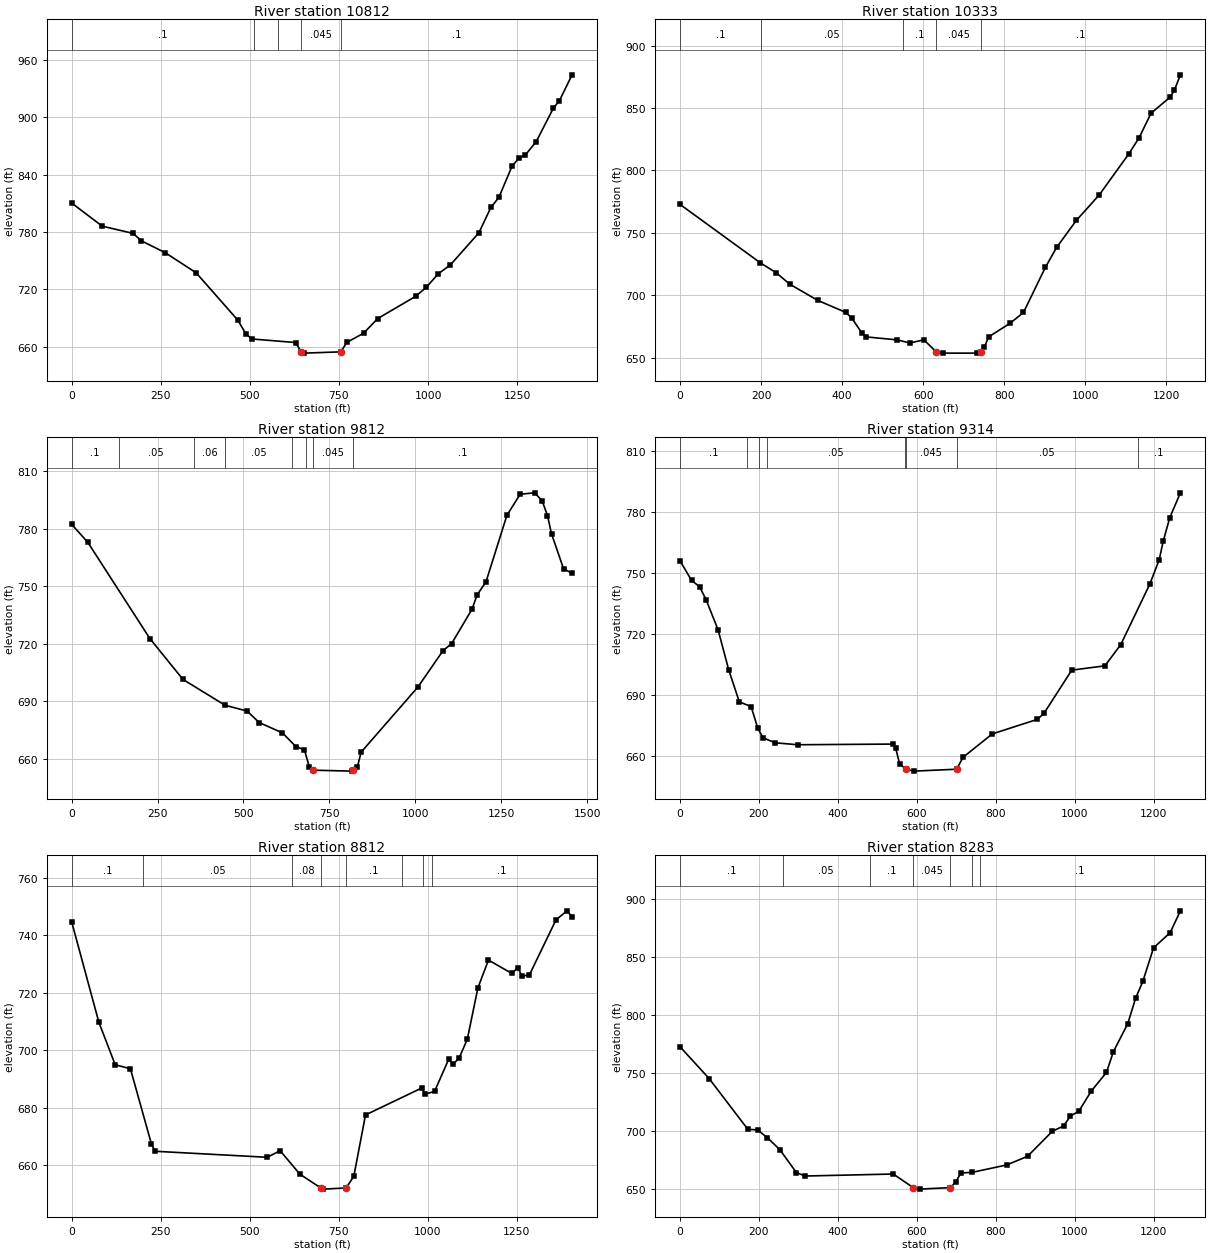
Type RM Length L Ch R = 1 ,10812   ,448.8,479,516.7
XS GIS Cut Line= 6
1621397.00608972474603.6193319711621499.91697314474598.214815229
1621597.18449514474578.480602726 1621693.9822018474560.574798644
1622041.68294998474498.9184258881622780.54662973474367.896378234
#Sta/Elev= 30
       0  810.29    85.6  786.15   172.3  778.58   195.8   770.8   262.5  758.42
   349.2  737.46   466.1  688.02   489.2  673.47   505.8  668.31   629.1  664.56
   643.5654.8779   652.4  653.53   755.1  654.86   772.4  664.83     819  674.26
     859  689.68   965.6   712.9   995.3  722.32  1028.9  736.45  1062.3  745.48
  1142.5  779.09  1176.4  805.67  1198.9  816.21  1235.5  848.53  1255.5  857.47
  1272.2  860.02  1303.8  874.52  1352.1  909.56  1368.8  917.21  1404.3  944.19
#Mann= 5 ,-1,0
       0      .1       0  511.37     .05       0  578.87      .1       0
   643.5    .045       0   755.1      .1       0
Bank Sta=643.5,755.1
XS Rating Curve= 0 ,0
Exp/Cntr(USF)=0,0
Exp/Cntr=0.3,0.1

Type RM Length L Ch R = 1 ,10333   ,481.1,521,567.6
XS GIS Cut Line= 2
1621487.49836943474669.2004296581622601.61423025475201.649375194
#Sta/Elev= 30
       0  772.72   198.2  725.91   238.1  717.78   270.8  708.78   339.9   695.8
     409  686.16   423.6  681.75     449  669.56   459.9  666.52   536.3  664.13
   567.1  661.64   601.7  664.17     632654.6971     649  653.53   732.6  653.53
   742.6 654.695   750.8  658.14   761.7  666.57   814.3   677.4   847.6  686.11
   901.7  722.32   929.5  738.29     978  759.89  1034.4  780.24  1107.2  813.04
  1132.6  825.97  1162.5  845.82  1209.3   858.6  1219.9  864.17  1234.8  876.54
#Mann= 5 ,-1,0
       0      .1       0     200     .05       0     550      .1       0
     632    .045       0   742.6      .1       0
Bank Sta=632,742.6
XS Rating Curve= 0 ,0
Exp/Cntr(USF)=0,0
Exp/Cntr=0.3,0.1

Type RM Length L Ch R = 1 ,9812    ,485.6,497.3,504.1
XS GIS Cut Line= 6
1621389.52480547474692.7093768861621484.95473272474776.394576982
1621554.35518447474866.7644749731621599.84229822474960.372555479
1621740.74260697475292.8896069821622005.38873123475995.063727558
#Sta/Elev= 30
       0  782.29      47  772.89   227.6   722.7     324  701.37   446.3  687.92
   510.7  684.87   545.7  678.88   613.4  673.51   652.5  666.36   677.4  664.64
   691.6  655.82   701.3654.0439   814.6  653.54   819.6 654.045   831.5  655.75
   842.6  663.45  1007.9  697.45    1081  716.44  1105.6  719.98  1165.2  738.02
  1180.3  745.56  1205.8  752.24  1266.8  787.01  1305.4  798.01  1347.5  798.74
  1369.4  794.61  1384.9  786.86  1396.6  777.41  1431.6  759.16  1456.5  756.73
#Mann= 8 ,-1,0
       0      .1       0  136.93     .05       0  354.94     .06       0
  446.33     .05       0   641.1     .08       0   681.1      .1       0
   701.3    .045       0   819.6      .1       0
Bank Sta=701.3,819.6
XS Rating Curve= 0 ,0
Exp/Cntr(USF)=0,0
Exp/Cntr=0.3,0.1

Type RM Length L Ch R = 1 ,9314    ,504.6,502,511
XS GIS Cut Line= 2
 1621156.3956638474857.1235869061621424.85731701476096.521552564
#Sta/Elev= 30
       0  756.09    29.3  746.37    49.5  743.31    66.3   736.8    96.5  722.05
   123.3  702.41   150.2  686.59   180.4  684.16   197.2  673.48   210.6  668.83
   240.8  666.38   297.9  665.41   539.6  665.74   546.3  663.95   556.4   656.1
   571.8653.3577   592.8  652.41   700.9 653.356   717.5  659.27   791.4  670.74
   905.5  677.92   922.3  680.85   992.8  702.18  1076.7  704.29    1117  714.75
  1190.8  744.66  1214.5  756.63  1224.4  765.59  1241.2  777.32  1268.1  789.55
#Mann= 8 ,-1,0
       0      .1       0     170     .05       0     200      .1       0
     220     .05       0     570     .07       0   571.8    .045       0
   700.9     .05       0    1160      .1       0
Bank Sta=571.8,700.9
XS Rating Curve= 0 ,0
Exp/Cntr(USF)=0,0
Exp/Cntr=0.3,0.1

Type RM Length L Ch R = 1 ,8812    ,528.3,529.1,556.2
XS GIS Cut Line= 6
1620839.56330697474885.212600812 1620815.6611238475281.905705065
1620806.83076088475464.2481881381620804.93312688475539.575137228
1620810.63915221475639.4207380561620857.00782588476288.157629564
#Sta/Elev= 30
       0  744.61    76.2  709.79   122.2  694.98     165  693.58   224.1  667.43
     234  664.93   549.4  662.84   585.5  665.13   641.3  656.95     700652.1732
     707  651.78   771.1 652.185   792.6  656.28   825.4  677.55   983.3   686.9
   993.1  684.79  1019.4  685.72  1058.9  696.83  1072.1  695.22  1088.5  697.36
  1111.4  703.85  1141.1  721.65  1170.7  731.34  1236.5   726.7    1253  728.71
  1265.2  725.77  1285.9   726.2  1360.3  745.25  1391.1  748.44  1405.7  746.45
#Mann= 8 ,-1,0
       0      .1       0  200.48     .05       0  619.97     .08       0
     700    .045       0   771.1      .1       0  927.83     .05       0
  987.83     .06       0 1011.58      .1       0
Bank Sta=700,771.1
XS Rating Curve= 0 ,0
Exp/Cntr(USF)=0,0
Exp/Cntr=0.3,0.1

Type RM Length L Ch R = 1 ,8283    ,464.4,471.6,485.2
XS GIS Cut Line= 2
1620538.93386141474816.8543389251620091.49777273 476002.55997394
#Sta/Elev= 30
       0  772.53    73.7  745.19   171.9  701.48   196.4  700.99     221  694.41
   253.1  683.92   294.6  664.35   316.7  661.33   540.1  663.05   590.6651.3588
     607  650.06   684.6651.3722   697.9  655.88   711.3  663.96     740  664.49
   827.6  670.87   880.2  678.29   943.3  699.91   971.4  704.34   988.8  712.92
    1010  717.02  1041.5  734.34  1080.1  750.46  1097.6  768.27    1134  792.36
  1153.7  814.08  1172.2  828.75  1199.3  857.53  1241.4  870.67  1267.3  889.42
#Mann= 7 ,-1,0
       0      .1       0     260     .05       0     480      .1       0
   590.6    .045       0   684.6      .1       0     740     .06       0
     760      .1       0
Bank Sta=590.6,684.6
XS Rating Curve= 0 ,0
Exp/Cntr(USF)=0,0
Exp/Cntr=0.3,0.1

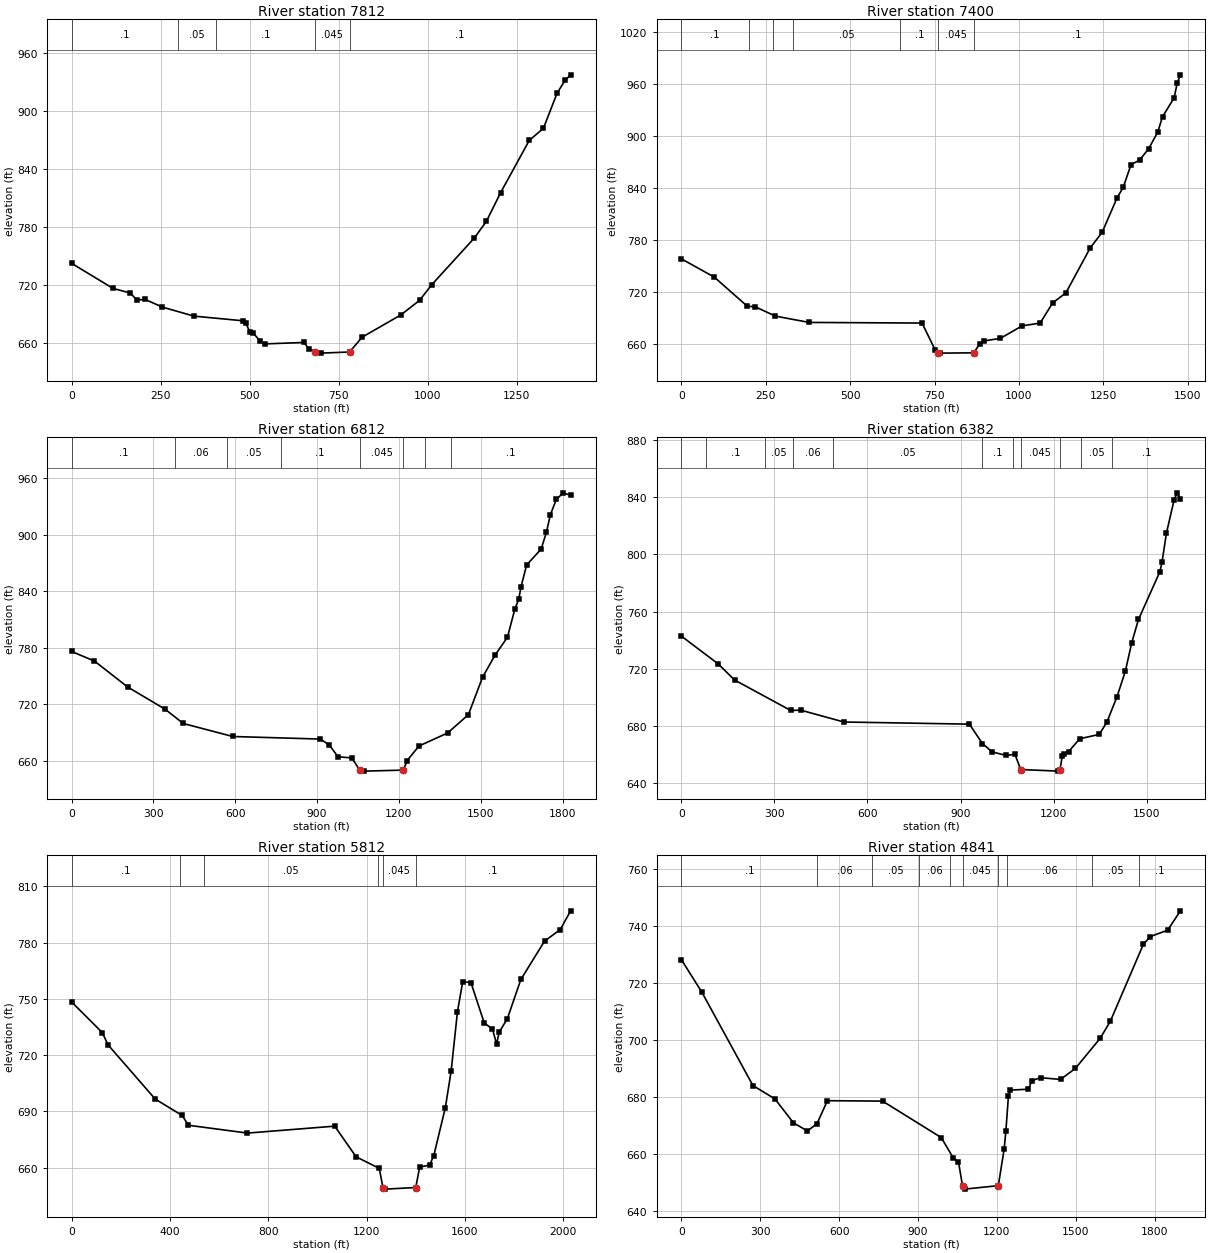
Type RM Length L Ch R = 1 ,7812    ,413.4,411.4,426.9
XS GIS Cut Line= 6
1620286.84984547474598.4047754711620232.23053214 474681.70382148
1620123.84787489474846.9951575551619971.34161822475079.579338059
1619681.75066197475521.2274048921619518.74901947475769.817786977
#Sta/Elev= 30
       0  742.74   116.1  716.81   164.9  712.01   182.8  704.88   206.4  705.45
   254.6   697.5   343.7  688.14     481  683.35   488.5  681.54   500.3  671.76
   509.8  670.79   528.1  662.66   543.8  659.46     652  660.92   666.2  654.28
   683.8651.0887   699.4  649.91   780.4651.0835   815.5   666.4   924.3  689.42
   976.6  704.41  1010.6  720.45  1130.6  768.93  1164.1  785.99  1204.1  815.62
  1284.6  869.75  1324.5  882.34  1362.8  918.64  1385.4  931.96  1400.8  937.56
#Mann= 5 ,-1,0
       0      .1       0  297.27     .05       0  404.14      .1       0
   683.8    .045       0   780.4      .1       0
Bank Sta=683.8,780.4
XS Rating Curve= 0 ,0
Exp/Cntr(USF)=0,0
Exp/Cntr=0.3,0.1

Type RM Length L Ch R = 1 ,7400    ,561.2,588.6,610.2
XS GIS Cut Line= 3
1620274.94656909 474454.431107091619899.10025459474588.661933695
1619169.77943004475385.098171555
#Sta/Elev= 30
       0  758.43    97.3  737.44   194.8  703.99   219.2  703.19   278.3  692.54
   378.4  685.26     713  684.53   751.9  653.65   760.6  650.25   765.8  649.91
   866.5650.2527   884.3  660.83   896.4  663.96     945  666.86  1009.7  681.31
  1063.1  684.52  1100.4  707.84  1139.3  719.24  1211.7  771.17  1246.9  789.06
  1291.3  828.94  1309.2  840.67  1332.4   866.9  1358.1  872.25  1384.8  885.37
  1411.4  904.16  1425.9  922.21  1460.2  943.87  1469.4  961.05    1479  970.37
#Mann= 7 ,-1,0
       0      .1       0     200     .06       0     270      .1       0
     330     .05       0   649.1      .1       0   760.6    .045       0
   866.5      .1       0
Bank Sta=760.6,866.5
XS Rating Curve= 0 ,0
Exp/Cntr(USF)=0,0
Exp/Cntr=0.3,0.1

Type RM Length L Ch R = 1 ,6812    ,427.8,429.9,437.5
XS GIS Cut Line= 6
 1620375.1510496 474092.03806835 1619957.9611008474120.660281245
1619851.48194981474149.4220776411619584.58287731474273.975306228
1619499.62799472474313.620568141 1618672.3819458474699.669008642
#Sta/Elev= 30
       0  775.91    83.8  765.73   205.4  738.19   342.9  714.53   409.3  699.38
   590.9  685.56   911.7  682.82   944.3  676.68   976.9  663.96  1027.6   662.8
  1056.2 649.808    1071  648.75    1216649.8208  1230.3     660  1273.7  675.47
  1378.4  689.26  1454.8  708.74  1506.7  748.57  1552.5  772.04  1598.1  791.08
  1624.9  820.83  1639.4  831.47  1647.4  844.31  1668.4  867.92  1721.5  884.74
  1740.8  902.54  1755.3  921.19    1777  937.47  1802.3  944.55  1829.6  941.86
#Mann= 8 ,-1,0
       0      .1       0     380     .06       0  568.47     .05       0
  766.12      .1       0  1056.2    .045       0    1216      .1       0
 1294.25     .05       0 1391.75      .1       0
Bank Sta=1056.2,1216
XS Rating Curve= 0 ,0
Exp/Cntr(USF)=0,0
Exp/Cntr=0.3,0.1

Type RM Length L Ch R = 1 ,6382    ,560.4,570.1,577.5
XS GIS Cut Line= 2
1620189.93371224473626.6743430221618677.59973248474177.020732105
#Sta/Elev= 30
       0  742.85   118.8  723.39   171.1  712.25   352.5  690.92   384.1  691.19
   523.7  682.88   928.7  681.38   970.6  667.84    1002  662.01  1047.4  659.49
  1075.4  660.37  1094.2649.6831  1215.4  648.56  1220.8649.6461  1228.2  659.03
  1232.5   660.8  1248.7  662.26  1284.8  671.19  1347.7  674.23  1372.1  682.84
  1404.8   700.6  1431.5  718.28  1452.4  738.37  1473.9  754.49  1543.2  787.94
  1550.2  794.99  1564.1  814.75  1589.1  838.25  1599.1  842.98  1609.4  838.49
#Mann= 11 ,-1,0
       0     .08       0      80      .1       0     270     .05       0
     360     .06       0     490     .05       0     970      .1       0
    1070    .025       0  1094.2    .045       0  1220.8      .1       0
    1290     .05       0    1390      .1       0
Bank Sta=1094.2,1220.8
XS Rating Curve= 0 ,0
Exp/Cntr(USF)=0,0
Exp/Cntr=0.3,0.1

Type RM Length L Ch R = 1 ,5812    ,956.2,971.1,987.1
XS GIS Cut Line= 6
1620194.47986834 473223.89321819 1619477.9137993473358.174972475
 1619381.8450938473383.1887019721619286.25112489473406.757552475
1618941.79840173473484.5369244811618209.83693914473649.819074228
#Sta/Elev= 30
       0   748.4   124.8  732.05   148.2  725.49     340  696.59   449.7  687.83
   475.3   682.6   715.6  678.43  1070.5  682.13  1157.4  665.78  1251.6  659.63
  1266.7  649.39  1275.1  648.53  1400.2649.3851  1416.2  660.33  1456.7  661.35
  1473.6  666.44  1520.5  691.97  1544.2  711.51  1569.9  743.24  1591.3  759.19
  1624.8  758.71  1678.7  737.22  1712.4   733.9  1729.2  725.88  1739.3   732.2
  1772.9  739.47  1827.8  760.38  1924.2  780.84  1988.2  787.02  2030.3  797.01
#Mann= 6 ,-1,0
       0      .1       0     440     .06       0     540     .05       0
 1244.89      .1       0  1266.7    .045       0  1400.2      .1       0
Bank Sta=1266.7,1400.2
XS Rating Curve= 0 ,0
Exp/Cntr(USF)=0,0
Exp/Cntr=0.3,0.1

Type RM Length L Ch R = 1 ,4841    ,154.6,154,152.8
XS GIS Cut Line= 6
1620023.45932868 472431.959867251619536.18714324472530.167777749
 1618885.4059645472530.1677777491618785.44265323 472527.54007952
1618591.81317755472508.3917384121618554.36125374472963.083070854
#Sta/Elev= 30
       0  728.25    77.9  716.83     272  684.12   355.7  679.43     426  671.04
   479.5  668.17   515.9  670.78   555.3  678.81   765.3  678.66   988.3  665.88
  1034.3  658.72    1054  657.37  1069.4648.9752    1077  647.78  1205.7     649
  1227.9  661.91  1234.5  668.32  1244.3  680.62  1251.1  682.52  1320.3  682.84
  1333.4  685.87  1366.6  686.87  1442.5  686.27  1498.9  690.14  1593.2  700.68
  1631.7  706.64  1757.3  733.63  1783.7  736.39  1849.5   738.6  1898.7  745.42
#Mann= 10 ,-1,0
       0      .1       0  517.07     .06       0  724.73     .05       0
  905.35     .06       0 1022.85     .07       0  1069.4    .045       0
  1205.7     .07       0 1237.85     .06       0 1562.48     .05       0
 1742.48      .1       0
Bank Sta=1069.4,1205.7
XS Rating Curve= 0 ,0
Exp/Cntr(USF)=0,0
Exp/Cntr=0.3,0.1