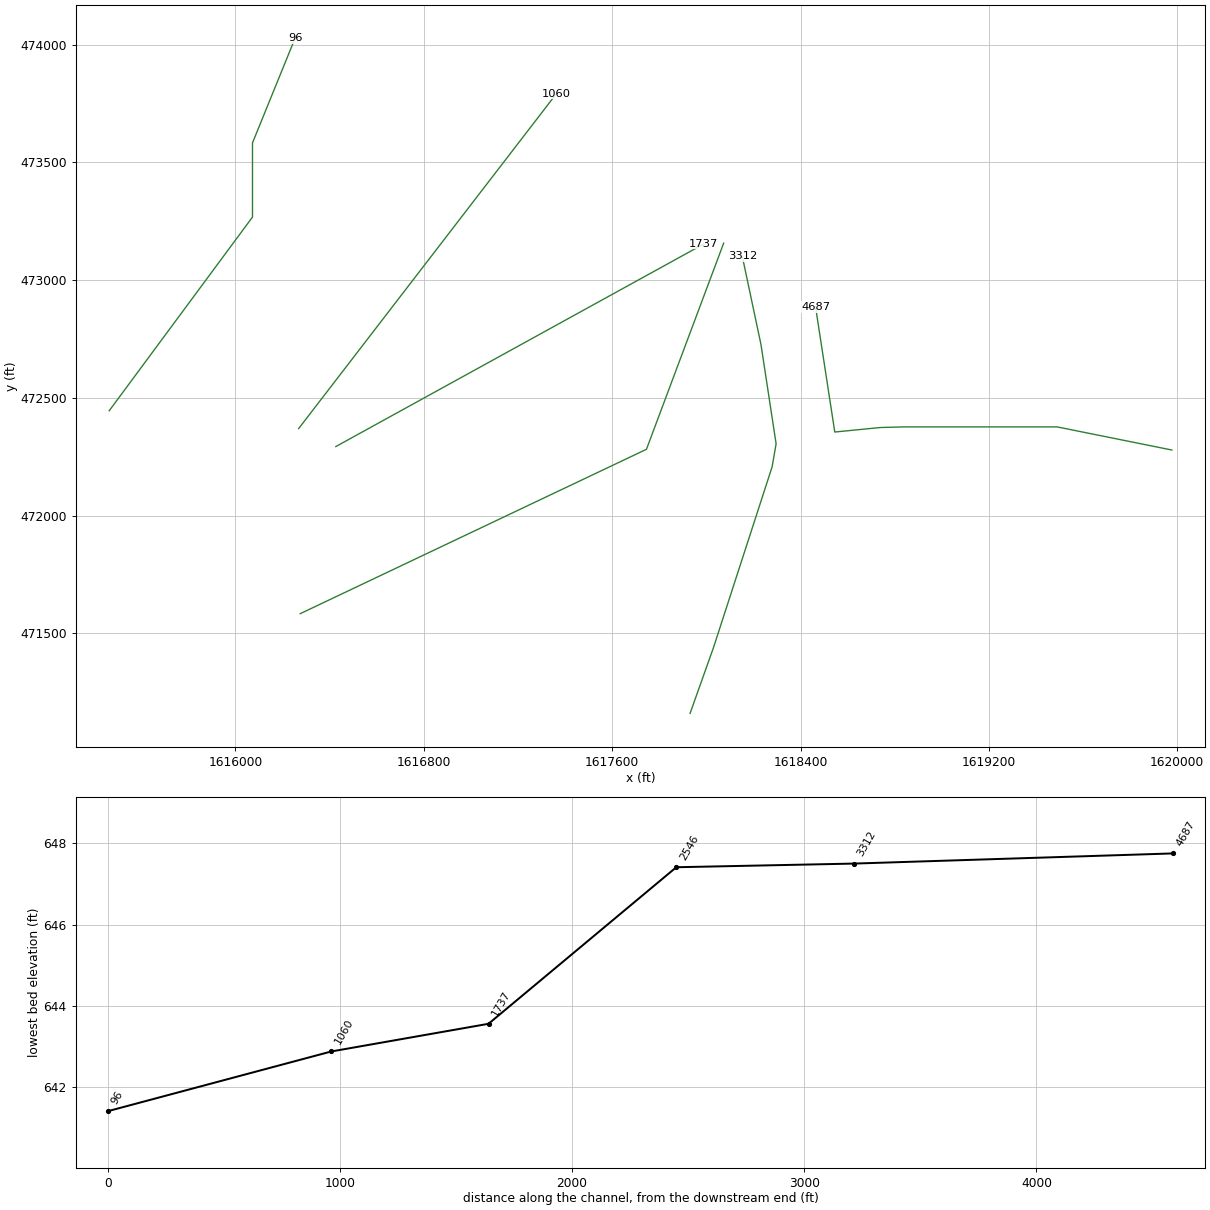
HEC-RAS study FshCrk.prj: FshCrk

--- FshCrk.g01 (geometry) --- (continued)

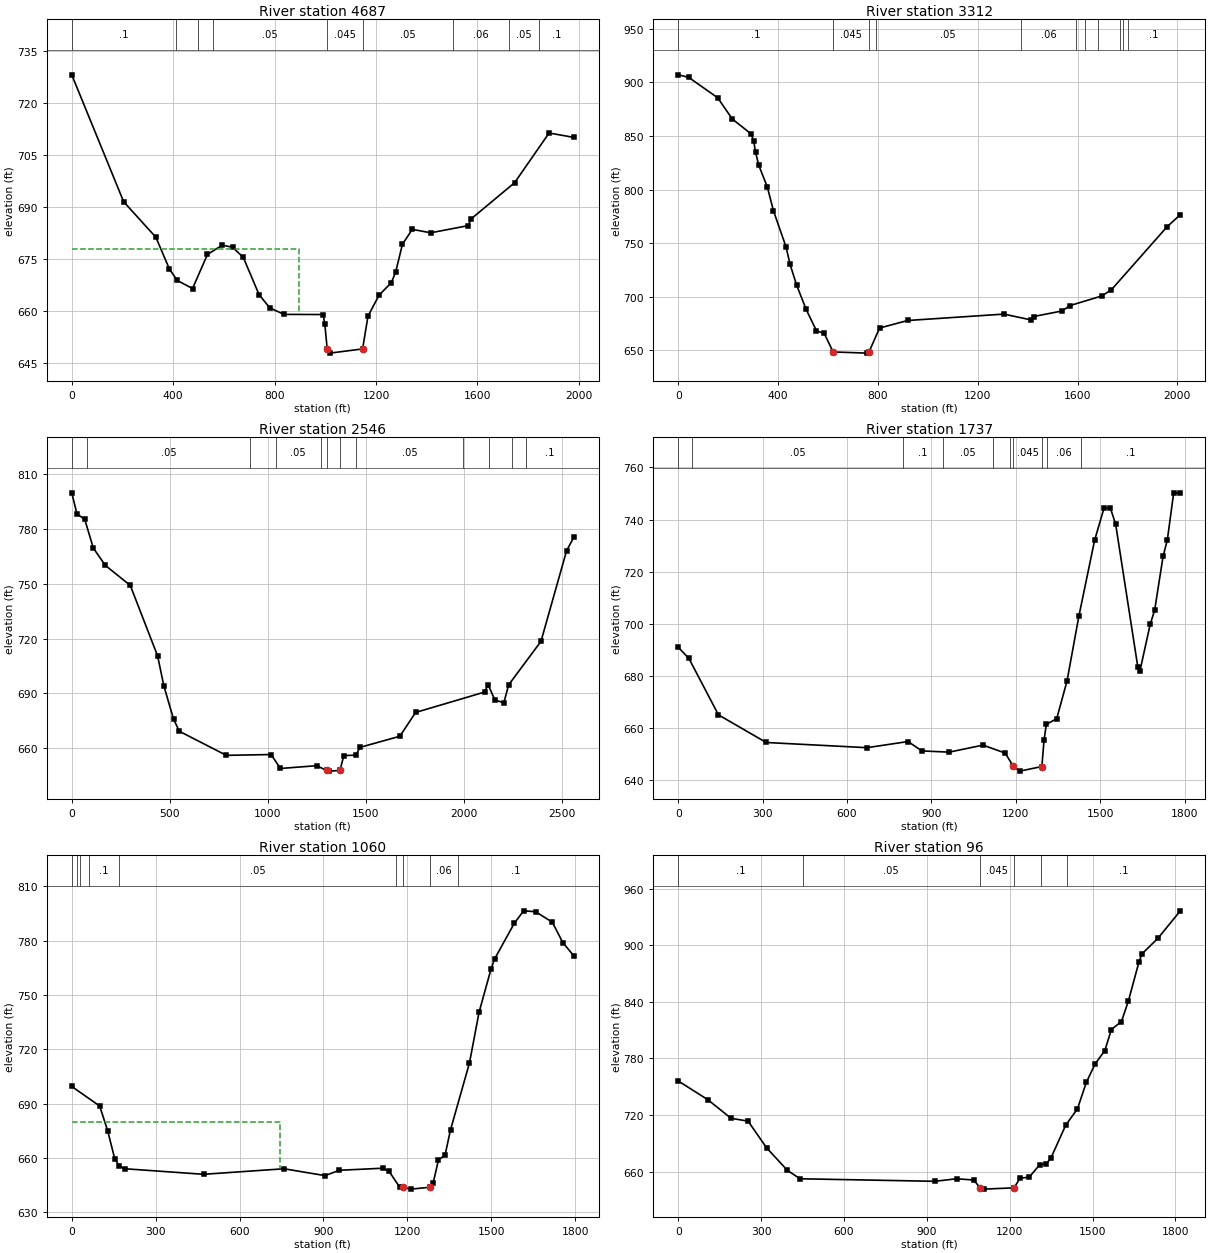
Type RM Length L Ch R = 1 ,4687    ,1504.8,1374.9,1237.6
XS GIS Cut Line= 6
1619977.11968554472278.1287208711619489.84750009472376.336631371
1618839.06632135472376.3366313711618739.10301008472373.708933142
 1618545.4735344472354.5605920341618463.78458208 472885.81109123
#Sta/Elev= 30
       0     728   204.6  691.41   331.8  681.15   385.4  671.93   416.3   668.7
   476.2  666.37   535.2  676.22   593.9  678.89     634  678.27   676.3  675.38
   738.6  664.62   780.9  660.79     837  658.92   991.2  658.88   997.8  656.21
  1007.3648.9859  1017.5  647.75  1146.9648.9605  1168.2  658.43  1212.4  664.52
  1259.9  668.03  1276.9  671.02  1304.1  679.17    1343  683.44  1415.6  682.45
  1563.7  684.52  1573.7  686.38  1746.3  696.89  1882.4  711.23    1980  709.95
#Mann= 9 ,-1,0
       0      .1       0     410     .06       0  497.07     .07       0
  557.07     .05       0  1007.3    .045       0  1146.9     .05       0
 1502.48     .06       0 1722.48     .05       0 1842.48      .1       0
#XS Ineff= 2 , 0
           894.8  677.77
Permanent Ineff=
       F       F
Bank Sta=1007.3,1146.9
XS Rating Curve= 0 ,0
Exp/Cntr(USF)=0,0
Exp/Cntr=0.3,0.1

Type RM Length L Ch R = 1 ,3312    ,797.9,766.1,734.2
XS GIS Cut Line= 6
1617930.89950489471159.561915651 1618030.5367728471439.756237149
1618279.26888689472206.6792439821618296.24457473472304.659034893
1618231.85034655472726.9078623061618152.71434997473100.137102723
#Sta/Elev= 30
       0   906.9    41.2  904.63   157.8  885.56     217  865.65   291.1     852
   302.1  845.62   309.9  834.58   322.8  822.57   357.3  802.09   381.5   780.2
   431.7  746.66   448.2  730.12   474.6  710.78   512.5  688.26   553.9  668.32
   584.9  665.85   620.7648.5978   757.4   647.5   764.4648.5668   806.7  670.89
   919.5  677.92  1305.1  683.88    1412  678.53  1424.6  681.64  1537.4  686.78
  1570.4  691.86  1697.4   700.8    1736  706.65    1959  765.34  2011.8  776.56
#Mann= 11 ,-1,0
       0      .1       0   620.7    .045       0   764.4      .1       0
  790.53     .05       0 1373.09     .06       0 1593.09     .05       0
 1630.23     .06       0 1680.23     .05       0 1770.23      .1       0
 1780.23     .05       0 1800.23      .1       0
Bank Sta=620.7,764.4
XS Rating Curve= 0 ,0
Exp/Cntr(USF)=0,0
Exp/Cntr=0.3,0.1

Type RM Length L Ch R = 1 ,2546    ,785.4,808.8,816.5
XS GIS Cut Line= 3
1616275.09277106471583.0755958691617745.54878244472281.183140135
1618073.56101276473156.866449903
#Sta/Elev= 30
       0  799.77    26.3  788.26    66.3  785.22   109.8  769.57   171.6  760.01
   298.7  749.08   438.2  710.46   470.2  694.03   519.4  675.91     549  669.23
     789  656.05  1017.8  656.49    1065  648.86  1250.2  650.39  1300.8647.7573
    1312  647.41    1369  647.76  1388.7  655.91    1450  656.17  1471.7  660.43
  1674.9   666.5    1755  679.53  2107.4  690.69  2124.9  694.74  2159.9  686.36
  2205.5  684.81    2230  694.64  2395.1  718.45    2526  768.13  2562.9  775.46
#Mann= 12 ,-1,0
       0      .1       0      80     .05       0     910     .06       0
    1040     .05       0    1270      .1       0  1300.8    .045       0
    1369      .1       0    1450     .05       0 1997.76     .07       0
 2127.76     .06       0 2247.76     .05       0 2317.76      .1       0
Bank Sta=1300.8,1369
XS Rating Curve= 0 ,0
Exp/Cntr(USF)=0,0
Exp/Cntr=0.3,0.1

Type RM Length L Ch R = 1 ,1737    ,654.6,676.8,695.4
XS GIS Cut Line= 2
1616426.32339181472292.9005172791617989.53446712473153.544817167
#Sta/Elev= 30
       0  691.07      38  686.76   142.9  665.14   312.7  654.54   670.9  652.55
     817  654.91   865.7  651.31   963.1  650.84  1082.9  653.53  1161.6  650.51
  1191.5  645.38    1214  643.56 1292.43645.3264  1300.1  655.38  1308.3  661.51
  1345.1  663.65  1381.8   678.1  1423.9  702.94  1479.9  732.08  1513.6  744.52
  1536.1  744.39  1554.8  738.18  1633.4  683.53  1641.2  682.08  1677.4  699.82
  1693.4  705.32  1723.2  725.89  1738.3  732.16  1760.8  750.15  1784.5  750.27
#Mann= 10 ,-1,0
       0      .1       0      50     .05       0     800      .1       0
     940     .05       0    1120      .1       0    1180     .07       0
  1191.5    .045       0 1292.43     .07       0    1310     .06       0
    1430      .1       0
Bank Sta=1191.5,1292.43
XS Rating Curve= 0 ,0
Exp/Cntr(USF)=0,0
Exp/Cntr=0.3,0.1

Type RM Length L Ch R = 1 ,1060    ,924.9,963.5,987
XS GIS Cut Line= 2
1616268.24586734472369.0119179491617363.07909237473791.709638172
#Sta/Elev= 30
       0  699.57    99.9  688.75   128.9  674.79   153.7   659.6   170.3  655.46
     191  654.12   471.3  651.07   759.1  654.12   905.5  650.34   956.8  653.28
  1112.3  654.43  1134.8  652.65  1173.1  643.83  1184.5  643.92  1212.2  642.88
  1280.8  643.92  1292.1  646.21  1311.2  659.03  1334.6  661.59  1354.2  675.63
    1422  712.55  1456.2  740.47  1499.1  764.44  1511.6   769.9  1581.9  789.57
  1615.6  796.55  1658.7  796.06  1718.2  790.26  1755.8  779.01  1795.2  771.68
#Mann= 9 ,-1,0
       0     .05       0      20      .1       0      30     .05       0
      60      .1       0     170     .05       0    1160     .07       0
  1184.5    .045       0  1280.8     .06       0    1380      .1       0
#XS Ineff= 2 , 0
          744.19     680
Permanent Ineff=
       F       F
Bank Sta=1184.5,1280.8
XS Rating Curve= 0 ,0
Exp/Cntr(USF)=0,0
Exp/Cntr=0.3,0.1

Type RM Length L Ch R = 1 ,96      ,,,
XS GIS Cut Line= 4
1615463.78224819472444.946028062 1616072.2750329473267.586282448
 1616072.2750329473582.6224681361616252.93230206 474026.68931953
#Sta/Elev= 30
       0  756.03   106.8  736.26   191.2  716.47   252.9  713.46   320.2  685.06
   395.3   661.3   440.7  652.39   929.8  649.69  1007.5  652.41  1069.9  651.05
  1092.7  642.79    1106  641.41 1216.01642.7711  1237.3  653.02  1270.3     654
  1309.4  667.51  1332.4  668.04  1349.7  674.66  1402.8  709.16  1445.3  726.52
  1477.4   754.5    1509  773.98  1544.5  788.31  1568.1  810.57  1604.7  819.06
  1629.5  840.58  1668.4  882.57    1679  890.79  1736.8  907.26  1817.7  936.35
#Mann= 6 ,-1,0
       0      .1       0     450     .05       0  1092.7    .045       0
 1216.01      .1       0 1313.23     .06       0 1408.27      .1       0
Bank Sta=1092.7,1216.01
XS Rating Curve= 0 ,0
Exp/Cntr(USF)=0,0
Exp/Cntr=0.3,0.1
LCMann Table=0

Chan Stop Cuts=-1
Use User Specified Reach Order=0
Composite Channel Slope=5